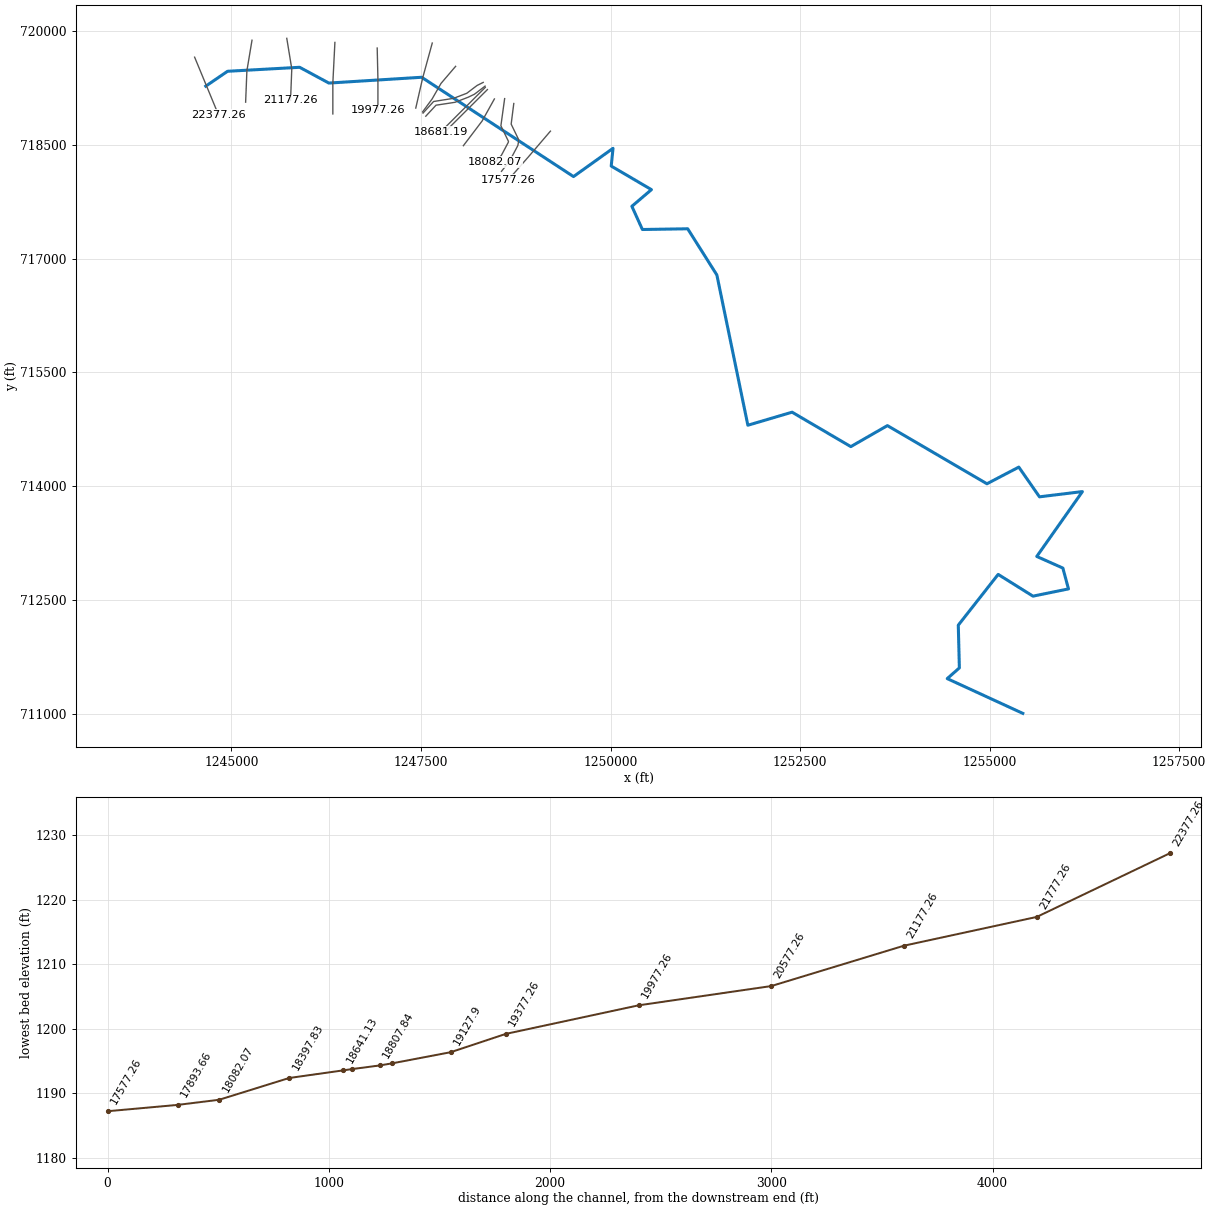
--- CubCreek.prj (project) ---

Proj Title=CubCreek
Current Plan=p01
Default Exp/Contr=0.3,0.1
English Units
Geom File=g01
Flow File=f01
Plan File=p01
Y Axis Title=Elevation
X Axis Title(PF)=Main Channel Distance
X Axis Title(XS)=Station
BEGIN DESCRIPTION:
END DESCRIPTION:
DSS Export Rating Curves= 0
DSS Export Rating Curve Sorted= 0
DSS Export Volume Flow Curves= 0
DXF OffsetX= 0
DXF OffsetY= 0
DXF ScaleX= 1
DXF ScaleY= 10

--- CubCreek.p01 (plan) ---

Plan Title=Approximate Study - 100 YR
Program Version=3.12
Short Identifier=100 Yr
Geom File=g01
Flow File=f01
Subcritical Flow
K Sum by GR= 0
Std Step Tol= 0.01
Critical Tol= 0.01
Num of Std Step Trials= 20
Max Error Tol= 0.3
Flow Tol Ratio= 0.001
Split Flow NTrial= 30
Split Flow Tol= 0.02
Split Flow Ratio= 0.02
Log Output Level= 0
Friction Slope Method= 1
Unsteady Friction Slope Method= 2
Unsteady Bridges Friction Slope Method= 1
Calc Critical at every XS
Parabolic Critical Depth
Global Vel Dist= 0 , 0 , 0
Global Log Level= 0
CheckData=True
Encroach Param=-1 ,10,10, 2
Encroach River=CubCreek
Encroach Reach=Main
Encroach Node=22377.26
       1383.0405431.5172
Encroach Node=21777.26
       1360.4677455.9039
Encroach Node=21177.26
       1392.5216455.0053
Encroach Node=20577.26
       1475.7077576.3819
Encroach Node=19977.26
       1382.9424 442.925
Encroach Node=19377.26
       1313.5593489.0561
Encroach Node=19127.9
       1     250422.3303
Encroach Node=18864.24
       1  276.53  599.76
Encroach Node=18807.84
       1  275.63  556.22
Encroach Node=18681.19
       1249.5963548.6191
Encroach Node=18641.13
       1     265     480
Encroach Node=18397.83
       1     250     400
Encroach Node=18082.07
       1     230     330
Encroach Node=17893.66
       1     306581.5891
Encroach Node=17577.26
       1 423.095542.4934
Encroach Node=17178.13
       1  410.99  550.99
Encroach Node=16883.08
       1  520.99  630.99
Encroach Node=16727.7
       1434.0111530.5987
Encroach Node=16562.34
       1439.9321     490
Encroach Node=16196.56
       1307.4302     390
Encroach Node=15716.32
       1318.1184356.2612
Encroach Node=15410.45
       1220.0566     400
Encroach Node=14920.59
       1314.6358425.6817
Encroach Node=14577.26
       1300.4312529.6148
Encroach Node=14054.17
       1317.2454 433.447
Encroach Node=13598.24
       1364.9915525.8408
Encroach Node=13149.78
       1 348.966544.2385
Encroach Node=12787.01
       1239.5941324.2079
Encroach Node=12544.49
       1224.6137 308.415
Encroach Node=12400.74
       1258.7913430.8115
Encroach Node=12340.68
       1     342     391
Encroach Node=12141.43
       1234.5725291.8599
Encroach Node=11666.7
       1     309     345
Encroach Node=10977.26
       1     600     750
Encroach Node=10377.26
       1 365.135422.0233
Encroach Node=9777.259
       1     380     420
Encroach Node=9177.259
       1     423     467
Encroach Node=8577.259
       1393.4122     500
Encroach Node=8305.97
       1     243     324
Encroach Node=8038.482
       1364.8293     418
Encroach Node=7900.569
       1 293.254354.0578
Encroach Node=7769.93
       1368.2314 408.235
Encroach Node=7377.259
       1     410474.5191
Encroach Node=7012.702
       1341.8833     630
Encroach Node=6760.217
       1267.0767482.1027
Encroach Node=6617.986
       1     317     464
Encroach Node=6308.857
       1551.6086619.7869
Encroach Node=5690.443
       1551.2407     640
Encroach Node=5139.481
       1674.7871730.0158
Encroach Node=4712.437
       1847.3489   888.7
Encroach Node=4025.344
       1 353.405420.9133
Encroach Node=3524.497
       1323.2974405.2078
Encroach Node=3083.877
       1217.9281271.4882
Encroach Node=2779.567
       1307.3201350.4165
Encroach Node=2504.998
       1333.8619396.3549
Encroach Node=1977.259
       1370.7493431.0208
Encroach Node=1377.259
       1329.7082 467.199
Encroach Node=777.259
       1299.1603 341.995
Encroach Node=226.893
       1371.5608436.9232
Computation Interval=1HOUR
Output Interval=1HOUR
Run HTab= 0
Run UNet= 0
Run PostProcess= 0
UNET Theta= 1
UNET Theta Warmup= 1
UNET ZTol= 0.02
UNET ZSATol= 0.05
UNET MxIter= 20
UNET MaxInSteps= 0
UNET DtIC= 0
UNET DtMin= 0
UNET MaxCRTS= 20
UNET WFStab= 2
UNET SFStab= 1
UNET WFX= 1
UNET SFX= 1
UNET DSS MLevel= 4
UNET DZMax Abort= 100
UNET Convert EG Bridges=-1
UNET Use Existing IB Tables=-1
UNET Froude Reduction=False
UNET Froude Limit= 1
UNET Froude Power= 10
Instantaneous Interval=1HOUR
Write IC File= 0
Echo Input=False
Echo Output=False
Write Detailed= 0
Detailed Automatic Start=False, 10

--- CubCreek.f01 (steady flow) ---

Flow Title=CubCreek
Program Version=3.12
Number of Profiles= 2
Profile Names=P100yr,Encroachments
River Rch & RM=CubCreek,Main            ,22377.26
     880     880
River Rch & RM=CubCreek,Main            ,21177.26
    1350    1350
River Rch & RM=CubCreek,Main            ,19977.26
    1810    1810
River Rch & RM=CubCreek,Main            ,17577.26
    1970    1970
River Rch & RM=CubCreek,Main            ,14054.17
    2180    2180
River Rch & RM=CubCreek,Main            ,9177.259
    2520    2520
River Rch & RM=CubCreek,Main            ,7012.702
    2750    2750
Boundary for River Rch & Prof#=CubCreek,Main            , 1
Up Type= 0
Dn Type= 3
Dn Slope=0.013
DSS Import GetInterval= 0
DSS Import GetPeak= 0
DSS Import FillOption= 0

--- CubCreek.g01 (geometry) ---

Geom Title=Approximate Geometry
Program Version=3.12

River Reach=CubCreek        ,Main
Reach XY= 30
  1244661.380103   719275.380525  1244948.128778   719471.378211
  1245899.498496   719523.995445  1246284.379104   719316.000528
  1247508.251627   719392.501537  1249511.248873   718082.629405
  1250032.378879   718455.500553  1250008.499214   718221.250358
  1250539.127821   717910.499103  1250280.997858   717690.634033
  1250419.631092   717384.630048  1251017.130818   717394.190259
  1251401.995239   716784.688935  1251810.751504   714803.060494
  1252394.001403   714975.190796   1253168.50177   714521.059088
  1253651.379217   714798.309164  1254963.631124    714031.00136
  1255384.249321   714250.940169  1255656.748016   713858.940686
  1256223.249407   713928.249132  1255621.002257   713072.500486
  1255965.131777   712919.498519    1256039.2489    712644.62827
  1255570.748407   712548.998926  1255111.750574   712835.878686
  1254585.996263   712166.559499  1254600.250354   711602.441995
  1254440.129512   711461.441318  1255436.878835   711002.939151

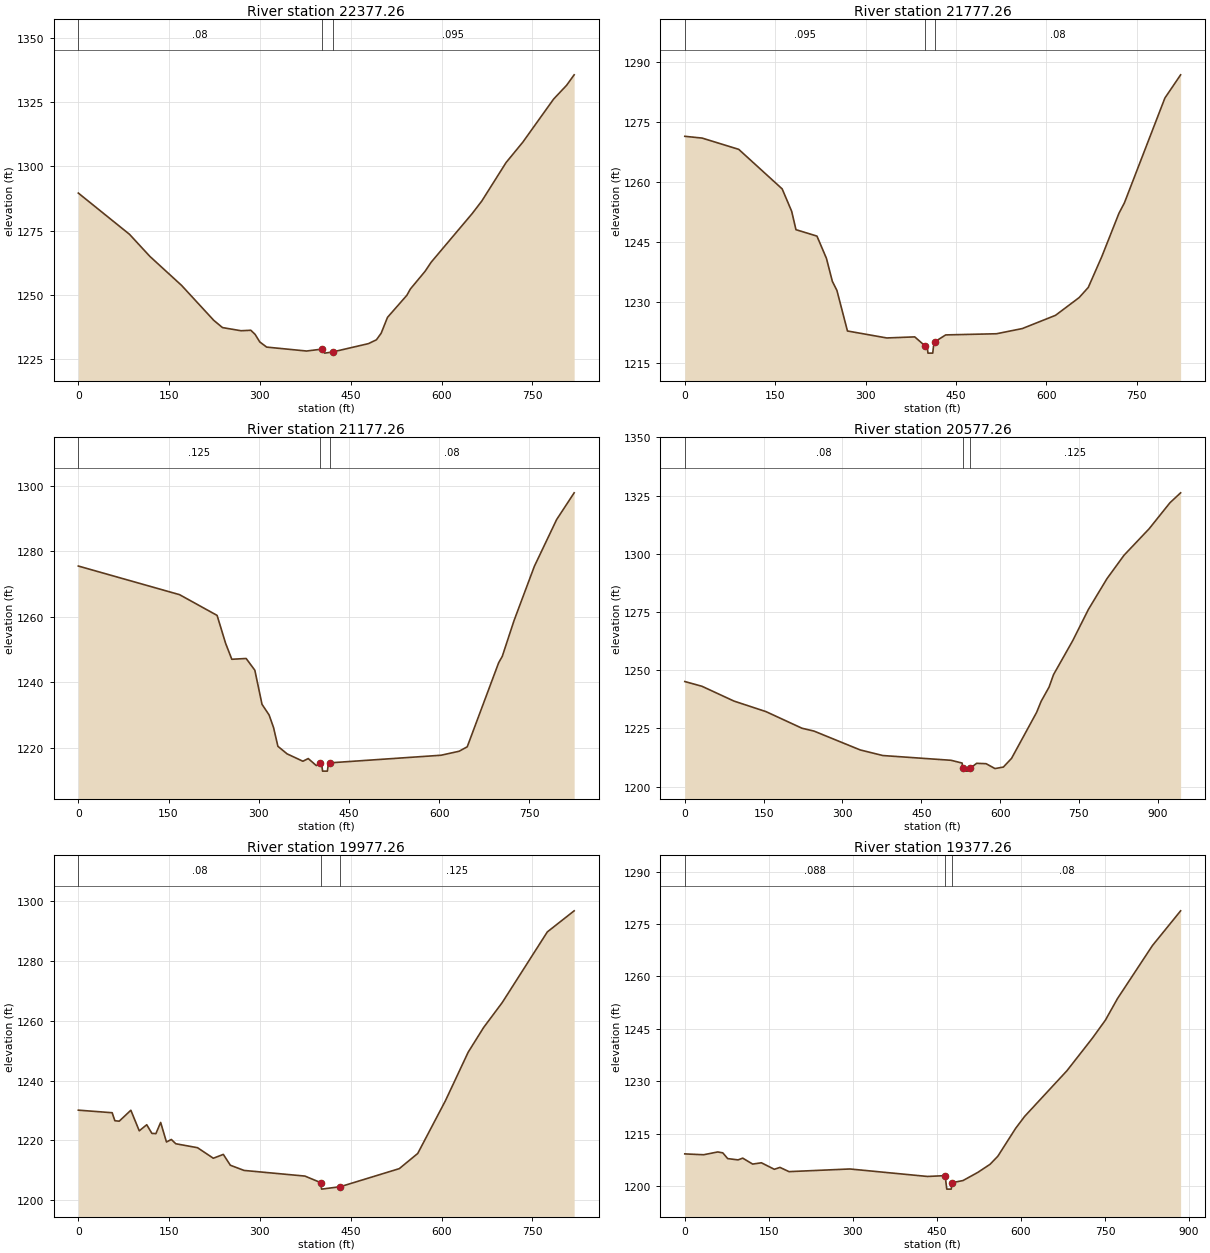
Type RM Length L Ch R = 1 ,22377.26,616.63,600,586.33
XS GIS Cut Line= 3
  1244514.037862   719657.590257  1244670.620181   719279.204188
  1244827.199005   718900.826701
#Sta/Elev= 30
       0 1289.62   84.57 1273.53   118.3  1264.9  170.51 1253.62  223.74 1239.98
  238.16 1237.16  268.73 1235.93  284.94 1236.12  291.99 1234.51  299.73 1231.56
  311.11 1229.55  377.01 1228.02  401.87 1228.75  406.93  1227.2  419.95 1227.65
  479.11  1230.9  492.35 1232.39   500.2 1234.95  510.69 1241.15   542.7 1249.77
  548.36 1252.18  572.73  1259.1  582.72 1262.63  650.65 1281.65  666.53 1286.55
  706.58 1301.54  734.01 1309.42  785.06 1326.28  806.46 1331.64     819 1335.74
#Mann= 3 , 0 , 0
       0     .08       0  401.87    .048       0  419.95    .095       0
Bank Sta=401.87,419.95
Exp/Cntr=0.3,0.1

Type RM Length L Ch R = 1 ,21777.26,590.06,600,599.84
XS GIS Cut Line= 3
  1245270.886102   719881.244099  1245203.530827   719478.225102
  1245186.850148   719064.010132
#Sta/Elev= 30
       0 1271.52   28.67 1271.08   89.53 1268.26  161.66 1258.38  177.44 1252.78
  184.57 1248.19   219.4 1246.59  235.14 1241.03  244.95 1235.29  252.59 1232.99
  270.05 1222.88   335.3 1221.14  381.75 1221.41  399.43 1219.08  402.73  1218.6
  403.67 1217.35  411.62 1217.35  412.91 1219.07  415.85 1220.25  433.12  1221.9
  517.51 1222.19  560.39 1223.49  615.42 1226.79  654.71 1231.23  669.86 1233.77
  692.33 1241.47  720.78 1252.29  729.81 1254.88  797.04 1281.08  823.16 1286.88
#Mann= 3 , 0 , 0
       0    .095       0  399.43    .048       0  415.85     .08       0
Bank Sta=399.43,415.85
Exp/Cntr=0.3,0.1

Type RM Length L Ch R = 1 ,21177.26,606.19,600,600.62
XS GIS Cut Line= 3
  1245729.543197    719905.92903  1245795.583871   719502.495761
  1245779.108375    719086.99142
#Sta/Elev= 30
       0 1275.52  168.33 1266.78  230.78 1260.45  244.98  1251.9  255.27 1247.05
   279.1 1247.29  293.55 1243.71   305.5 1233.29  317.28 1230.04  324.75 1226.15
  331.92 1220.47  347.14 1218.17  373.49 1215.91  382.39 1216.73  395.78 1214.59
  402.65  1215.3  405.21 1214.27  406.24 1212.89   414.2 1212.89  415.97 1215.25
  417.78 1215.41  603.22 1217.74  633.31 1218.96  646.81 1220.32  699.15 1246.03
  705.05 1247.93  724.56 1258.82  758.47 1275.45  795.42 1289.69  824.63 1297.88
#Mann= 3 , 0 , 0
       0    .125       0  402.65    .048       0  417.78     .08       0
Bank Sta=402.65,417.78
Exp/Cntr=0.3,0.1

Type RM Length L Ch R = 1 ,20577.26,597.7,600,599.98
XS GIS Cut Line= 3
  1246364.287346   719852.108291  1246336.927377   719316.000528
  1246336.927377   718909.199799
#Sta/Elev= 30
       0 1245.11   32.66 1243.08   93.47 1236.73  154.54 1232.19  222.91 1225.06
  245.84 1223.83  333.85 1215.73  376.79 1213.33  506.86 1211.28  527.71  1210.1
  529.47 1207.87  530.31 1206.63  538.25 1206.63  543.17 1207.82  555.43 1209.99
  573.41 1209.82  590.36 1207.73  606.22 1208.37  621.85 1212.11  669.62  1231.9
  678.16 1236.62  693.23 1242.72  701.75 1248.08  738.39 1262.72  767.97 1276.03
  803.38 1289.28  835.91 1299.36   883.8 1310.76  923.32 1321.91  943.61 1326.17
#Mann= 3 , 0 , 0
       0     .08       0  529.47    .048       0  543.17    .125       0
Bank Sta=529.47,543.17
Exp/Cntr=0.3,0.1

Type RM Length L Ch R = 1 ,19977.26,608.69,600,593.14
XS GIS Cut Line= 3
  1246922.064571    719778.15437  1246931.706948   719368.630043
  1246931.706948   718959.154378
#Sta/Elev= 30
       0 1230.08    55.9 1229.22   60.36 1226.54   67.56 1226.39   86.76 1230.05
  100.66 1223.16     113  1225.2  121.53  1222.3  128.12 1222.22     136 1225.97
   145.6 1219.42  153.61 1220.27  161.05 1218.83   196.9 1217.51  223.05 1213.98
  239.53 1215.27  251.14 1211.64  273.79  1209.9  374.26 1208.01  400.21 1205.83
  401.85 1203.64  432.91 1204.46  530.22  1210.5  560.69 1215.58  606.43 1233.23
  644.05 1249.49  669.59 1257.77  700.35 1266.12  774.78 1289.76  819.11 1296.82
#Mann= 3 , 0 , 0
       0     .08       0  400.21    .048       0  432.91    .125       0
Bank Sta=400.21,432.91
Exp/Cntr=0.3,0.1

Type RM Length L Ch R = 1 ,19377.26,258.28,249.36,240.52
XS GIS Cut Line= 3
  1247648.295245   719843.903739   1247522.92297     719387.6053
  1247430.830557   718986.206803
#Sta/Elev= 30
       0 1209.28   33.65 1209.04   58.94 1209.84   67.82 1209.58   76.53 1207.94
   95.12 1207.57  103.35 1208.07  121.12 1206.37  136.76 1206.74  159.77 1204.88
  169.87 1205.42  186.06 1204.21  294.67 1204.97   433.2 1202.83  464.74 1203.07
  467.63 1199.21  475.58 1199.21  477.01 1201.05  496.58 1201.66  522.98 1203.99
  544.84  1206.3  558.75 1208.61  590.46 1216.57  606.77 1220.03  682.13 1233.06
  727.71  1242.4   750.8 1247.53   772.3 1253.67  834.73 1268.84  885.04 1278.77
#Mann= 3 , 0 , 0
       0    .088       0  464.74    .048       0  477.01     .08       0
Bank Sta=464.74,477.01
Exp/Cntr=0.3,0.1

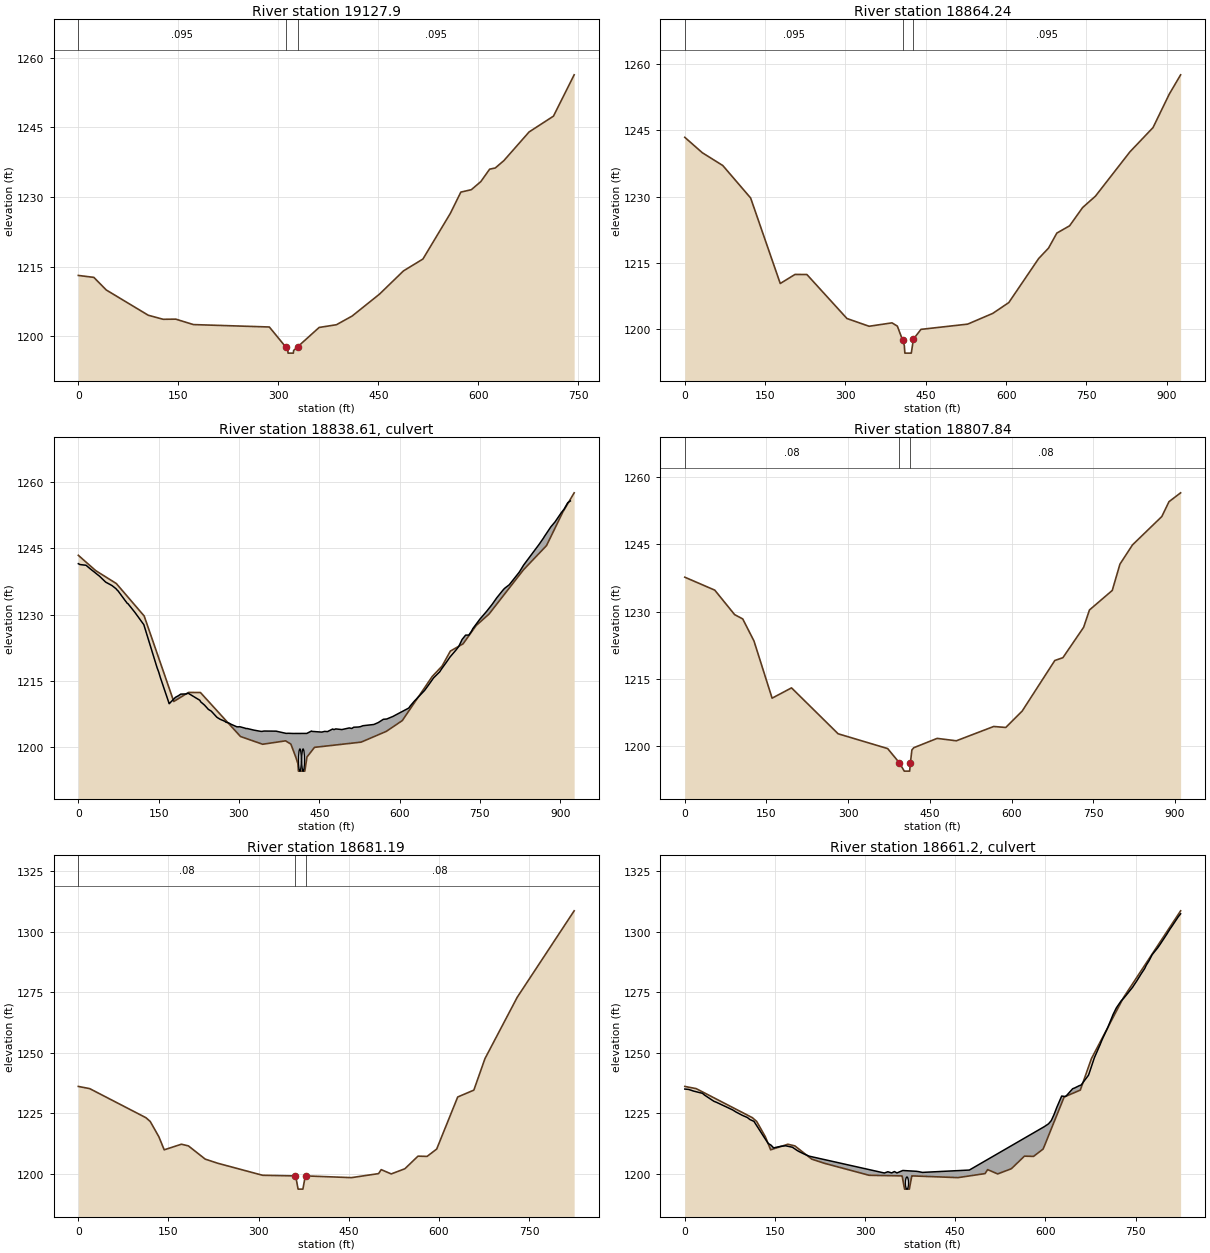
Type RM Length L Ch R = 1 ,19127.9 ,280.2,263.66,245.7
XS GIS Cut Line= 4
   1247956.10883   719536.491116  1247763.871191   719311.468718
  1247646.144239   719105.819149  1247520.966202   718935.934711
#Sta/Elev= 30
       0 1213.11   23.29 1212.69   41.87 1209.98  104.94 1204.53  127.32 1203.66
  146.22 1203.69  172.72 1202.52  286.61    1202  310.88 1197.75  314.06 1197.18
  314.67 1196.37  322.63 1196.37  323.06 1196.94  329.52 1197.79  361.31  1201.9
  387.29 1202.49  410.81 1204.36  451.87 1209.08  487.87 1214.09  517.02 1216.64
  558.13 1226.47  573.91 1231.06  589.64 1231.58  603.87 1233.32   617.1    1236
  625.56 1236.26  638.45 1237.84  676.32 1244.02   712.9 1247.43  743.94 1256.33
#Mann= 3 , 0 , 0
       0    .095       0  310.88    .048       0  329.52    .095       0
Bank Sta=310.88,329.52
Exp/Cntr=0.5,0.3

Type RM Length L Ch R = 1 ,18864.24,56.394,56.394,56.394
XS GIS Cut Line= 6
  1248320.462537   719324.888151  1248239.092885     719284.2033
   1248104.16081   719181.665607  1247930.226458   719114.844692
  1247666.088888   719072.868003  1247526.764516   718920.392997
#Sta/Elev= 30
       0 1243.41    32.7 1239.93   70.93 1237.04  122.98  1229.7  178.27 1210.38
  205.82 1212.43  228.03 1212.41  302.85 1202.47   344.2 1200.72  386.98 1201.49
  396.97 1200.75   406.6 1197.65     410 1196.35     411 1194.65     423 1194.65
  427.01 1197.83  441.11 1200.02   528.2  1201.2  575.19 1203.63  605.08 1206.07
  660.86 1216.02   679.3 1218.38   694.8 1221.77  718.67 1223.42  742.94 1227.54
  766.94 1230.12  831.34 1240.13  874.45 1245.61  904.85 1253.18     926 1257.53
#Mann= 3 , 0 , 0
       0    .095       0   406.6    .048       0  427.01    .095       0
Bank Sta=406.6,427.01
Exp/Cntr=0.5,0.3

Type RM Length L Ch R = 2 ,18838.61,,,
BEGIN DESCRIPTION:
Culvert: 3723-257 Gravel Drive
END DESCRIPTION:
Bridge Culvert--1,0,-1,-1, 0
Deck Dist Width WeirC Skew NumUp NumDn MinLoCord MaxHiCord MaxSubmerge Is_Ogee
19.2,18,2.6,0, 146, 145, 1203.2, , 0.95, 0, 0,0,,
       0    2.65    2.86    3.47   14.41   21.21    39.5   51.11   62.74   70.43
   71.48   74.11   83.57   86.64    91.2   92.72  103.06   105.5  115.27  122.31
  147.03  150.19  153.05  166.39  169.69  170.37  181.28   183.6  187.32  191.24
  201.18  204.47  205.46  213.03   213.4  213.45  225.67  226.95  228.53  235.45
  242.85  248.28  256.21  258.85  264.98  266.25  273.71  275.32  281.14  284.41
  285.26  296.11  301.97  311.64  312.39  312.57  315.22   326.5  328.15  339.77
  340.96  342.88  346.77   369.4  387.98  392.65  400.41  421.39  426.62  435.41
  436.32  450.03  454.18   454.7  459.99  465.35  475.03  476.67  477.57  480.74
   492.1  505.98  509.42  510.72  514.29  523.11  527.01  531.42  551.84  560.24
  569.65  574.01  576.03  585.62  587.79  590.34  616.88  618.33  619.56  627.74
   641.5  646.64  654.01  663.54  672.65  674.85  678.54  687.73  694.04  705.05
  710.47  715.66  716.72  723.27   729.3  734.14  736.89  748.19  750.15  752.06
  762.55  772.64  780.83  781.22  781.55  794.05   796.6  801.38  804.82   823.1
  825.31  831.31  833.42  844.55  847.27  853.92  860.58  869.03  870.11  882.51
  890.32  902.03   905.7  907.15  914.02  918.94
 1241.52 1241.34 1241.33 1241.32 1241.16 1240.46  1238.7 1237.35 1236.59 1235.86
 1235.68 1235.38 1233.84 1233.35 1232.58 1232.48 1230.93 1230.54 1228.91 1227.74
 1218.03 1217.01 1215.84 1211.06 1209.88 1209.96 1211.32 1211.47 1211.72 1212.05
 1212.09 1212.22 1212.23 1211.67 1211.65 1211.65 1210.76 1210.65  1210.3 1209.59
  1208.6  1208.2 1207.14 1206.81 1206.35 1206.29 1205.91 1205.72 1205.52 1205.28
 1205.24 1204.66 1204.67 1204.35 1204.28 1204.27 1204.28 1203.94 1203.91 1203.64
 1203.63 1203.62 1203.71 1203.68 1203.18  1203.2 1203.16 1203.18 1203.17 1203.71
 1203.63  1203.5 1203.47 1203.47 1203.63 1203.58 1204.17 1204.06 1204.03 1204.19
 1204.04 1204.41 1204.34 1204.29 1204.57 1204.62  1204.7 1204.91 1205.19 1205.63
 1206.36 1206.42 1206.43  1206.9 1207.02 1207.19 1208.89  1209.1 1209.33 1210.49
 1212.25 1212.88  1214.1 1215.73 1216.83 1217.08 1217.77 1219.31 1220.42 1221.97
 1222.82 1224.15  1224.4 1225.38 1225.39 1226.25 1226.87  1228.7 1229.02 1229.28
 1230.76  1232.3 1233.72 1233.78 1233.83  1235.7    1236 1236.46 1236.76 1239.55
 1239.96 1241.15  1241.5  1243.3 1243.77 1244.84  1245.9 1247.37 1247.61 1249.85
 1250.97 1253.05 1253.64 1253.84  1255.3  1255.7
                                                                                
                                                                                
                                                                                
                                                                                
                                                                                
                                                                                
                                                                                
                                                                                
                                                                                
                                                                                
                                                                                
                                                                                
                                                                                
                                                                                
                                                
       0    2.65    2.86    3.47   14.41   21.21    39.5   51.11   62.74   70.43
   71.48   74.11   83.57   86.64    91.2   92.72  103.06   105.5  115.27  122.31
  147.03  150.19  153.05  166.39  169.69  170.37  181.28   183.6  187.32  191.24
  201.18  204.47  205.46  213.03   213.4  213.45  225.67  226.95  228.53  235.45
  242.85  248.28  256.21  258.85  264.98  266.25  273.71  275.32  281.14  284.41
  285.26  296.11  301.97  311.64  312.39  312.57  315.22   326.5  328.15  339.77
  340.96  342.88  346.77  359.91   369.4  379.31  387.98  392.65  400.41  421.39
  426.62  450.03  454.18   454.7  459.99  465.35  475.03  476.67  477.57  480.74
   492.1  505.98  509.42  510.72  514.29  523.11  527.01  531.42  551.84  560.24
  574.01  576.03  585.62  587.79  590.34  616.88  618.33  619.56  627.74   641.5
  646.64  654.01  663.54  672.65  674.85  678.54  687.73  694.04  705.05  710.47
  715.66  716.72  723.27   729.3  734.14  736.89  748.19  750.15  752.06  762.55
  772.64  780.83  781.22  781.55  794.05   796.6  801.38  804.82   823.1  825.31
  831.31  833.42  844.55  847.27  853.92  860.58  869.03  870.11  882.51  890.32
  902.03   905.7  907.15  914.02  918.94
 1241.52 1241.34 1241.33 1241.32 1241.16 1240.46  1238.7 1237.35 1236.59 1235.86
 1235.68 1235.38 1233.84 1233.35 1232.58 1232.48 1230.93 1230.54 1228.91 1227.74
 1218.03 1217.01 1215.84 1211.06 1209.88 1209.96 1211.32 1211.47 1211.72 1212.05
 1212.09 1212.22 1212.23 1211.67 1211.65 1211.65 1210.76 1210.65  1210.3 1209.59
  1208.6  1208.2 1207.14 1206.81 1206.35 1206.29 1205.91 1205.72 1205.52 1205.28
 1205.24 1204.66 1204.67 1204.35 1204.28 1204.27 1204.28 1203.94 1203.91 1203.64
 1203.63 1203.62 1203.71 1203.74 1203.68 1203.54 1203.18  1203.2 1203.16 1203.18
 1203.17  1203.5 1203.47 1203.47 1203.63 1203.58 1204.17 1204.06 1204.03 1204.19
 1204.04 1204.41 1204.34 1204.29 1204.57 1204.62  1204.7 1204.91 1205.19 1205.63
 1206.42 1206.43  1206.9 1207.02 1207.19 1208.89  1209.1 1209.33 1210.49 1212.25
 1212.88  1214.1 1215.73 1216.83 1217.08 1217.77 1219.31 1220.42 1221.97 1222.82
 1224.15  1224.4 1225.38 1225.39 1226.25 1226.87  1228.7 1229.02 1229.28 1230.76
  1232.3 1233.72 1233.78 1233.83  1235.7    1236 1236.46 1236.76 1239.55 1239.96
 1241.15  1241.5  1243.3 1243.77 1244.84  1245.9 1247.37 1247.61 1249.85 1250.97
 1253.05 1253.64 1253.84  1255.3  1255.7
                                                                                
                                                                                
                                                                                
                                                                                
                                                                                
                                                                                
                                                                                
                                                                                
                                                                                
                                                                                
                                                                                
                                                                                
                                                                                
                                                                                
                                        
BR Coef=-1 , 0 , 0 ,, 0 ,,,0.8,-1,,0,
WSPro=,,,, 1 ,,,, 0 ,,,, 0 ,,,,-1 ,-1 ,-1 , 0 , 0 , 0 , 0 , 0
Multiple Barrel Culv=1,5,,18,0.027,0.9,1,2,3,1194.65,1194.32, 2,Culvert #1  , 0 ,19.2
   413.8  404.82   419.8  410.82
Culvert Bottom n=0.027
BC Design=,, 0 ,, 0 ,,,,,,

Type RM Length L Ch R = 1 ,18807.84,116.74,126.65,136.56
XS GIS Cut Line= 6
   1248345.05929   719275.694646  1248204.990082   719169.055808
   1248122.68598   719129.549847  1247947.826068   719062.203718
  1247697.615519   719024.056961   1247563.18538   718879.179899
#Sta/Elev= 30
       0 1237.67   55.03 1234.78   91.47 1229.31   106.4 1228.34  127.05 1223.41
  160.32 1210.63     196 1212.93  281.53 1202.67  372.53 1199.36  394.07 1196.17
     403 1194.32  412.86 1194.32  414.33  1196.2  416.97 1199.05  420.57 1199.56
  463.36 1201.64   498.6  1201.1  567.24  1204.3  589.32 1204.08  619.47 1207.74
  679.43 1219.05  694.29 1219.68   732.4 1226.48  743.03 1230.34  784.93 1234.71
  799.05 1240.59  822.05 1244.89  875.92 1251.23  889.09 1254.55  910.46 1256.53
#Mann= 3 , 0 , 0
       0     .08       0  394.07    .048       0  414.33     .08       0
Bank Sta=394.07,414.33
Exp/Cntr=0.5,0.3

Type RM Length L Ch R = 1 ,18681.19,40.062,40.062,40.062
XS GIS Cut Line= 2
  1248347.323088   719258.569275  1247763.159037   718675.895461
#Sta/Elev= 30
       0 1236.11   18.88 1235.21  112.44 1223.22   119.6 1221.67  133.97 1215.38
  142.91 1209.96   171.5 1212.27   183.2 1211.58  211.21 1206.12   231.9 1204.43
  306.64 1199.46  360.53  1199.2  361.69 1199.11  365.71 1193.75  373.67 1193.75
  377.75 1199.19  378.85  1199.2  454.55 1198.49  499.62 1200.15     504 1201.79
  520.67 1200.02  543.38 1202.15   565.2 1207.35  580.34 1207.25  596.33 1210.28
   631.3 1231.75  658.18 1234.59  676.65 1247.58  730.42 1272.92  825.08 1308.54
#Mann= 3 , 0 , 0
       0     .08       0  360.53    .048       0  378.85     .08       0
Bank Sta=360.53,378.85
Exp/Cntr=0.5,0.3

Type RM Length L Ch R = 2 ,18661.2 ,,,
BEGIN DESCRIPTION:
Culvert: 3723-1043 Gravel Drive
END DESCRIPTION:
Bridge Culvert--1,0,-1,-1, 0
Deck Dist Width WeirC Skew NumUp NumDn MinLoCord MaxHiCord MaxSubmerge Is_Ogee
14.03,12,2.6,0, 83, 100, 1200.75, , 0.95, 0, 0,0,,
       0     6.6   14.57   29.41   32.85   48.59   52.04   55.83    79.5   84.81
   95.85  104.13  108.31  115.07  131.06  138.79  143.44  147.88  153.45  159.37
   166.5  167.37  167.63  179.03  180.27  186.63  190.07   197.7  201.94   207.1
  332.03  337.89   344.2  348.78  352.99  362.77  384.99  388.27  395.62   400.7
  473.49  598.48   605.3  609.92  614.59  619.14  627.14  633.17  635.11  645.36
     649  656.07  659.49  671.77  672.41  672.93  681.51  691.18  694.12  695.79
  703.26   712.7  718.18  726.28  730.65  738.84  745.27  747.52   751.6  759.45
   765.3  767.68  772.64  777.72  786.88  790.74  800.56  802.19  807.83  808.07
  809.29  821.06  825.08
 1235.03 1234.86 1234.19 1233.27 1232.54 1229.95 1229.63  1229.2 1226.44 1225.61
 1224.17 1223.28 1222.46  1221.7 1215.51 1212.59  1211.9 1210.75 1211.08 1211.38
 1211.61 1211.64 1211.64 1211.03 1210.82 1209.75 1209.25 1208.33 1207.87 1207.34
  1200.4 1200.92 1200.44    1201 1200.43 1201.44 1201.11    1201 1200.64 1200.72
 1201.62 1219.56  1220.7 1222.05 1224.62 1227.54 1232.14 1231.94 1232.31 1235.15
 1235.51 1236.38 1236.69 1240.74 1241.23 1241.54 1247.93  1253.4  1255.2 1256.15
 1260.03  1265.8 1268.54 1271.46 1272.57 1275.06 1277.05 1277.94 1279.42 1282.56
 1284.74 1286.02 1288.01 1290.47 1293.28 1294.64 1298.34 1298.96 1301.19 1301.28
 1301.68 1306.05 1307.31
                                                                                
                                                                                
                                                                                
                                                                                
                                                                                
                                                                                
                                                                                
                                                                                
                        
       0     6.6   14.57   29.41   32.85   48.59   52.04   55.83    79.5   84.81
   95.85  104.13  108.31  115.07  131.06  138.79  143.44  147.88  153.45  159.37
   166.5  167.37  167.63  179.03  180.27  186.63  190.07   197.7  201.94  316.08
  322.25  328.16  332.03   344.2  348.78  352.99  362.77  384.99  388.27  395.62
   400.7   408.6   503.8  512.67  516.56   519.3  526.66  533.06  539.27  544.64
  548.88  557.28  561.09  567.43  581.56  582.03  582.22  592.29  598.48   605.3
  609.92  614.59  619.14  627.14  633.17  635.11  645.36     649  656.07  659.49
  671.77  672.41  672.93  681.51  691.18  694.12  695.79  703.26   712.7  718.18
  726.28  730.65  738.84  745.27  747.52   751.6  759.45   765.3  767.68  772.64
  777.72  786.88  790.74  800.56  802.19  807.83  808.07  809.29  821.06  825.08
 1235.03 1234.86 1234.19 1233.27 1232.54 1229.95 1229.63  1229.2 1226.44 1225.61
 1224.17 1223.28 1222.46  1221.7 1215.51 1212.59  1211.9 1210.75 1211.08 1211.38
 1211.61 1211.64 1211.64 1211.03 1210.82 1209.75 1209.25 1208.33 1207.87 1200.66
  1200.6 1200.55  1200.4 1200.44    1201 1200.43 1201.44 1201.11    1201 1200.64
 1200.72 1200.38 1205.73 1204.89 1204.66  1205.5 1206.26 1206.15 1206.36 1208.19
 1210.25 1211.48 1212.81 1212.83 1214.97 1214.98    1215 1218.15 1219.56  1220.7
 1222.05 1224.62 1227.54 1232.14 1231.94 1232.31 1235.15 1235.51 1236.38 1236.69
 1240.74 1241.23 1241.54 1247.93  1253.4  1255.2 1256.15 1260.03  1265.8 1268.54
 1271.46 1272.57 1275.06 1277.05 1277.94 1279.42 1282.56 1284.74 1286.02 1288.01
 1290.47 1293.28 1294.64 1298.34 1298.96 1301.19 1301.28 1301.68 1306.05 1307.31
                                                                                
                                                                                
                                                                                
                                                                                
                                                                                
                                                                                
                                                                                
                                                                                
                                                                                
                                                                                
BR Coef=-1 , 0 , 0 ,, 0 ,,,0.8,-1,,0,
WSPro=,,,, 1 ,,,, 0 ,,,, 0 ,,,,-1 ,-1 ,-1 , 0 , 0 , 0 , 0 , 0
Culvert=1,5,,12,0.012,0.5,1,1,1,1193.75,369.69,1193.55,370.04,Culvert #1  , 0 ,14.03
Culvert Bottom n=0.012
BC Design=,, 0 ,, 0 ,,,,,,

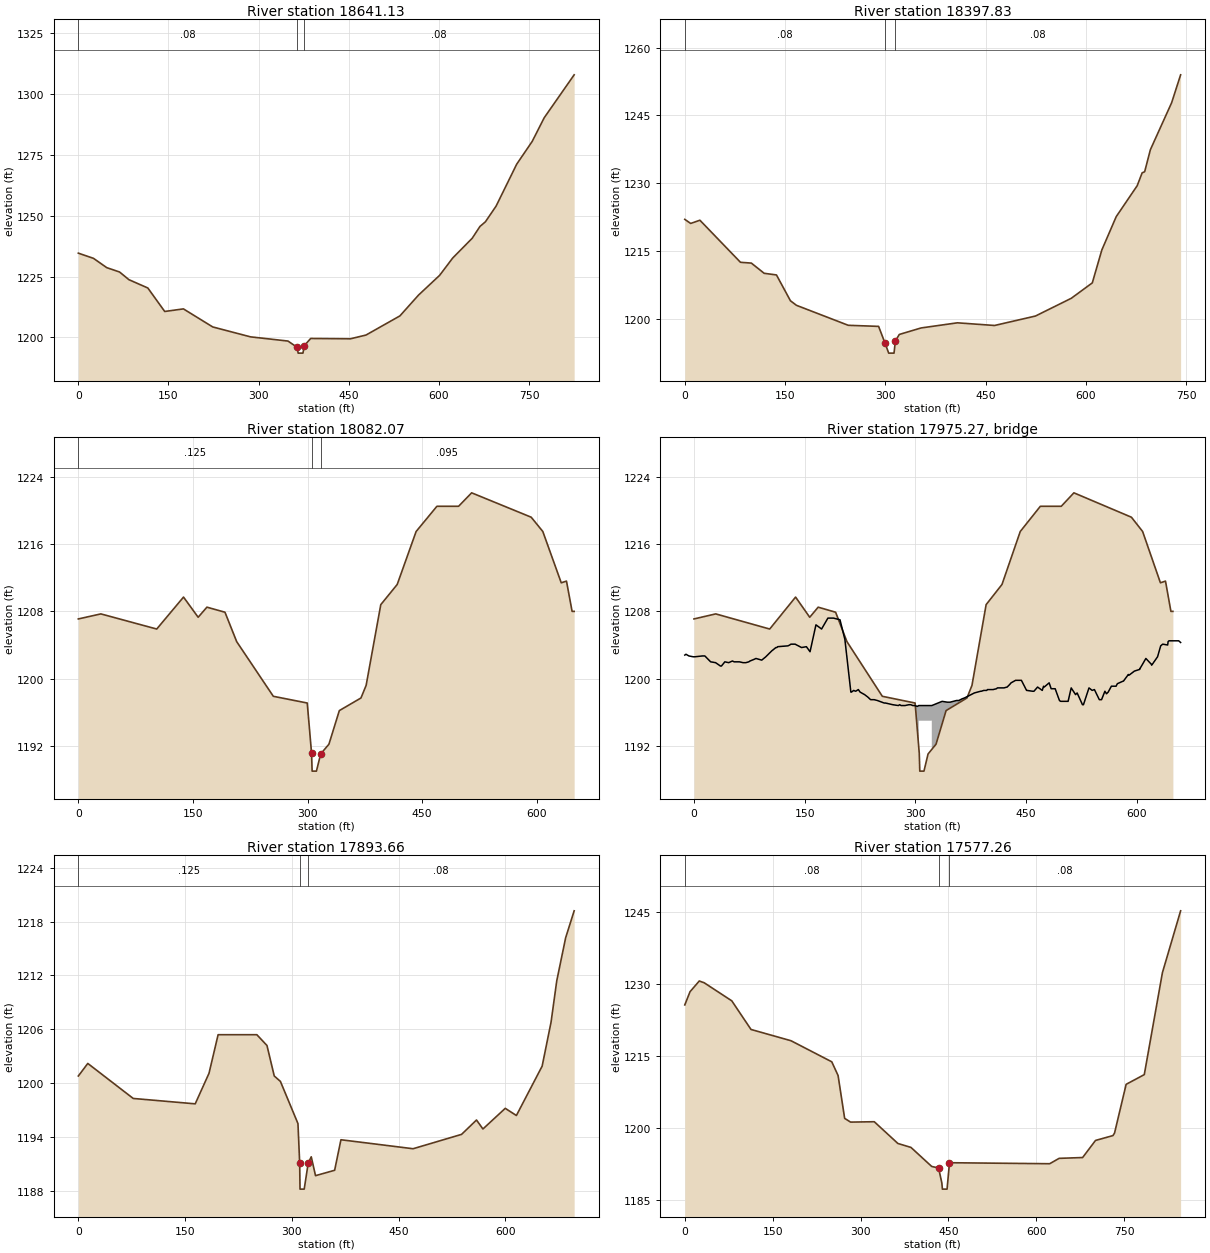
Type RM Length L Ch R = 1 ,18641.13,234.91,243.3,251.28
XS GIS Cut Line= 2
  1248375.571259   719230.248856  1247791.407207   718647.575042
#Sta/Elev= 30
       0 1234.64   25.27  1232.5   47.24 1228.69   68.61 1226.89   84.23 1223.73
  115.66 1220.32  143.75 1210.67  174.89 1211.73  223.65 1204.31  286.51 1200.24
  348.83 1198.51  363.98 1195.97   365.8 1193.55  373.76 1193.55  376.09 1196.65
  386.68 1199.57  452.78 1199.44  478.69 1200.98  535.14 1208.85  566.13 1217.41
  601.19 1225.51  622.99 1232.64   655.4 1240.75   668.3  1245.6  677.38 1247.52
  695.15 1253.96  729.49 1271.21  755.26 1280.56  775.23 1290.28  825.08 1307.93
#Mann= 3 , 0 , 0
       0     .08       0  363.98    .048       0  376.09     .08       0
Bank Sta=363.98,376.09
Exp/Cntr=0.5,0.3

Type RM Length L Ch R = 1 ,18397.83,279.59,315.76,352.25
XS GIS Cut Line= 3
  1248467.619018   719106.530585  1248306.201149   718816.082085
  1248058.702019   718490.072097
#Sta/Elev= 30
       0 1221.98    8.79 1221.08   22.62 1221.79   83.26 1212.48   99.54  1212.3
  118.75 1210.04   137.1 1209.68  158.02 1203.96  166.93 1202.96  244.47 1198.53
  289.86 1198.29   299.3 1194.66  304.98 1192.37  312.94 1192.37  314.96 1195.06
   320.8  1196.5  353.36 1197.94  407.69 1199.08  463.29 1198.49  524.47 1200.58
  578.08 1204.51   609.5 1207.92  623.75  1215.2  645.29 1222.59  676.63 1229.43
  684.07 1232.29   687.8 1232.52  696.36  1237.4  728.15  1247.8   741.6 1253.98
#Mann= 3 , 0 , 0
       0     .08       0   299.3    .048       0  314.96     .08       0
Bank Sta=299.3,314.96
Exp/Cntr=0.5,0.3

Type RM Length L Ch R = 1 ,18082.07,189.09,188.41,224.1
BEGIN DESCRIPTION:
Upstream xs of Bridge 3723-168
END DESCRIPTION:
XS GIS Cut Line= 6
  1248602.923742   719111.059517   1248553.46745   718753.090126
  1248653.317207     718546.7339  1248651.552467   718535.557248
   1248560.51788   718363.602994  1248478.747059   718274.156482
#Sta/Elev= 30
       0  1207.1  29.486  1207.7 102.601  1205.9 137.674  1209.7 156.836  1207.3
 168.291  1208.5 191.909  1207.9 207.253  1204.4 255.195  1197.9 299.601  1197.1
 305.258  1191.1 305.965    1189 311.622    1189 317.1591191.038 327.956  1192.2
 341.603  1196.2 369.888  1197.7 376.676  1199.2 395.838  1208.8 417.334  1211.2
 442.083  1217.5 469.307  1220.5 497.662  1220.5 514.774  1222.1 592.697  1219.2
   607.9  1217.5 632.012  1211.4 638.871  1211.6 646.225    1208 648.912    1208
#Mann= 3 , 0 , 0
       0    .125       0 305.258    .048       0 317.159    .095       0
Bank Sta=305.258,317.159
Skew Angle= 45
Exp/Cntr=0.5,0.3

Type RM Length L Ch R = 3 ,17975.27,,,
BEGIN DESCRIPTION:
Bridge : 3723-168 --- SR 1746
END DESCRIPTION:
Bridge Culvert--1,0,-1,-1, 0
Deck Dist Width WeirC Skew NumUp NumDn MinLoCord MaxHiCord MaxSubmerge Is_Ogee
96.8,20,2.6,45, 167, 65, 1196.8, , 0.95, 0, 0,0,,
 -12.445 -10.889   -6.93  -1.061   1.202  11.526  14.708  22.557  29.274   35.85
  36.345  37.194   41.79  47.023  52.114  54.377  61.518  66.397  70.286  74.317
  75.943    81.6  84.004  91.782  97.298 105.359 111.016 112.289 113.491 127.421
 129.683 131.239 133.997 137.037 145.735 152.311 157.261 165.251 165.251 165.251
 172.888 181.444 181.656 182.009 188.939 197.354 197.707 197.848 199.546 204.071
 204.283 212.273 212.556 213.405 216.375 219.062 222.668 225.072 231.153 235.679
 239.285 244.093 248.477  257.74 258.943 259.508 269.337 276.903 278.741 280.509
 285.883 291.257 293.732  296.49 298.965 302.712 304.551 304.551 322.229 322.229
 336.229   343.3 346.977 355.745 357.018 358.857 363.311 366.423 370.948 379.646
 379.646 379.928 388.343 389.262 392.798 396.687 397.677 399.798 405.314  409.91
 411.041 413.445 414.152 420.021 424.335 427.729 429.638  435.79 439.184 443.639
 450.639 451.063 451.276 458.842 460.609 465.559 471.923  473.62  474.61 481.257
 483.944 489.389 495.187 496.884 498.015  504.45 506.925 511.097 517.036 519.158
  526.37 526.865 527.714 535.209 539.522 542.563  549.21   550.2  552.25 556.776
 558.897 561.231 565.544 571.908 573.676 581.383 581.878 588.596 589.091 590.858
 596.798  603.94 604.081 604.364 612.284 619.779 620.133 620.981 628.123 632.366
 635.053 641.841 642.406 643.609 656.761 659.236 659.377
  1202.8  1202.9  1202.7  1202.6  1202.6  1202.7  1202.7    1202  1201.9  1201.5
  1201.5  1201.5    1202  1201.9  1202.1    1202    1202  1201.9  1201.9    1202
  1202.1  1202.3  1202.4  1202.2  1202.6  1203.3  1203.7  1203.7  1203.8  1203.9
    1204  1204.1  1204.1  1204.1  1203.7  1203.8  1203.2  1206.4  1206.4  1206.4
  1205.9  1207.2  1207.2  1207.2  1207.2    1207    1207    1207  1206.4  1204.8
  1204.8  1198.6  1198.4  1198.4  1198.6  1198.5  1198.7  1198.4  1198.1  1197.8
  1197.5  1197.5  1197.4  1197.1  1197.1  1197.1  1196.9  1196.8  1196.9  1196.8
  1196.8  1196.9  1196.9  1196.8  1196.8  1196.7  1196.8  1196.8  1196.8  1196.8
  1197.3  1197.2  1197.2  1197.4  1197.4  1197.4  1197.6  1197.7  1197.9  1198.3
  1198.3  1198.3  1198.5  1198.5  1198.6  1198.6  1198.7  1198.7  1198.7  1198.8
  1198.9  1198.9  1198.9  1198.9    1199  1199.3  1199.5  1199.8  1199.8  1199.8
  1198.6  1198.6  1198.6  1198.5  1198.5    1199  1198.6  1199.1    1199  1199.5
  1198.8  1198.8  1197.4  1197.3  1197.3  1197.3  1197.3  1198.9  1198.1  1198.3
  1196.9  1196.9  1196.9  1198.9  1198.6  1198.7  1197.5  1197.5  1197.5  1198.5
  1198.2  1198.4  1199.1  1199.1  1199.4  1199.7  1199.7  1200.5  1200.4  1200.5
  1200.9  1201.1  1201.2  1201.2  1202.4  1201.7  1201.6  1201.7  1202.6  1203.9
  1204.1    1204  1204.4  1204.5  1204.5  1204.3  1204.3
                                                                                
                                                                                
                                                                                
                                                                                
                                                                                
                                                                                
                                                                                
                                                            1195    1195
                                                                                
                                                                                
                                                                                
                                                                                
                                                                                
                                                                                
                                                                                
                                                                                
                                                        
       1     210 265.236 265.519 266.367 269.337 272.024  275.63 278.034 284.115
 288.641 292.247 297.056  301.44 310.349 310.349 328.027 328.027 329.865 331.704
 333.472 338.916  344.22 346.694 349.523 351.927 355.675 358.927 389.192 396.333
  399.94 408.708 410.051  411.89 416.274 419.385 423.911 432.891 442.225  445.76
 503.601 504.026 524.956 634.345  634.84 641.629 642.053 643.821 649.831 656.902
 657.044 657.326 665.246 672.741 673.166 673.943 681.085 685.399 688.015 694.803
 695.369 696.642 709.723 712.269  712.41
    1203  1205.9  1198.6  1198.4  1198.4  1198.6  1198.5  1198.7  1198.4  1198.1
  1197.8  1197.5  1197.5  1197.4  1196.8  1196.8  1196.8  1196.8  1196.8  1196.9
  1196.8  1196.8  1196.9  1196.9  1196.8  1196.8  1196.7  1196.8  1197.3  1197.2
  1197.2  1197.4  1197.4  1197.4  1197.6  1197.7  1197.9  1198.3  1198.5  1198.6
  1198.6  1198.6  1198.6  1199.7  1199.7  1200.5  1200.4  1200.5  1200.9  1201.1
  1201.2  1201.2  1202.4  1201.7  1201.6  1201.7  1202.6  1203.9  1204.1    1204
  1204.4  1204.5  1204.5  1204.3  1204.3
                                                                                
                                            1195    1195
                                                                                
                                                                                
                                                                                
                                                                                
                                        
BR Coef=-1 , 1 , 0 ,, 0 ,,,0.8,0,1.2,0,
WSPro=,,,, 1 ,,,, 0 ,,,, 0 ,,,,-1 ,-1 ,-1 , 0 , 0 , 0 , 0 , 0
BC Design=,, 0 ,, 0 ,,,,,,

Type RM Length L Ch R = 1 ,17893.66,357.73,316.4,236.83
BEGIN DESCRIPTION:
Down stream xs of Bridge 3723-168
END DESCRIPTION:
XS GIS Cut Line= 6
  1248723.562929   719046.439401  1248688.903362   718774.486473
  1248789.357518   718566.881266   1248777.76865   718493.485188
  1248668.499325   718287.087494  1248561.094222   718151.748547
#Sta/Elev= 30
       0  1200.8  13.294  1202.2  77.145  1198.3 164.261  1197.7 183.636  1201.1
 196.434  1205.4 250.881  1205.4 265.094  1204.2 275.347  1200.8 283.974  1200.2
 308.652  1195.5 311.056  1191.1 311.523  1188.2  317.42  1188.2 323.077  1191.1
  327.32  1191.8  333.33  1189.7   360.2  1190.3 369.039  1193.7 470.438  1192.7
 538.603  1194.3 559.534  1195.9 568.585  1194.9  599.98  1197.2 615.607  1196.4
 651.811  1201.9 664.327  1206.8 672.317  1211.4 684.833  1216.2 696.783  1219.2
#Mann= 3 , 0 , 0
       0    .125       0 311.056    .048       0 323.077     .08       0
Bank Sta=311.056,323.077
Skew Angle= 45
Exp/Cntr=0.5,0.3

Type RM Length L Ch R = 1 ,17577.26,361.96,399.13,479.78
XS GIS Cut Line= 3
  1249206.917544   718682.018943  1248919.131648   718345.852001
  1248653.315409   718042.055084
#Sta/Elev= 30
       0 1225.59    8.94 1228.34   24.69 1230.57      33 1230.21   80.21 1226.44
  112.97 1220.48  181.26 1218.13  250.85 1213.74  261.61 1210.88  272.82 1201.96
  282.93 1201.18  323.36 1201.26  363.67 1196.73  385.98 1195.91   421.4 1191.94
  433.11 1191.63  438.67 1188.52  439.64 1187.22   447.6 1187.22  451.72 1192.72
  622.69 1192.51  638.91 1193.63  678.94  1193.8  700.95 1197.36  730.66 1198.37
  733.36 1198.87  753.22 1209.05  784.18 1211.07  815.14 1232.31   846.2 1245.19
#Mann= 3 , 0 , 0
       0     .08       0  433.11    .048       0  451.72     .08       0
Bank Sta=433.11,451.72
Exp/Cntr=0.5,0.3