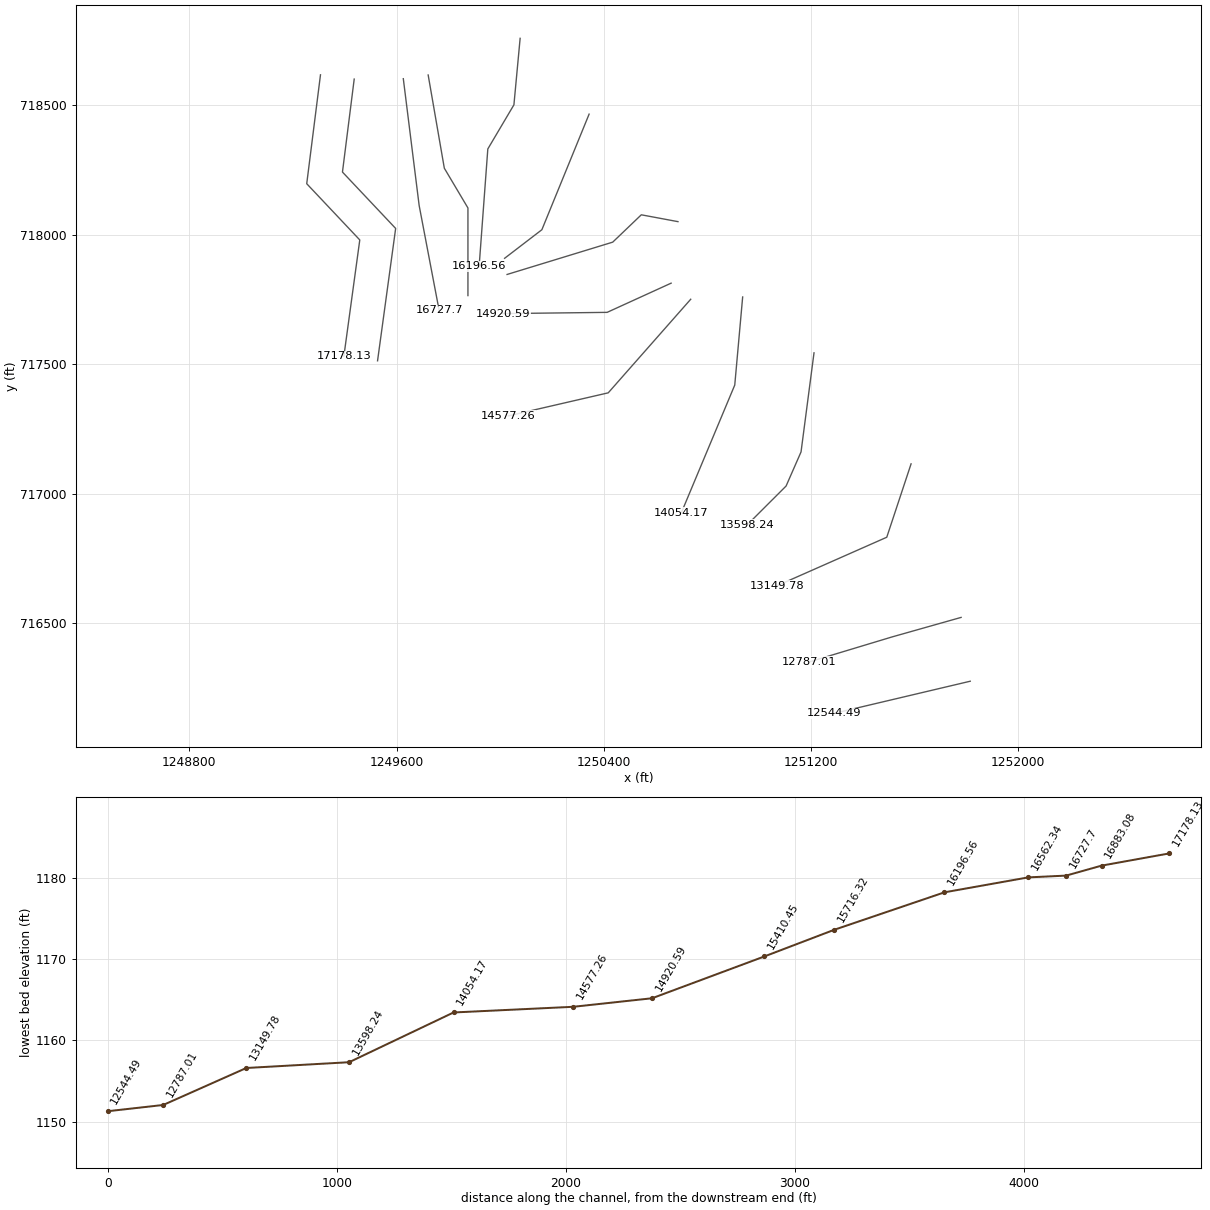
HEC-RAS study CubCreek.prj: CubCreek

--- CubCreek.g01 (geometry) --- (continued)

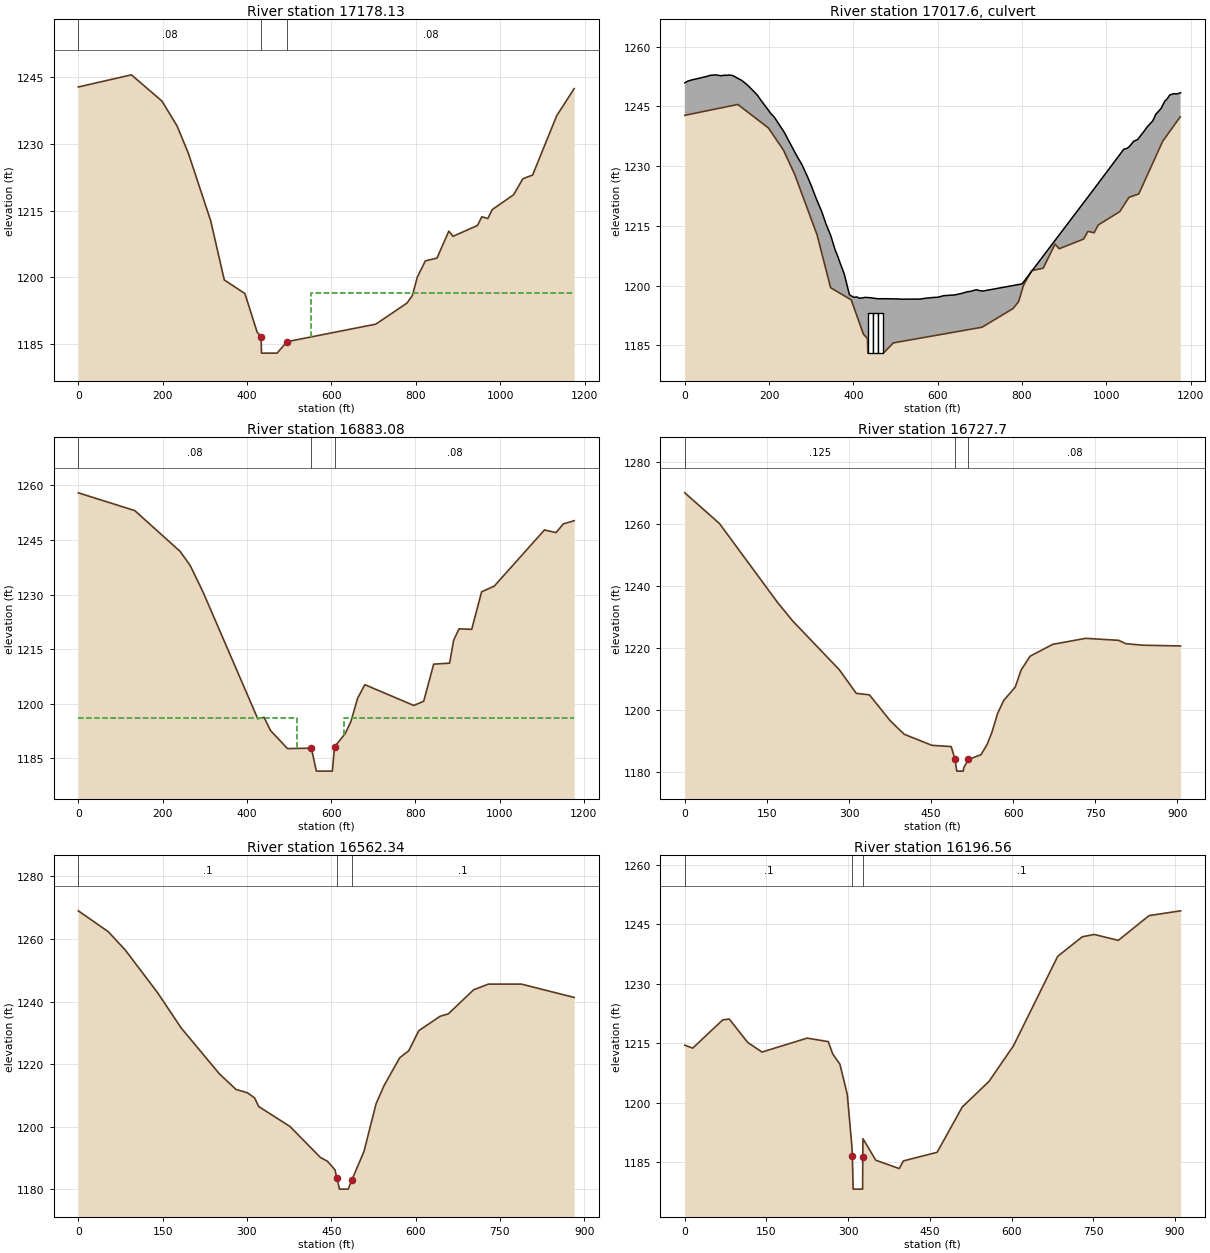
Type RM Length L Ch R = 1 ,17178.13,277.058,295.047,266.081
XS GIS Cut Line= 4
  1249306.145739   718617.346105  1249253.037669   718196.906886
  1249457.867636   717979.787149  1249396.483331   717530.914153
#Sta/Elev= 30
       0 1242.78   125.8 1245.51  198.39  1239.6  234.22    1234  260.84 1227.89
  313.81 1212.72  345.93 1199.44  394.86 1196.38  423.78 1187.74  433.22 1186.68
   434.2    1183   471.2    1183  494.64 1185.57   705.2 1189.51  778.92 1194.23
  791.88 1195.95  803.46 1200.05  822.59 1203.72  850.18 1204.35  878.21  1210.4
  888.19 1209.24  946.15 1211.67  956.33 1213.62  970.94 1213.25  980.89 1215.22
 1031.82 1218.58 1053.84 1222.18 1076.86    1223 1133.85  1236.3 1175.32 1242.41
#Mann= 3 , 0 , 0
       0     .08       0  433.22    .048       0  494.64     .08       0
#XS Ineff= 2 , 0
       0   354.2  1196.6   551.2       0  1196.6
Permanent Ineff=
       F       F
Bank Sta=433.22,494.64
Exp/Cntr=0.5,0.3

Type RM Length L Ch R = 2 ,17017.6 ,,,
BEGIN DESCRIPTION:
Culvert: 3723-169 - Mineral Springs Mountain Road
END DESCRIPTION:
Bridge Culvert--1,0,-1,-1, 0
Deck Dist Width WeirC Skew NumUp NumDn MinLoCord MaxHiCord MaxSubmerge Is_Ogee
80,38,2.6,0, 148, 180, , , 0.95, 0, 0,0,,
       0    1.59    5.36    6.35   14.28   17.68   28.26   28.71   28.87   33.34
   38.93   39.13   40.32   49.45   51.73   60.63   64.85   72.17   79.13   86.62
   93.67  100.86  104.06  108.38  114.04  120.96  125.21  134.73  136.78  146.33
  147.56  152.46  171.73  179.14  180.78  190.47  198.31   201.7  203.11  209.32
  211.66  212.18   214.4  222.64  225.17  233.05  235.99  243.07  247.43  254.85
  262.71  266.41  271.48  277.94  285.14  288.98  290.37  299.66  299.91  310.05
  312.14  324.99  334.17  334.39  334.45  334.61  346.12  353.75  356.48  364.26
  367.69  375.78  378.17  388.55  390.36  392.81  401.03  408.13  414.13   426.8
  427.41  428.91   442.4  449.27  457.82  472.46  473.24   474.8  489.22  498.88
  505.12   514.1  556.55  558.13  571.61  578.65  586.36  600.77   600.9  601.17
   615.1  620.16  629.15   639.3  643.17  654.01     657  658.18  670.59  677.21
  684.19  691.71  694.23  697.71  706.56  800.12  800.14  969.83 1041.36  1048.9
 1052.16  1056.5 1064.61 1071.84 1074.15 1075.24 1079.56 1084.93 1086.34 1096.16
    1097 1097.15 1109.33 1111.47 1117.63 1118.95 1123.98 1130.08 1133.51  1138.9
  1144.4 1150.38 1154.88 1160.18 1166.24  1172.2 1175.67 1176.15
 1250.94 1251.05 1251.27 1251.36  1251.6 1251.71 1251.95 1251.95 1251.96 1252.08
 1252.24 1252.24 1252.27 1252.51 1252.55 1252.84 1252.86 1252.96 1252.84 1252.72
 1252.87 1252.83  1252.9 1252.87 1252.76 1252.36  1252.1 1251.57 1251.41  1250.6
 1250.49 1249.99 1247.92 1246.75 1246.54 1245.19 1244.07 1243.55 1243.35 1242.67
 1242.42 1242.35 1241.99 1240.67 1240.21 1238.97  1238.5 1237.08 1236.17  1234.7
 1233.17 1232.44 1231.55 1230.37 1228.74 1227.85 1227.51 1225.19 1225.12 1222.33
 1221.76 1218.54 1215.68 1215.61 1215.59 1215.55 1212.58 1210.01 1209.01 1206.94
 1205.86 1203.64 1202.93 1198.46 1197.76 1197.52 1197.03 1197.13 1196.78 1196.98
 1196.97 1197.02  1196.9  1196.8 1196.66 1196.68 1196.67 1196.68 1196.65 1196.62
 1196.62 1196.56 1196.58 1196.59  1196.8 1196.88 1196.97 1197.05 1197.06 1197.06
 1197.47 1197.46 1197.57 1197.61  1197.7 1197.93    1198 1198.04 1198.45  1198.5
 1198.71 1198.96 1198.85 1198.76  1198.6 1200.41 1200.41 1224.15 1234.26 1234.47
 1234.72 1235.16 1236.26 1236.57 1236.73 1236.84 1237.42 1238.19 1238.33 1239.78
  1239.9 1239.93 1241.29 1241.71 1243.13 1243.25  1243.8 1244.55 1245.32 1246.38
 1246.94  1247.9 1248.07 1248.25 1248.12  1248.3 1248.43 1248.45
                                                                                
                                                                                
                                                                                
                                                                                
                                                                                
                                                                                
                                                                                
                                                                                
                                                                                
                                                                                
                                                                                
                                                                                
                                                                                
                                                                                
                                                                
       0    1.59    5.36    6.35   14.28   17.68   28.26   28.71   28.87   33.34
   38.93   39.13   40.32   49.45   51.73   60.63   64.85   72.17   79.13   86.62
   93.67  100.86  104.06  108.38  114.04  120.96  125.21  134.73  136.78  146.33
  147.56  152.46  171.73  179.14  180.78  190.47  198.31   201.7  203.11  209.32
  211.66  212.18   214.4  222.64  225.17  233.05  235.99  243.07  247.43  254.85
  262.71  266.41  271.48  277.94  285.14  288.98  290.37  299.66  299.91  310.05
  312.14  324.99  334.17  334.39  334.45  334.61  346.12  353.75  356.48  364.26
  367.69  375.78  378.17  388.55  390.36  392.81  401.03  408.13  414.13   426.8
  427.41  428.91   442.4  449.27  457.82  472.46  473.24   474.8  489.22  498.88
  505.12   514.1  556.55  558.13  571.61  578.65  586.36  600.77   600.9  601.17
   615.1  620.16  629.15   639.3  643.17  654.01     657  658.18  670.59  677.21
  684.19  691.71  694.23  697.71  706.56  800.12  800.14  800.32  824.29  827.13
  835.73  840.79  849.03  851.93  859.04  864.99  882.59   892.3  895.83  899.95
  915.33  923.14  926.12  928.93  937.51  942.17  950.88  968.91  969.19  969.83
  980.08  989.36  993.26  995.89 1003.32 1009.09 1016.62 1020.72 1027.81 1034.01
 1041.36  1048.9 1052.16  1056.5 1064.61 1071.84 1074.15 1075.24 1079.56 1084.93
 1086.34 1096.16    1097 1097.15 1109.33 1111.47 1117.63 1118.95 1123.98 1130.08
 1133.51  1138.9  1144.4 1150.38 1154.88 1160.18 1166.24  1172.2 1175.67 1176.15
 1250.94 1251.05 1251.27 1251.36  1251.6 1251.71 1251.95 1251.95 1251.96 1252.08
 1252.24 1252.24 1252.27 1252.51 1252.55 1252.84 1252.86 1252.96 1252.84 1252.72
 1252.87 1252.83  1252.9 1252.87 1252.76 1252.36  1252.1 1251.57 1251.41  1250.6
 1250.49 1249.99 1247.92 1246.75 1246.54 1245.19 1244.07 1243.55 1243.35 1242.67
 1242.42 1242.35 1241.99 1240.67 1240.21 1238.97  1238.5 1237.08 1236.17  1234.7
 1233.17 1232.44 1231.55 1230.37 1228.74 1227.85 1227.51 1225.19 1225.12 1222.33
 1221.76 1218.54 1215.68 1215.61 1215.59 1215.55 1212.58 1210.01 1209.01 1206.94
 1205.86 1203.64 1202.93 1198.46 1197.76 1197.52 1197.03 1197.13 1196.78 1196.98
 1196.97 1197.02  1196.9  1196.8 1196.66 1196.68 1196.67 1196.68 1196.65 1196.62
 1196.62 1196.56 1196.58 1196.59  1196.8 1196.88 1196.97 1197.05 1197.06 1197.06
 1197.47 1197.46 1197.57 1197.61  1197.7 1197.93    1198 1198.04 1198.45  1198.5
 1198.71 1198.96 1198.85 1198.76  1198.6 1200.41 1200.41 1200.47 1207.77 1207.89
 1208.04 1208.03 1208.12 1207.92  1207.7 1210.86 1220.02 1221.55 1221.85  1221.9
 1222.48 1222.84 1222.94 1223.11 1223.01 1223.62 1223.53 1224.13 1224.11 1224.15
 1225.78 1228.76 1229.98 1230.21 1230.58 1231.05 1231.81 1232.15 1232.83  1233.5
 1234.26 1234.47 1234.72 1235.16 1236.26 1236.57 1236.73 1236.84 1237.42 1238.19
 1238.33 1239.78  1239.9 1239.93 1241.29 1241.71 1243.13 1243.25  1243.8 1244.55
 1245.32 1246.38 1246.94  1247.9 1248.07 1248.25 1248.12  1248.3 1248.43 1248.45
                                                                                
                                                                                
                                                                                
                                                                                
                                                                                
                                                                                
                                                                                
                                                                                
                                                                                
                                                                                
                                                                                
                                                                                
                                                                                
                                                                                
                                                                                
                                                                                
                                                                                
                                                                                
BR Coef=-1 , 0 , 0 ,, 0 ,,,0.8,-1,,0,
WSPro=,,,, 1 ,,,, 0 ,,,, 0 ,,,,-1 ,-1 ,-1 , 0 , 0 , 0 , 0 , 0
Multiple Barrel Culv=2,10,12,38,0.012,0.4,1,8,1,1183,1181.5, 3,Culvert #1  , 0 ,80
   440.2   571.3   452.7   583.8   465.2   596.3
Culvert Bottom n=0.012
BC Design=,, 0 ,, 0 ,,,,,,

Type RM Length L Ch R = 1 ,16883.08,185,155.38,129.66
XS GIS Cut Line= 4
  1249436.344521   718600.899951  1249390.998367   718241.909371
  1249596.394502    718024.18945  1249526.506476   717513.133203
#Sta/Elev= 30
       0 1257.95  133.98 1253.07  241.57 1241.87  265.35 1238.03  296.02 1230.71
  425.92  1195.9  441.03 1196.26     456 1192.68  496.55 1187.69  553.17 1187.81
     565  1181.5     603  1181.5  608.17 1188.18   633.8 1191.85  647.13 1195.17
  662.76 1201.47  680.08 1205.25  796.36 1199.54  819.82  1200.7  843.51 1210.89
  881.34 1211.16  890.93 1217.48  903.77 1220.59  933.77 1220.45  957.33 1230.77
  987.27 1232.32 1106.44 1247.75 1134.03 1247.03 1151.21 1249.41 1176.97 1250.29
#Mann= 3 , 0 , 0
       0     .08       0  553.17    .048       0  608.17     .08       0
#XS Ineff= 2 , 0
       0     520    1196     630       0    1196
Permanent Ineff=
       F       F
Bank Sta=553.17,608.17
Exp/Cntr=0.5,0.3

Type RM Length L Ch R = 1 ,16727.7 ,151.996,165.361,176.314
XS GIS Cut Line= 3
  1249625.934356    718602.42513  1249687.119285   718112.749352
  1249764.279162   717707.765057
#Sta/Elev= 30
       0 1270.02   63.37 1260.11  169.67 1234.62  197.34 1228.65  282.25 1212.97
  313.21 1205.36  337.19 1204.88  374.91 1196.59  400.89 1192.15  451.36  1188.6
  486.64 1188.18  493.48 1184.18  496.85 1180.27  508.62 1180.27  509.66 1181.41
  518.04 1184.02  541.11 1185.57  552.27 1188.89  560.75 1192.64  571.49 1198.92
  582.73  1203.1  603.61 1207.37  614.44  1212.9  630.86 1217.34     672 1221.15
  732.44  1223.1  792.69 1222.45  805.39 1221.38   836.2 1220.88  905.75 1220.64
#Mann= 3 , 0 , 0
       0    .125       0  493.48    .048       0  518.04     .08       0
Bank Sta=493.48,518.04
Exp/Cntr=0.3,0.1

Type RM Length L Ch R = 1 ,16562.34,399.09,365.78,326.26
XS GIS Cut Line= 4
  1249721.932033   718616.679376  1249784.311167   718256.799618
  1249875.480693   718103.250958  1249875.480693   717764.964047
#Sta/Elev= 30
       0 1269.02   53.21 1262.36   83.72 1256.45   141.1 1242.83  182.74 1231.63
  250.63 1216.98  280.51 1211.92  300.97 1210.84  313.57 1209.21  320.91 1206.46
  376.43 1200.09  430.85 1190.15   443.3 1188.96  456.68 1186.19  459.83  1183.7
  464.64 1180.05  480.18 1180.05  486.29 1182.84  508.21 1192.11  529.81  1207.4
  543.81 1213.11  571.81 1222.05  587.82 1224.29  605.67  1230.7  643.67 1235.31
  658.35 1236.09  703.17 1243.77  729.52 1245.59  788.42 1245.59  882.11 1241.33
#Mann= 3 , 0 , 0
       0      .1       0  459.83    .045       0  486.29      .1       0
Bank Sta=459.83,486.29
Exp/Cntr=0.3,0.1

Type RM Length L Ch R = 1 ,16196.56,469.59,480.24,470.29
XS GIS Cut Line= 4
  1250077.013341   718758.232038  1250053.021347   718501.517855
  1249952.255074     718331.1748  1249918.666282   717877.726368
#Sta/Elev= 30
       0 1214.47   14.53 1213.74   69.46 1220.83   81.59 1221.07  115.63 1215.16
  141.76 1212.75  224.76 1216.26  263.53 1215.37  271.54 1212.29   284.8  1209.7
  298.37 1202.07  306.99 1188.72  307.61 1186.66  309.19 1178.21  326.49 1178.21
  326.84 1186.43  327.11 1190.92  350.76 1185.49  393.71 1183.39  401.39 1185.32
  463.32 1187.49  509.39 1198.89  558.74 1205.38  603.39  1214.3  684.72 1236.86
  729.94  1241.8  751.96 1242.37  796.06 1240.89  852.51 1247.13  910.44 1248.33
#Mann= 3 , 0 , 0
       0      .1       0  307.61    .045       0  326.84      .1       0
Bank Sta=307.61,326.84
Exp/Cntr=0.3,0.1

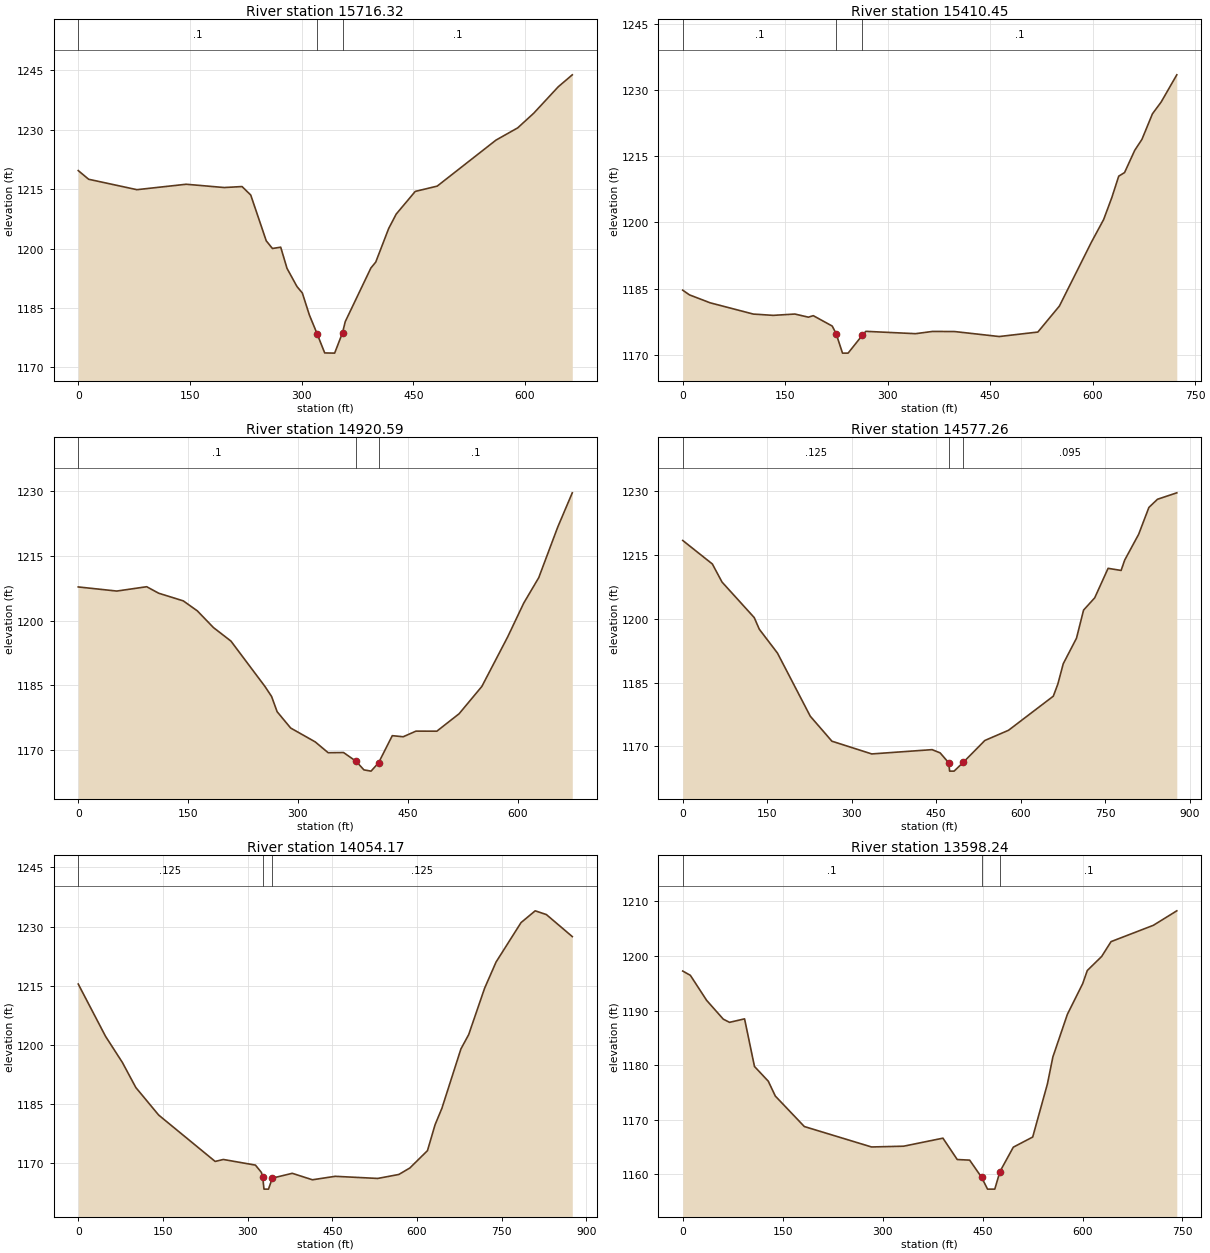
Type RM Length L Ch R = 1 ,15716.32,318.44,305.87,292.95
XS GIS Cut Line= 3
  1250343.324373   718465.529864   1250160.98532    718019.27903
  1250017.033407   717908.915909
#Sta/Elev= 30
       0  1219.7   13.99 1217.51   78.77 1214.88  144.98 1216.25   196.1 1215.42
  219.96 1215.67  231.65 1213.53  252.47 1201.97  260.78 1200.03  271.89 1200.36
  280.37 1195.01  293.74 1190.42  300.92  1188.8   310.4 1183.24  320.67 1178.54
  330.99 1173.66  344.32 1173.61  354.92 1178.76  358.56 1181.56     393  1195.1
  399.52  1196.6  416.88 1205.07  426.97 1208.71  452.56 1214.44  482.07 1215.78
  561.03  1227.4  590.12 1230.48  611.66 1234.18  644.55 1240.85  663.46 1243.88
#Mann= 3 , 0 , 0
       0      .1       0  320.67    .045       0  354.92      .1       0
Bank Sta=320.67,354.92
Exp/Cntr=0.3,0.1

Type RM Length L Ch R = 1 ,15410.45,509.89,489.86,462.39
XS GIS Cut Line= 4
  1250686.409632   718050.468623  1250544.856969   718076.859816
  1250434.493848   717971.295093  1250026.630204   717846.536775
#Sta/Elev= 30
       0 1184.62    9.77 1183.56   40.16 1181.75  103.39 1179.19  132.44  1178.9
  164.09  1179.2  183.89 1178.49  191.08 1178.83  218.85 1176.47  224.52 1174.74
  233.88 1170.32  242.04 1170.32  262.68 1174.34  268.02 1175.27   340.8 1174.74
  365.79 1175.25  398.12 1175.22  463.25 1174.09  519.84 1175.11  551.39 1181.02
  598.45 1195.59   616.1 1200.66  628.13 1205.67  638.23 1210.53  646.75 1211.34
  661.63 1216.39  672.22 1218.89   687.6  1224.7   700.3 1227.36  723.23 1233.55
#Mann= 3 , 0 , 0
       0      .1       0  224.52    .045       0  262.68      .1       0
Bank Sta=224.52,262.68
Exp/Cntr=0.3,0.1

Type RM Length L Ch R = 1 ,14920.59,317.72,343.33,348.84
XS GIS Cut Line= 3
   1250660.01849   717812.947984  1250412.901053   717700.185714
  1250009.835809   717695.387315
#Sta/Elev= 30
       0 1207.78   52.63 1206.83   93.51 1207.83  109.86 1206.33  143.44 1204.56
   162.7 1202.24  184.61 1198.39  208.54 1195.26  255.18 1184.72  264.07 1182.44
  271.63 1178.92   290.1 1175.15  323.66 1171.94   341.3 1169.44  362.34 1169.48
  379.33 1167.47  390.18 1165.47  399.89 1165.18  410.11 1167.09  428.88 1173.38
   443.8 1173.13  461.22 1174.43  489.76 1174.42  520.15 1178.45  551.22 1184.77
  586.38 1196.19  608.44 1204.05  628.92 1209.93  654.85 1221.63  674.72 1229.55
#Mann= 3 , 0 , 0
       0      .1       0  379.33    .045       0  410.11      .1       0
Bank Sta=379.33,410.11
Exp/Cntr=0.3,0.1

Type RM Length L Ch R = 1 ,14577.26,503.81,523.09,553.56
XS GIS Cut Line= 3
  1250735.673125   717750.847823   1250417.20322   717389.486101
  1250031.709272   717300.501547
#Sta/Elev= 30
       0 1218.45   52.58 1212.91   69.73 1208.66  126.93 1200.29  135.93 1197.55
  168.15 1191.94  226.45 1177.06  264.86 1171.18   335.6 1168.18   442.8 1169.19
  457.03 1168.43  472.33 1166.09  473.88 1164.13  481.83 1164.13  498.14  1166.2
  536.46 1171.35   578.5 1173.75  658.03 1181.78   666.1 1184.64  675.64 1189.41
  699.21 1195.44  711.74 1202.05  731.54 1204.94  755.31 1211.89  778.39 1211.39
  784.81 1213.84  809.57  1219.9  827.76 1226.23  842.98 1228.15   877.3 1229.67
#Mann= 3 , 0 , 0
       0    .125       0  472.33    .048       0  498.14    .095       0
Bank Sta=472.33,498.14
Exp/Cntr=0.3,0.1

Type RM Length L Ch R = 1 ,14054.17,445.108,455.932,473.399
XS GIS Cut Line= 3
  1250936.218344    717759.56721   1250905.70062   717419.512218
  1250699.801162   716927.316125
#Sta/Elev= 30
       0 1215.44   48.35 1202.18   78.11 1195.57  102.04 1189.19  142.46 1182.21
  242.51 1170.45  256.92 1170.95  313.83 1169.52  324.43 1167.66  326.73 1166.39
  328.95 1163.43  336.91 1163.43  343.79 1166.22  379.03 1167.44  414.72  1165.8
  455.14 1166.68   530.4 1166.14  567.81 1167.15  587.26 1168.79  618.48 1173.19
  631.95 1179.77     644 1183.92  677.76    1199   691.4 1202.59  719.68 1214.38
  740.06 1221.05  784.17 1231.02  809.25 1234.01   829.1 1233.06  874.95 1227.48
#Mann= 3 , 0 , 0
       0    .125       0  326.73    .048       0  343.79    .125       0
Bank Sta=326.73,343.79
Exp/Cntr=0.3,0.1

Type RM Length L Ch R = 1 ,13598.24,486.7,448.46,405.32
XS GIS Cut Line= 4
  1251211.712005    717543.87389      1251161.61   717161.276761
  1251103.916782   717029.695755  1250953.948166   716879.895786
#Sta/Elev= 30
       0 1197.24   11.42 1196.46    35.9 1191.87   60.87 1188.43   70.24 1187.85
   92.78 1188.49  107.66 1179.77  128.39 1177.07  138.96 1174.35  182.48 1168.77
  283.34 1165.03   331.5 1165.17   390.5 1166.64     412 1162.73  430.63 1162.62
   448.4  1159.5  457.47 1157.31  468.34 1157.31  476.06 1160.52  496.13 1164.99
  525.23 1166.85  547.32 1176.57  555.54 1181.52  577.29 1189.32  600.32 1194.95
  607.18 1197.34  628.71 1199.91  642.85 1202.63  706.36 1205.62  741.51 1208.27
#Mann= 3 , 0 , 0
       0      .1       0   448.4    .045       0  476.06      .1       0
Bank Sta=448.4,476.06
Exp/Cntr=0.3,0.1

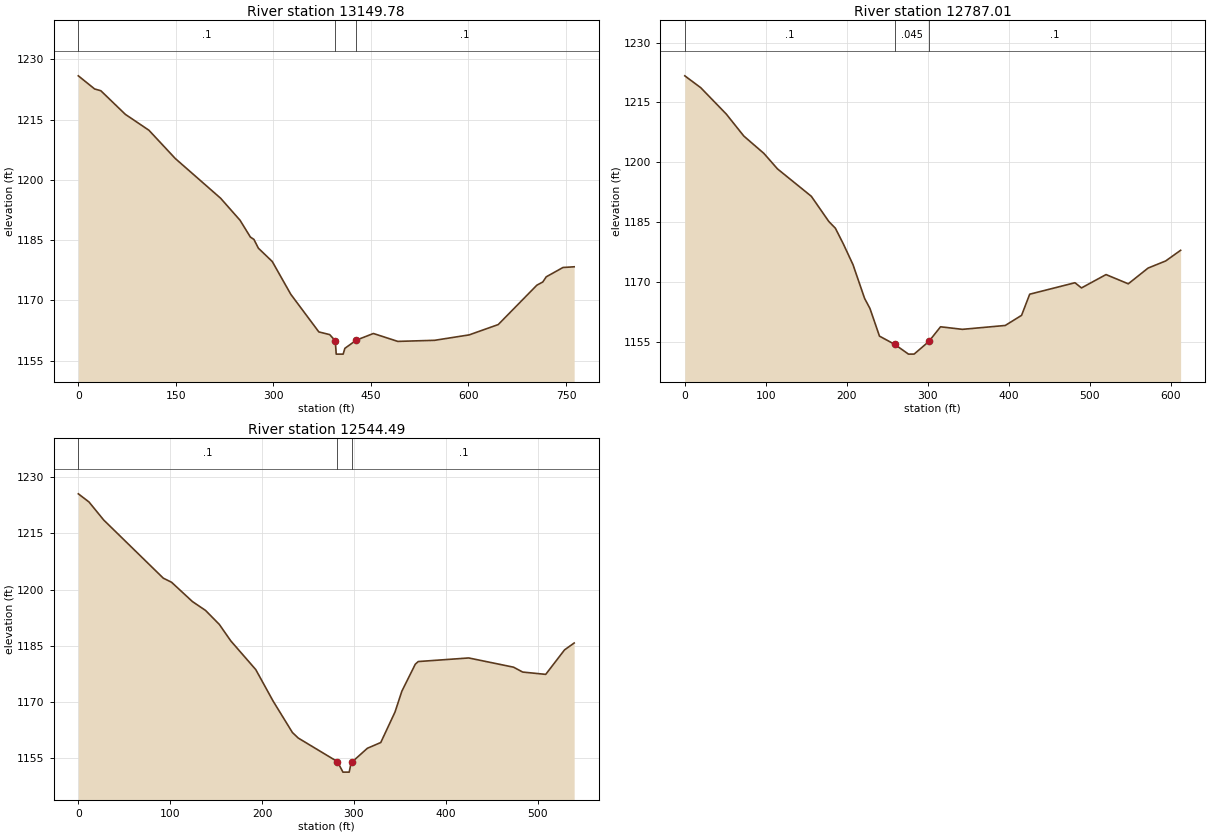
Type RM Length L Ch R = 1 ,13149.78,366.757,362.769,359.1
XS GIS Cut Line= 3
  1251586.506521    717115.29363   1251492.62614   716831.924953
  1251068.174466   716644.305041
#Sta/Elev= 30
       0  1225.9   25.05 1222.63    34.6 1222.19   72.24 1216.32  108.58 1212.35
  149.04 1205.32  218.88 1195.41  248.69 1189.94  264.64 1185.75  270.03 1185.17
   276.9 1182.98  298.24 1179.67  326.77  1171.5  369.92 1162.13  386.62 1161.46
  395.23 1159.91  396.62  1156.6   407.3  1156.6  409.93 1158.04  427.42 1160.07
   453.8 1161.74  491.32 1159.77  547.92 1160.04   601.1 1161.39  645.81 1163.96
  705.18 1173.76  714.31 1174.56  719.65 1175.85  745.35 1178.17  762.58 1178.35
#Mann= 3 , 0 , 0
       0      .1       0  395.23    .045       0  427.42      .1       0
Bank Sta=395.23,427.42
Exp/Cntr=0.3,0.1

Type RM Length L Ch R = 1 ,12787.01,243.77,242.52,240.47
XS GIS Cut Line= 3
  1251779.653173   716522.384294  1251512.533483   716446.844557
  1251192.187434   716350.142998
#Sta/Elev= 30
       0 1221.67   19.64 1218.71    51.2 1212.11    72.9  1206.6   97.68 1202.26
  114.44 1198.39  156.21 1191.54  177.91 1185.21  185.92 1183.55  195.73 1179.63
  207.67 1174.44  222.05 1165.97  228.65 1163.46  240.39 1156.55  259.12  1154.5
   276.2 1152.05  283.17 1152.06  301.37 1155.22  315.78 1158.89   342.8 1158.25
  395.67 1159.22  415.83 1161.75  425.87 1167.04  481.76 1169.91  489.79 1168.61
  520.13 1171.95  547.59 1169.64  572.05 1173.58  593.78 1175.36  612.22 1178.02
#Mann= 3 , 0 , 0
       0      .1       0  259.12    .045       0  301.37      .1       0
Bank Sta=259.12,301.37
Exp/Cntr=0.3,0.1

Type RM Length L Ch R = 1 ,12544.49,145.8,143.75,141.64
XS GIS Cut Line= 2
  1251814.939543   716275.993451  1251289.515129    716151.83501
#Sta/Elev= 30
       0 1225.53   11.56 1223.37   27.61 1218.55   92.51 1203.03  101.56 1201.93
  124.27 1196.78  138.47 1194.43  153.49  1190.7  166.03 1186.29  193.22 1178.63
  212.22 1170.18  233.14 1161.84  239.47 1160.37  282.09 1154.09  288.14 1151.28
  294.95 1151.28  296.99 1153.72   298.4 1154.06   314.7 1157.64  329.31 1159.18
  344.88 1167.35  352.25 1172.86  366.87 1180.06  370.11 1180.78  425.11 1181.74
  473.87 1179.28  483.83 1177.98  508.92 1177.36  529.43  1183.9  539.89 1185.73
#Mann= 3 , 0 , 0
       0      .1       0  282.09    .045       0   298.4      .1       0
Bank Sta=282.09,298.4
Exp/Cntr=0.5,0.3