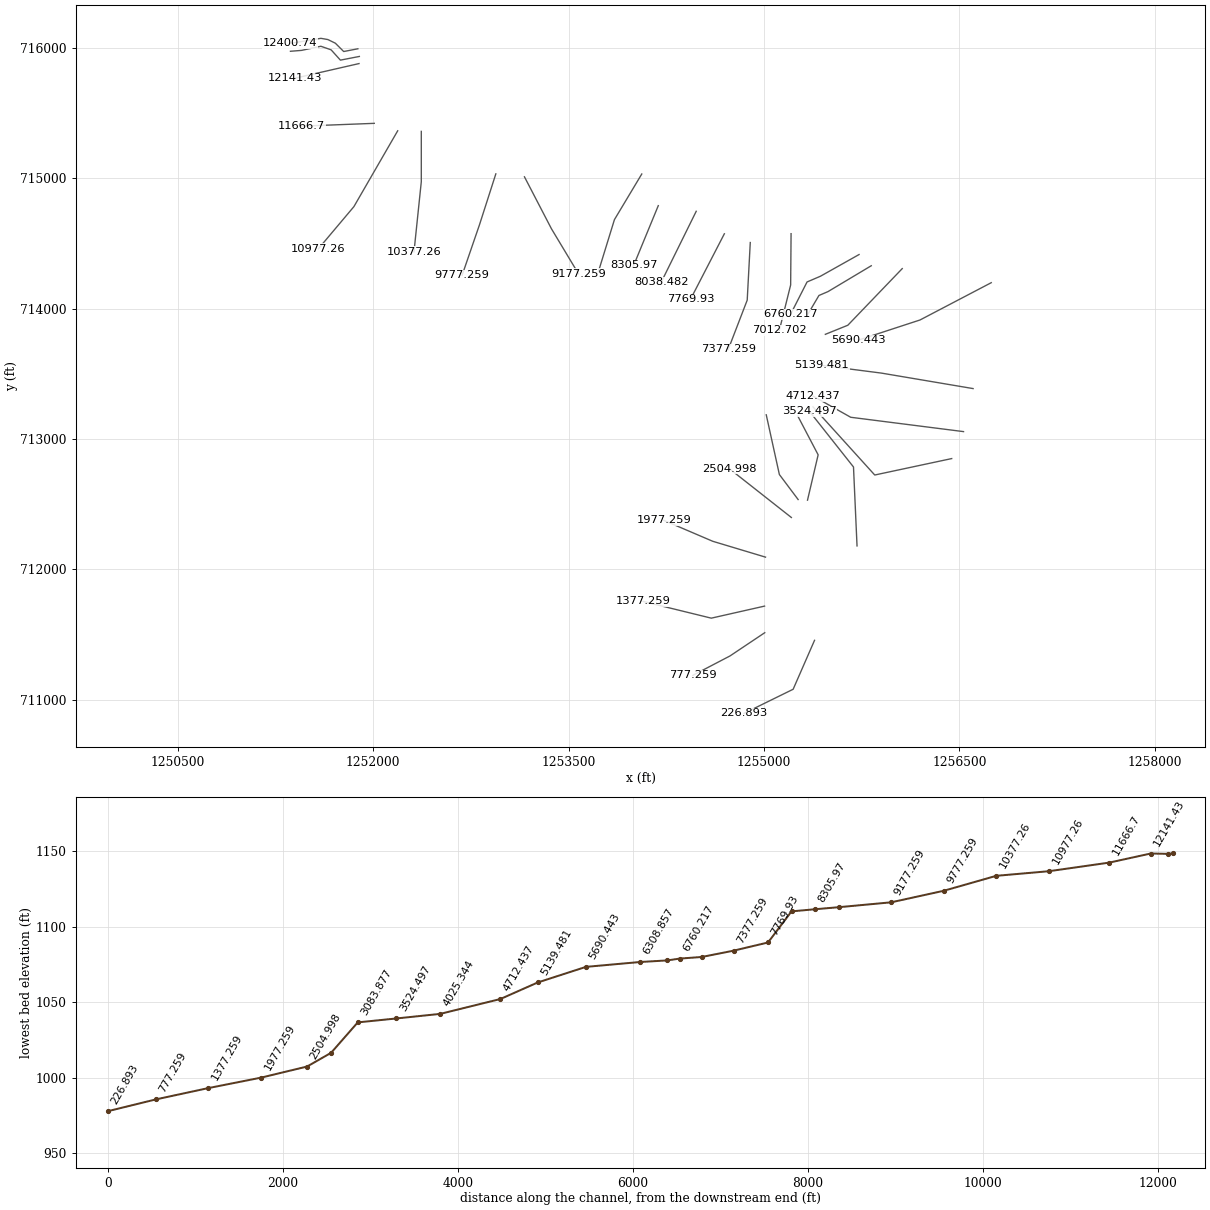
HEC-RAS study CubCreek.prj: CubCreek

--- CubCreek.g01 (geometry) --- (continued)

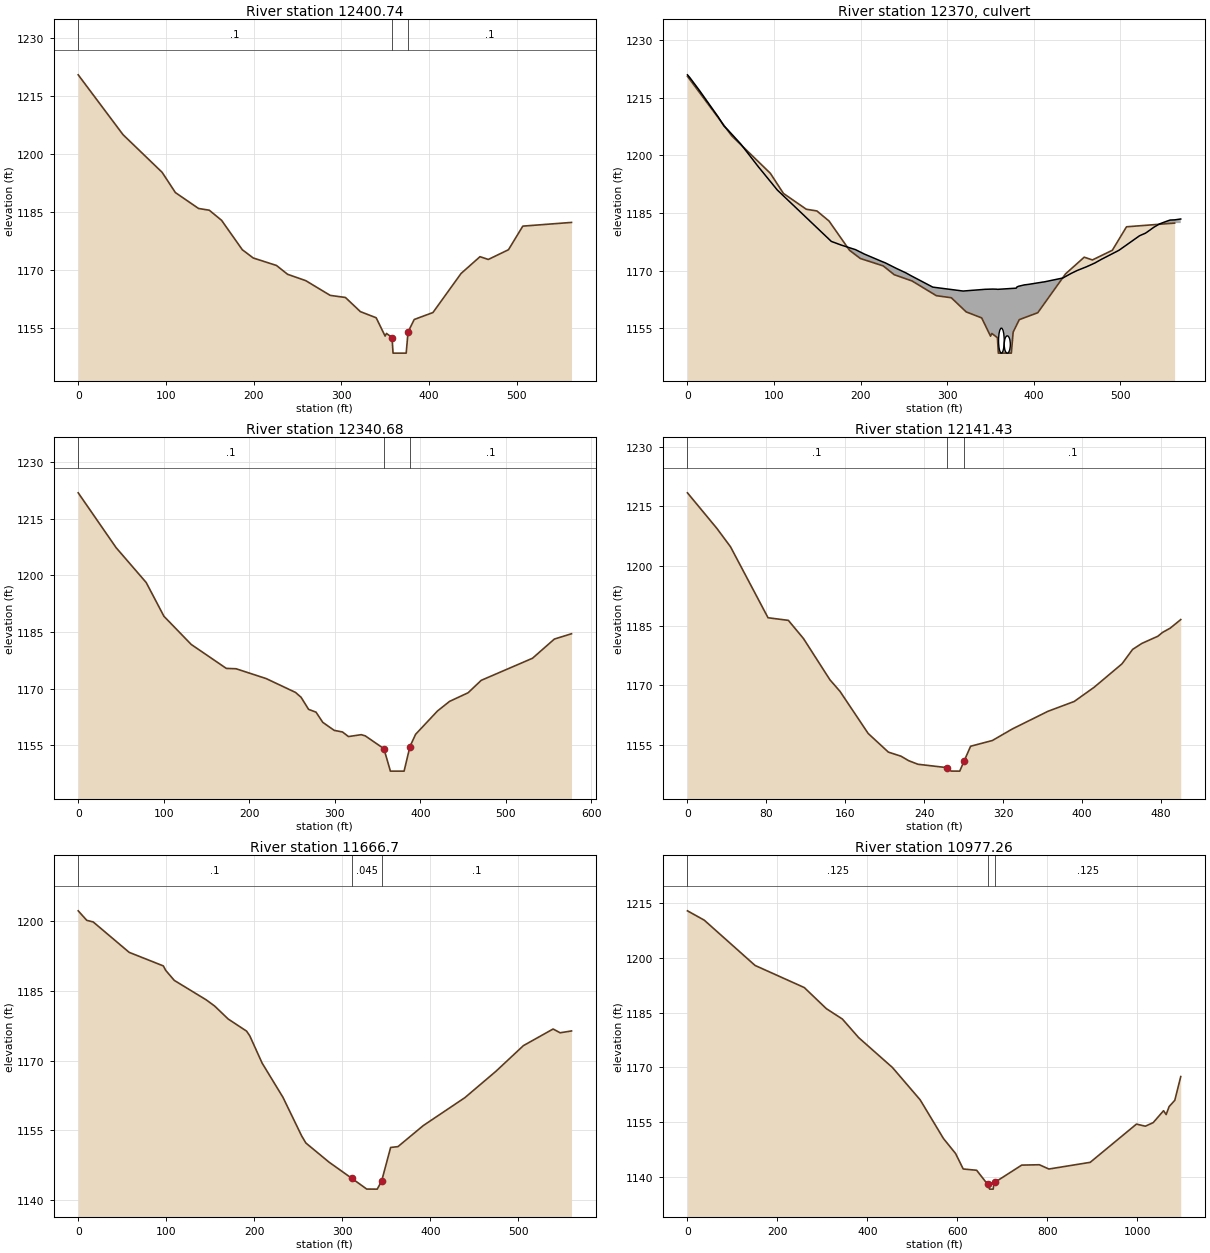
Type RM Length L Ch R = 1 ,12400.74,60.062,60.062,60.059
XS GIS Cut Line= 6
  1251883.445961   715995.460444  1251774.624566   715974.362442
  1251710.778884   716038.171178  1251653.270809   716066.187959
  1251599.972509    716075.59355  1251361.263986   716036.139746
#Sta/Elev= 30
       0 1220.55   51.07 1205.07   95.69 1195.31  110.85 1190.06  137.24 1185.95
  149.48  1185.5   163.5 1182.88  187.13 1175.27   199.6 1173.13  226.05  1171.2
  238.75 1168.91  259.43 1167.27  287.37 1163.45   304.7 1162.91  321.77 1159.24
  339.75 1157.66  349.98 1152.91  351.53  1153.6  357.89 1152.53     359  1148.5
     374  1148.5   376.1 1153.97  383.15 1157.21   404.5 1159.01  436.56 1169.12
  458.16 1173.47  467.62 1172.75  490.62 1175.27  506.97 1181.38   562.5 1182.34
#Mann= 3 , 0 , 0
       0      .1       0  357.89    .045       0   376.1      .1       0
Bank Sta=357.89,376.1
Exp/Cntr=0.5,0.3

Type RM Length L Ch R = 2 ,12370   ,,,
BEGIN DESCRIPTION:
Culvert: Local Driveway
END DESCRIPTION:
Bridge Culvert--1,0,-1,-1, 0
Deck Dist Width WeirC Skew NumUp NumDn MinLoCord MaxHiCord MaxSubmerge Is_Ogee
25,10,2.6,0, 56, 56, , , 0.95, 0, 0,0,,
       0    2.53   14.03   35.53   42.09   46.72   61.28   81.84   99.27  103.67
  166.15  177.36  188.92     194  204.33   224.5  228.44  236.19   241.7  252.32
  258.65   264.7  283.27   318.3  343.64  352.36  357.17  358.05  379.57  380.55
  382.41  389.01  393.69  409.33  409.85  411.45  433.42  443.11  450.03  461.21
  461.85  462.25  462.89  470.48  478.08  498.25  521.99  524.56  528.83  533.56
  538.25  545.09  551.96  557.24  562.81  569.61
 1220.93 1220.27 1216.81 1209.97 1207.63 1206.59    1203 1197.01  1192.2 1190.97
 1177.57 1176.64  1175.8 1175.44 1174.28 1172.35    1172 1171.12  1170.5 1169.38
 1168.59 1167.88 1165.68 1164.66 1165.11 1165.17 1165.14  1165.1 1165.41 1165.73
 1165.91 1166.26 1166.39 1166.96 1166.99 1167.02 1168.05 1169.25 1170.01 1171.01
 1171.09 1171.12 1171.18 1171.96 1172.92 1175.26 1179.04  1179.3 1179.71 1180.45
 1181.22 1182.13 1182.71 1183.13 1183.19 1183.41
                                                                                
                                                                                
                                                                                
                                                                                
                                                                                
                                                
       0    2.53   14.03   35.53   42.09   46.72   61.28   81.84   99.27  103.67
  166.15  177.36  188.92     194  204.33   224.5  228.44  236.19   241.7  252.32
  258.65   264.7  283.27   318.3  343.64  352.36  357.17  358.05  379.57  380.55
  382.41  389.01  393.69  409.33  409.85  411.45  433.42  443.11  450.03  461.21
  461.85  462.25  462.89  470.48  478.08  498.25  521.99  524.56  528.83  533.56
  538.25  545.09  551.96  557.24  562.81  569.61
 1220.93 1220.27 1216.81 1209.97 1207.63 1206.59    1203 1197.01  1192.2 1190.97
 1177.57 1176.64  1175.8 1175.44 1174.28 1172.35    1172 1171.12  1170.5 1169.38
 1168.59 1167.88 1165.68 1164.66 1165.11 1165.17 1165.14  1165.1 1165.41 1165.73
 1165.91 1166.26 1166.39 1166.96 1166.99 1167.02 1168.05 1169.25 1170.01 1171.01
 1171.09 1171.12 1171.18 1171.96 1172.92 1175.26 1179.04  1179.3 1179.71 1180.45
 1181.22 1182.13 1182.71 1183.13 1183.19 1183.41
                                                                                
                                                                                
                                                                                
                                                                                
                                                                                
                                                
BR Coef=-1 , 0 , 0 ,, 0 ,,,0.8,-1,,0,
WSPro=,,,, 1 ,,,, 0 ,,,, 0 ,,,,-1 ,-1 ,-1 , 0 , 0 , 0 , 0 , 0
Culvert=1,6.5,,30,0.027,0.5,1,2,1,1148.5,362.5,1148.2,369.4,Culvert #1  , 0 ,15
Culvert Bottom n=0.027
Culvert=4,4.5,7,30,0.015,0.5,1,29,1,1148.5,369.3,1148.2,376.2,Culvert #2  , 0 ,15
Culvert Bottom n=0.015
BC Design=,, 0 ,, 0 ,,,,,,

Type RM Length L Ch R = 1 ,12340.68,200.852,199.25,201.027
XS GIS Cut Line= 6
  1251894.865925   715936.557298  1251749.362316   715908.347409
  1251678.260046   715987.272078  1251599.620208     716014.7286
  1251450.944149    715983.06852  1251366.010896   715976.327792
#Sta/Elev= 30
       0 1221.88   44.29 1207.37   79.51 1198.13  100.22  1189.2  132.13 1181.74
  173.15  1175.4  184.61  1175.3  219.79  1172.7  254.05 1169.04  260.57 1167.75
  269.38 1164.55  278.06 1163.81  285.97 1161.11  299.32 1158.99  308.94 1158.57
     316 1157.35  330.86 1157.85  335.67 1157.53  357.41 1154.14     365  1148.2
     381  1148.2  387.86 1154.72  394.46 1157.95  420.03 1164.12  434.14 1166.66
  455.86 1168.95   471.2 1172.24  531.11 1178.08  556.72 1183.17  576.73 1184.57
#Mann= 3 , 0 , 0
       0      .1       0  357.41    .045       0  387.86      .1       0
Bank Sta=357.41,387.86
Exp/Cntr=0.5,0.3

Type RM Length L Ch R = 1 ,12141.43,474.47,474.74,468.15
XS GIS Cut Line= 2
  1251892.313647   715881.925179  1251404.676649   715770.362509
#Sta/Elev= 30
       0 1218.43   30.02 1209.43   43.67 1204.86   81.72 1187.01  102.35 1186.35
  117.63 1181.79  144.45 1171.42  154.71 1168.49  183.28  1157.9  203.77 1153.21
  216.62 1152.18  224.31 1151.06  233.72 1150.16  262.78 1149.32  267.38 1148.44
  276.11 1148.43  280.64 1151.02  287.15 1154.69  309.19 1156.13  329.64 1159.06
  365.59 1163.48   392.2 1165.95  412.54 1169.55  440.67 1175.42  451.44 1179.05
  460.85 1180.56  477.03 1182.36  481.79 1183.32  489.58  1184.4  500.24 1186.55
#Mann= 3 , 0 , 0
       0      .1       0  262.78    .045       0  280.64      .1       0
Bank Sta=262.78,280.64
Exp/Cntr=0.3,0.1

Type RM Length L Ch R = 1 ,11666.7 ,658.62,689.44,712.97
XS GIS Cut Line= 2
  1252009.349976   715423.237407  1251449.565881   715401.707252
#Sta/Elev= 30
       0 1202.16    9.73 1200.12   17.05 1199.77    57.9 1193.24   96.69 1190.33
   99.43 1189.36  109.11 1187.22  145.39 1183.04  154.91 1181.72  170.35 1178.92
  191.24 1176.32  194.86 1175.31  208.89 1169.45  232.52 1162.11  253.71 1153.84
  258.52  1152.3  284.75  1148.2  310.92 1144.68  327.66  1142.4  339.56 1142.39
  344.51 1144.08   354.8 1151.34  363.15 1151.52  391.81 1156.03  439.15 1162.04
  474.38  1167.7  505.58 1173.21  539.31 1176.78  547.32 1175.97   560.2 1176.36
#Mann= 3 , 0 , 0
       0      .1       0  310.92    .045       0  344.51      .1       0
Bank Sta=310.92,344.51
Exp/Cntr=0.3,0.1

Type RM Length L Ch R = 1 ,10977.26,583.66,600,617.87
XS GIS Cut Line= 3
  1252189.151807   715366.047872  1251852.892165   714783.944697
  1251579.271051   714459.289955
#Sta/Elev= 30
       0 1212.83   37.36 1210.28  150.35 1197.89  259.79 1191.84  308.91 1186.06
  344.45 1183.23  380.76 1178.14  455.91 1169.96  517.41 1161.13   569.2 1150.55
   596.3 1146.42  613.15 1142.21  643.06 1141.86  667.45 1138.01  671.95  1136.7
  679.89  1136.7  680.97 1138.14  684.38 1138.63  743.17 1143.27   782.4 1143.37
  803.65  1142.2   895.5 1144.03  998.35 1154.49 1018.12 1153.92 1035.52 1154.89
 1058.58 1158.15 1064.41  1157.1 1071.05  1159.3 1083.61    1161 1096.83 1167.49
#Mann= 3 , 0 , 0
       0    .125       0  667.45    .048       0  684.38    .125       0
Bank Sta=667.45,684.38
Exp/Cntr=0.3,0.1

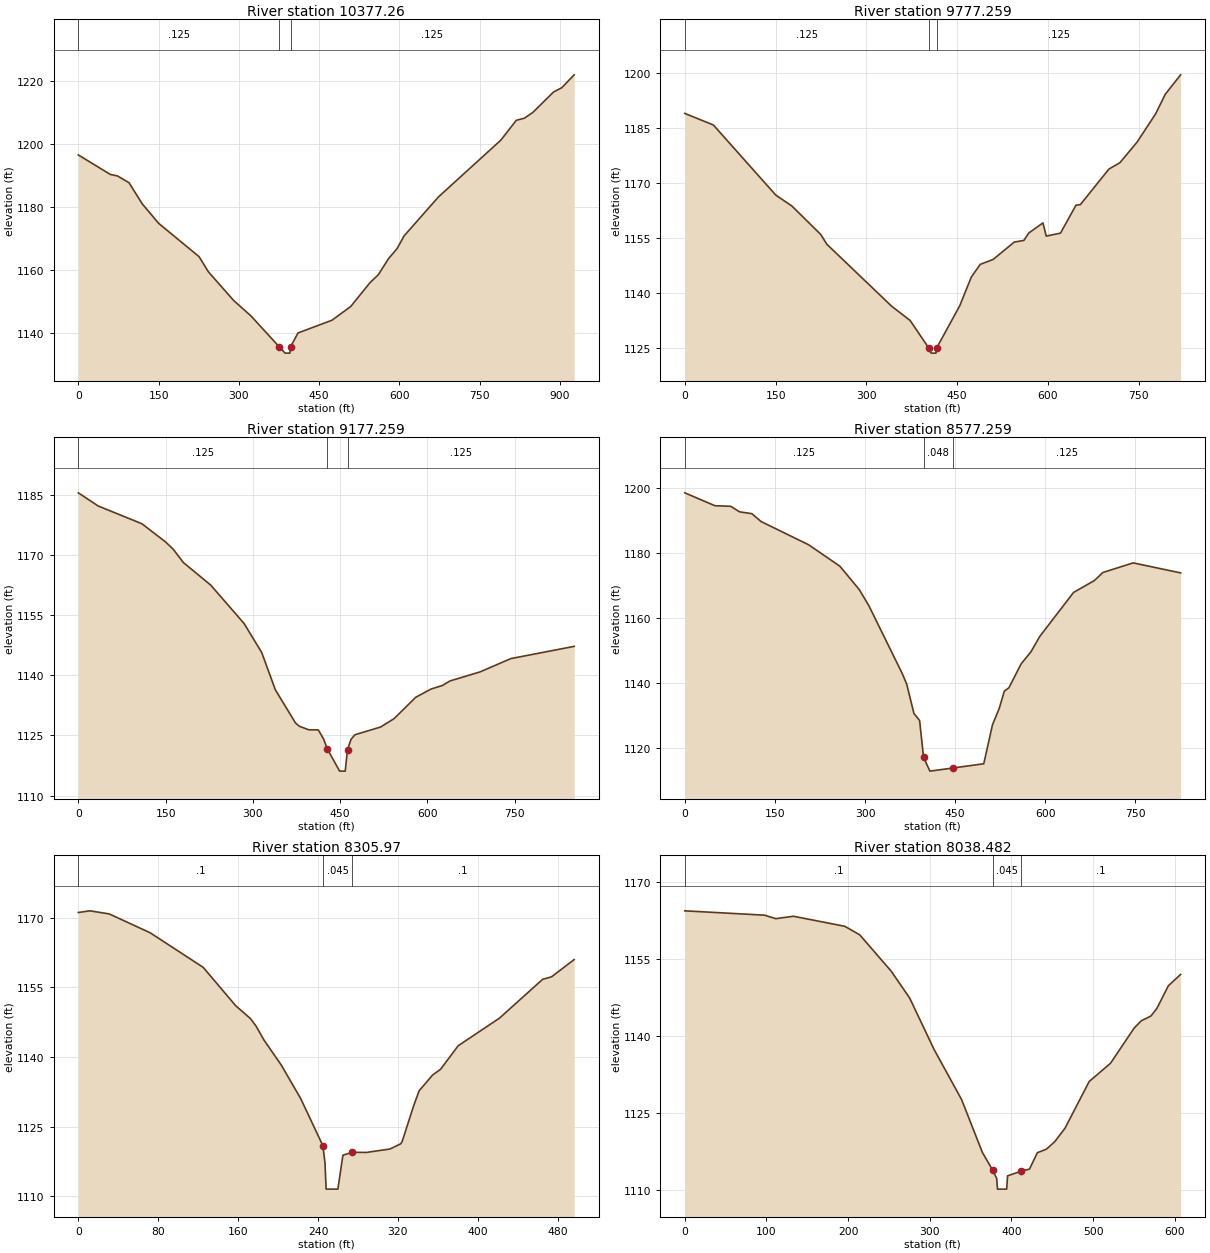
Type RM Length L Ch R = 1 ,10377.26,608.44,600,583.58
XS GIS Cut Line= 3
  1252370.187717   715361.594785  1252370.187717   714975.190796
  1252314.218696   714437.719667
#Sta/Elev= 30
       0 1196.48   59.75  1190.3    73.2 1189.82   94.81 1187.66  119.31    1181
  150.06  1174.8  225.64 1164.24  243.05 1159.44  290.57 1150.29  322.51 1145.48
  375.15 1135.72   386.4 1133.65  395.45 1133.65  396.99 1135.71  410.57 1140.04
  474.15 1144.08   509.3 1148.45  544.56 1155.87  560.93 1158.54  579.73 1163.59
  595.71 1166.77  608.95 1170.82  673.08 1183.16  789.58 1201.14  818.68 1207.46
  833.56 1208.11  849.51 1209.95  888.34 1216.44  903.55 1217.77  926.78 1221.87
#Mann= 3 , 0 , 0
       0    .125       0  375.15    .048       0  396.99    .125       0
Bank Sta=375.15,396.99
Exp/Cntr=0.3,0.1

Type RM Length L Ch R = 1 ,9777.259,577.84,600,626.14
XS GIS Cut Line= 3
  1252942.203361   715035.485314   1252816.97286   714645.622295
  1252683.742629   714258.291975
#Sta/Elev= 30
       0  1188.9   47.24 1185.75  150.35 1166.69     177 1163.72  224.65 1155.98
  234.71 1153.33  341.52 1136.52  372.26 1132.61   403.2  1125.1  406.96 1123.74
  414.92 1123.74  415.93  1125.1  454.18 1136.61  473.25 1144.38  487.98 1147.86
  509.42 1149.21  544.21 1153.92  560.17 1154.38  568.18 1156.38  591.66 1159.14
  597.07 1155.55  620.63 1156.36   646.2 1163.94  653.47 1164.11  700.64 1173.77
  718.65 1175.48  746.93 1181.05  777.67 1188.74  793.82 1194.13  819.09 1199.39
#Mann= 3 , 0 , 0
       0    .125       0   403.2    .048       0  415.93    .125       0
Bank Sta=403.2,415.93
Exp/Cntr=0.3,0.1

Type RM Length L Ch R = 1 ,9177.259,627.81,600,572.89
XS GIS Cut Line= 3
  1253161.777126   715012.971224   1253369.20978    714613.75143
  1253576.450251   714268.853951
#Sta/Elev= 30
       0 1185.47   33.98  1182.2  109.34 1177.76  150.29 1173.19  163.11  1171.4
  180.71 1168.07  227.66 1162.46  284.96 1152.89  315.21 1145.67  338.62 1136.38
  373.32  1128.1   379.8 1127.29  396.04 1126.41  412.49 1126.37  421.52 1124.11
  428.04 1121.62  449.13  1116.1  458.73  1116.1  462.73 1121.44  468.63 1124.01
  475.59 1125.18  519.39 1127.08  542.83 1129.19  579.92  1134.5  605.92 1136.54
  625.64 1137.44  638.93 1138.58  690.44 1140.83   743.5 1144.15  852.27  1147.2
#Mann= 3 , 0 , 0
       0    .125       0  428.04    .048       0  462.73    .125       0
Bank Sta=428.04,462.73
Exp/Cntr=0.3,0.1

Type RM Length L Ch R = 1 ,8577.259,268.034,271.29,268.56
XS GIS Cut Line= 3
  1254062.160233   715034.431084  1253852.395027   714684.362403
  1253729.443225   714285.467058
#Sta/Elev= 30
       0 1198.54   50.16 1194.57   76.44 1194.39    91.1 1192.69  111.66 1192.12
  127.09 1189.69  206.05 1182.56  258.22 1175.95  290.34 1168.78  306.49 1163.79
  361.99 1142.91  369.45 1139.66  381.46 1130.64  390.97 1128.42  397.49  1117.1
   408.1 1112.86  446.47 1113.82  497.76 1115.13  512.17 1127.06  523.43 1132.12
  532.05 1137.49  539.67 1138.53  560.02  1145.9  576.32  1149.6  591.12 1154.35
   647.2 1167.86  681.78 1171.52   696.2 1174.02  746.55 1176.97  825.52 1173.89
#Mann= 3 , 0 , 0
       0    .125       0  397.49    .048       0  446.47    .125       0
Bank Sta=397.49,446.47
Exp/Cntr=0.3,0.1

Type RM Length L Ch R = 1 ,8305.97 ,269.67,267.49,265.297
XS GIS Cut Line= 2
  1254188.894126   714791.557954  1253999.736291   714332.504162
#Sta/Elev= 30
       0 1171.14   11.55  1171.5   30.98 1170.83   71.92 1166.77  125.06 1159.31
  157.58 1151.04  172.31 1148.28  177.84 1146.69  186.12 1143.57  203.19 1138.26
  222.82 1130.96  244.93 1120.84     247 1117.15  248.13  1111.5   259.9  1111.5
  264.95 1118.81  274.19 1119.44  288.48 1119.41  312.07 1120.15  322.68 1121.25
   324.2 1121.72  335.83  1129.5  341.29 1132.71   354.7 1136.09   362.7 1137.33
  380.36 1142.41  421.76 1148.37  464.93 1156.73  473.84 1157.27   496.5 1160.99
#Mann= 3 , 0 , 0
       0      .1       0  244.93    .045       0  274.19      .1       0
Bank Sta=244.93,274.19
Exp/Cntr=0.3,0.1

Type RM Length L Ch R = 1 ,8038.482,268.901,268.553,268.194
XS GIS Cut Line= 2
   1254479.94168   714748.372313    1254211.2315   714203.754406
#Sta/Elev= 30
       0 1164.43   97.79 1163.58  111.49  1162.9  133.15 1163.37  195.94 1161.41
  214.24 1159.75  252.67 1152.68  275.41 1147.41  305.25 1137.39  339.01 1127.59
  364.43 1117.29  376.93 1113.84  381.98 1112.21  383.04  1110.1  394.29  1110.1
  395.31 1112.69  412.08 1113.61  422.15    1114  431.82 1117.21  443.06 1117.91
  453.39 1119.41  465.76 1122.01  495.29 1131.11  521.38 1134.66  550.49 1141.56
  559.06 1142.96  570.89 1143.89  578.15 1145.36  592.29  1149.8   607.3 1152.02
#Mann= 3 , 0 , 0
       0      .1       0  376.93    .045       0  412.08      .1       0
Bank Sta=376.93,412.08
Exp/Cntr=0.3,0.1

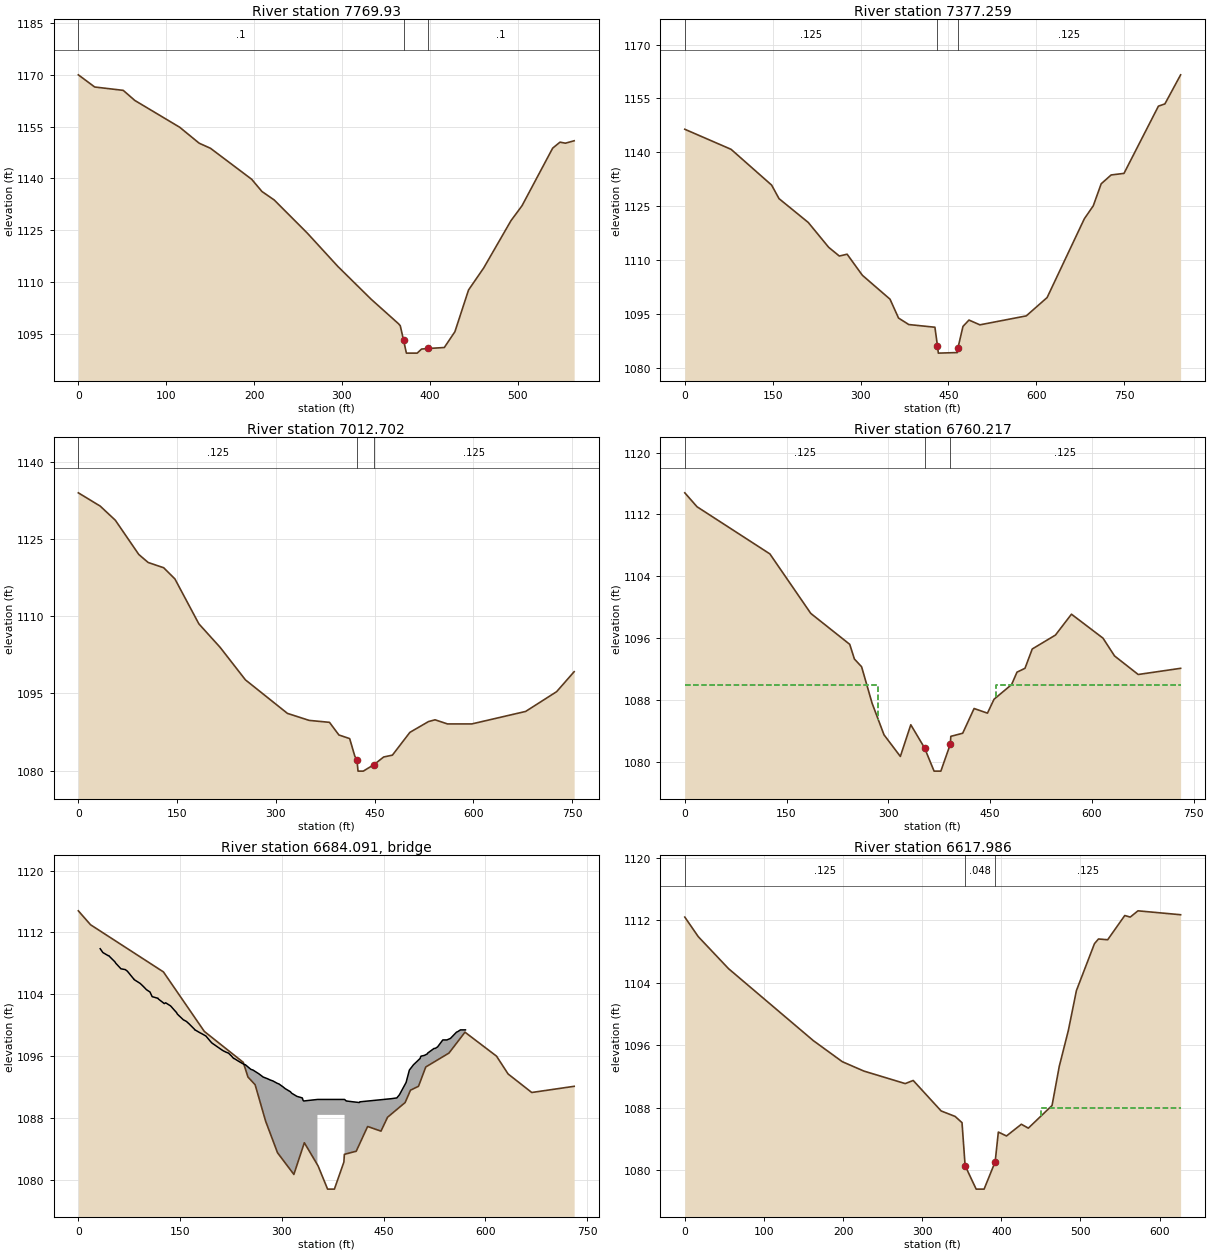
Type RM Length L Ch R = 1 ,7769.93 ,379.82,392.67,395.72
XS GIS Cut Line= 2
  1254695.869473   714575.630058  1254436.756091   714074.197689
#Sta/Elev= 30
       0 1169.96   18.63 1166.44    51.1 1165.47   64.31 1162.55  115.33 1154.81
   137.6 1150.18  150.42 1148.72  197.35 1139.75  209.03 1136.22  222.98 1133.77
  260.72 1124.17  295.35 1114.57  333.39 1105.05  364.43 1097.99  366.46 1097.41
  370.25 1093.21  373.45 1089.48  385.75 1089.48  390.76 1090.66  398.22 1090.82
  416.58  1091.1  428.67 1095.67  444.19 1107.74  461.47 1114.12  492.49 1127.78
  505.06  1132.1  539.97 1148.76  548.31 1150.49  554.46 1150.19  564.42 1150.89
#Mann= 3 , 0 , 0
       0      .1       0  370.25    .045       0  398.22      .1       0
Bank Sta=370.25,398.22
Exp/Cntr=0.3,0.1

Type RM Length L Ch R = 1 ,7377.259,387.65,364.56,348.85
XS GIS Cut Line= 3
   1254894.81151   714508.632016  1254871.307886   714066.525492
  1254726.360117   713689.812697
#Sta/Elev= 30
       0 1146.42   79.03 1140.83   148.2 1130.87  160.89 1127.09  210.78 1120.46
  245.62 1113.54   263.8 1111.11  277.08 1111.62  303.13 1105.75  350.32 1099.09
  364.85 1093.84  382.36 1092.03  426.95 1091.28  431.33 1086.06  432.79 1084.07
  465.27 1084.23  466.36 1085.58  474.85 1091.51  485.08 1093.28  503.72 1091.95
  582.89 1094.44  618.48 1099.55  681.97 1121.48  697.26  1125.1  710.76 1131.23
  727.76 1133.69   749.7 1134.13  808.48 1152.86  819.52 1153.48  846.37 1161.58
#Mann= 3 , 0 , 0
       0    .125       0  431.33    .048       0  466.36    .125       0
Bank Sta=431.33,466.36
Exp/Cntr=0.3,0.1

Type RM Length L Ch R = 1 ,7012.702,263.67,252.49,236.55
XS GIS Cut Line= 3
  1255207.943003    714576.59981  1255204.661203   714182.782659
   1255117.69323   713834.090447
#Sta/Elev= 30
       0 1134.01    33.2 1131.43   56.21 1128.68   91.84 1122.02  106.09 1120.46
  129.62 1119.44  146.68 1117.27  183.09 1108.53  215.37 1103.96  253.84 1097.63
  317.65 1091.11  350.62 1089.75  381.51 1089.37  395.84 1086.91  412.19 1086.21
  419.95 1082.82  423.28 1082.01  424.88 1079.88  432.83 1079.88  448.83 1081.12
  463.85 1082.63  477.12 1082.99  503.66 1087.42  531.94 1089.52  541.89 1089.86
  560.76 1089.06  597.74 1089.06   679.5 1091.49  726.53 1095.33   753.2 1099.22
#Mann= 3 , 0 , 0
       0    .125       0  423.28    .048       0  448.83    .125       0
Bank Sta=423.28,448.83
Exp/Cntr=0.5,0.3

Type RM Length L Ch R = 1 ,6760.217,136.72,142.23,149.46
BEGIN DESCRIPTION:
Upstream xs of Bridge 3723-175
END DESCRIPTION:
XS GIS Cut Line= 4
  1255729.616209   714416.390738  1255433.210408   714249.916257
  1255330.533512   714205.911836  1255203.840727   713957.158278
#Sta/Elev= 30
       0  1114.8      18    1113   125.4  1106.9   185.7  1099.2   243.1  1095.2
     250  1093.3   260.6  1092.3     276  1087.6   293.6  1083.5   317.7  1080.7
   333.1  1084.8   353.4  1081.8   367.4  1078.8   377.4  1078.8   391.4  1082.3
   392.1  1083.3   409.6  1083.7   426.4  1086.9   446.1  1086.3   455.8  1088.1
   481.7    1090   489.6  1091.6   501.4  1092.1   512.1  1094.6   546.3  1096.4
   569.9  1099.1   616.4    1096   633.4  1093.7   668.3  1091.3   730.8  1092.1
#Mann= 3 , 0 , 0
       0    .125       0   353.4    .048       0   391.4    .125       0
#XS Ineff= 2 , 0
       0   285.3    1090   459.2       0    1090
Permanent Ineff=
       F       F
Bank Sta=353.4,391.4
Exp/Cntr=0.5,0.3

Type RM Length L Ch R = 3 ,6684.091,,,
BEGIN DESCRIPTION:
Bridge : 3723-175 --- Nobby Lail Road
END DESCRIPTION:
Bridge Culvert--1,0,-1,-1, 0
Deck Dist Width WeirC Skew NumUp NumDn MinLoCord MaxHiCord MaxSubmerge Is_Ogee
67.1,18,2.6,0, 99, 118, , , 0.95, 0, 0,0,,
    32.2    36.2      44    45.1    45.9    53.9    55.4    62.8    69.1    72.2
    81.5    81.8    82.3    91.3      96   100.4   105.6   108.8   116.6   117.3
   117.9   126.7   128.7     136   145.1   145.5   146.4   154.8   159.2     163
     171   171.5   171.9   179.8   182.1   188.1   194.8   196.9     210   213.4
   218.1   221.2   225.9   228.9   229.6     237   244.9   245.5   246.1   254.2
   257.5   266.4   272.4   278.3   283.3   286.7   292.9   295.8   302.1   304.9
   312.6   313.5   314.6   322.2   330.1   331.2   332.1   352.4   352.4   392.4
   392.4   394.9   395.1   395.2   414.1     415   415.7   461.3   469.4   473.2
   483.1   487.9   494.1   503.7   504.5     505     510   514.5   514.9   524.3
     526   529.5   537.2   543.2   548.5   557.3   559.7   563.2   570.6
  1109.9  1109.4    1109    1109  1108.9  1108.2    1108  1107.3  1107.2    1107
    1106    1106  1105.9  1105.4    1105  1104.6  1104.3  1103.7  1103.5  1103.5
  1103.4  1102.8  1102.9  1102.5  1101.6  1101.5  1101.4  1100.7  1100.5  1100.2
  1099.5  1099.4  1099.4    1099  1098.9  1098.6  1097.9  1097.7  1096.9  1096.7
  1096.5  1096.4    1096  1095.7  1095.7  1095.3  1094.9  1094.9  1094.9  1094.3
  1094.2  1093.7  1093.3  1093.1  1092.9  1092.8  1092.5  1092.4    1092  1091.8
  1091.4  1091.3  1091.2  1090.8  1090.6  1090.3  1090.2  1090.4  1090.4  1090.4
  1090.4  1090.2  1090.2  1090.2    1090  1090.1  1090.1  1090.5  1090.6    1091
  1092.6  1094.2  1094.9  1095.7  1095.9    1096  1096.1  1096.3  1096.4    1097
    1097  1097.2  1098.1  1098.1  1098.3  1099.1  1099.2  1099.4  1099.4
                                                                                
                                                                                
                                                                                
                                                                                
                                                                                
                                                                                
                                                                  1088.4  1088.4
                                                                                
                                                                                
                                                                        
    21.5    25.6    33.4    34.5    35.2    43.3    44.7    52.2    58.4    61.5
    70.9    71.2    71.6    80.7    85.4    89.8    94.9    98.2   105.9   106.6
   107.3     116   118.1   125.3   134.4   134.8   135.8   144.2   148.6   152.4
   160.4   160.8   161.2   169.2   171.5   177.4   184.1   186.2   199.3   202.7
   207.4   210.5   215.2   218.2     219   226.3   234.3   234.9   235.4   243.5
   246.8   255.8   261.8   267.6   272.6   276.1   282.2   285.1   291.4   294.2
     302   302.8   303.9   311.6   319.5   320.6   321.4   336.1   353.3   353.3
   393.3   393.3   394.3   403.4   404.4   405.1   414.1   414.7   426.7   432.4
   450.7   458.7   462.6   472.4   477.2   483.5     493   493.9   494.4   499.4
   503.9   504.3   513.7   515.3   518.8   526.5   532.5   537.9   546.6     549
   552.5   559.9   563.5     570   573.4   580.8     588   592.2     598   603.3
   605.9   614.6   625.1   625.6   626.6   635.5   637.8   644.4
  1109.9  1109.4    1109    1109  1108.9  1108.2    1108  1107.3  1107.2    1107
    1106    1106  1105.9  1105.4    1105  1104.6  1104.3  1103.7  1103.5  1103.5
  1103.4  1102.8  1102.9  1102.5  1101.6  1101.5  1101.4  1100.7  1100.5  1100.2
  1099.5  1099.4  1099.4    1099  1098.9  1098.6  1097.9  1097.7  1096.9  1096.7
  1096.5  1096.4    1096  1095.7  1095.7  1095.3  1094.9  1094.9  1094.9  1094.3
  1094.2  1093.7  1093.3  1093.1  1092.9  1092.8  1092.5  1092.4    1092  1091.8
  1091.4  1091.3  1091.2  1090.8  1090.6  1090.3  1090.2  1089.4  1089.2  1089.2
  1089.2  1089.2  1089.2    1090  1090.1  1090.1  1089.8  1089.9  1089.5  1089.9
  1090.5  1090.6    1091  1092.6  1094.2  1094.9  1095.7  1095.9    1096  1096.1
  1096.3  1096.4    1097    1097  1097.2  1098.1  1098.1  1098.3  1099.1  1099.2
  1099.4  1099.4  1099.5  1099.8    1100  1100.4  1100.7  1100.8  1100.9  1100.9
  1101.1  1101.7    1102    1102  1102.1    1102  1101.9  1102.5
                                                                                
                                                                                
                                                                                
                                                                                
                                                                                
                                                                                
                                                                          1087.2
  1087.2
                                                                                
                                                                                
                                                                                
                                                                
BR Coef=-1 , 1 , 0 ,, 0 ,,,0.8,0,1.2,0,
WSPro=,,,, 1 ,,,, 0 ,,,, 0 ,,,,-1 ,-1 ,-1 , 0 , 0 , 0 , 0 , 0
BC Design=,, 0 ,, 0 ,,,,,,

Type RM Length L Ch R = 1 ,6617.986,303.66,309.13,304.85
BEGIN DESCRIPTION:
Down stream xs of Bridge 3723-175
END DESCRIPTION:
XS GIS Cut Line= 4
  1255823.282259   714330.464097  1255491.356026   714132.058168
  1255421.737929    714102.22187  1255338.303701   713960.746388
#Sta/Elev= 30
       0  1112.4      17  1109.9    55.3  1105.8   162.4  1096.6   199.1  1093.9
   226.4  1092.7   278.6  1091.1   288.7  1091.5     324  1087.6   341.7  1086.9
   350.4  1086.1   354.3  1080.6   368.3  1077.6   378.3  1077.6   392.3  1081.1
   396.3  1084.9   406.6  1084.4   425.4  1085.9   434.2  1085.4   464.2  1088.3
   473.3  1093.3   484.8  1097.9     495    1103   517.8    1109   522.9  1109.6
   534.5  1109.5   556.1  1112.6     563  1112.4   572.8  1113.2   626.7  1112.7
#Mann= 3 , 0 , 0
       0    .125       0   354.3    .048       0   392.3    .125       0
#XS Ineff= 2 , 0
       0   296.2    1088   450.4       0    1088
Permanent Ineff=
       F       F
Bank Sta=354.3,392.3
Exp/Cntr=0.5,0.3

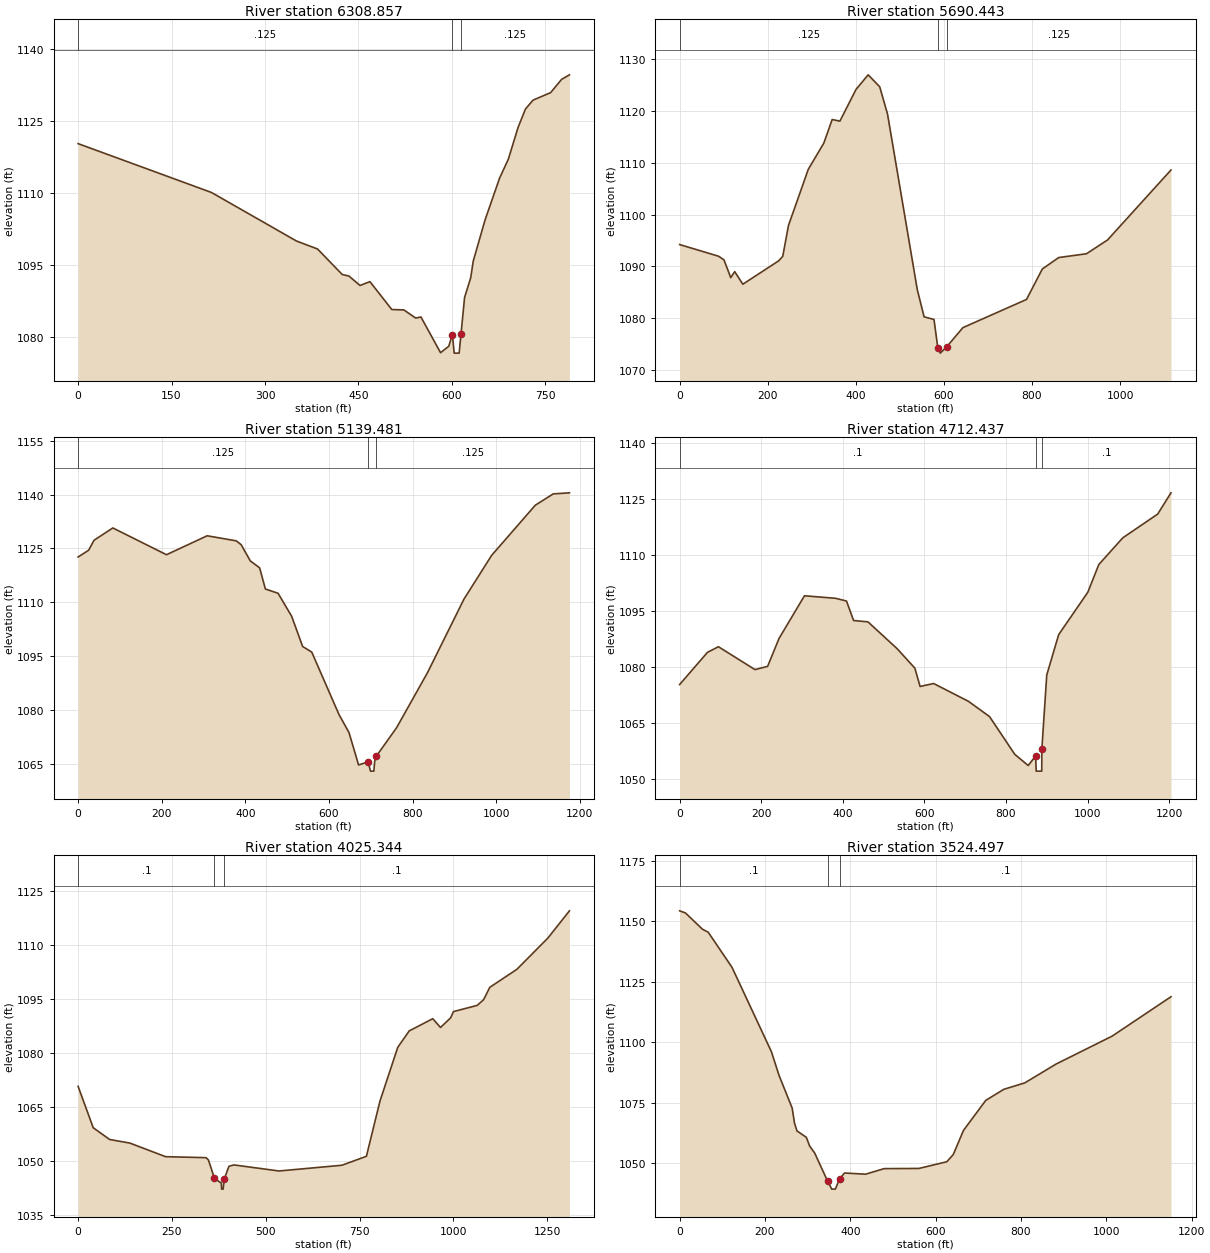
Type RM Length L Ch R = 1 ,6308.857,623.61,618.41,609.67
XS GIS Cut Line= 3
  1256061.061985    714308.53709   1255643.47904   713873.886326
  1255471.039345   713804.176659
#Sta/Elev= 30
       0  1120.3  214.11  1110.1  350.43 1099.97  384.42 1098.29     424 1092.97
  434.76 1092.65  452.54 1090.68  468.45 1091.48  503.53 1085.66  522.99 1085.57
  541.84 1083.88  550.38 1084.09  581.82 1076.64  594.99 1077.98  600.81 1080.44
  603.73 1076.55  611.67 1076.55   614.7 1080.58  620.39 1088.17   630.2 1092.27
  634.35 1095.79  653.41 1104.42  676.58 1113.09  690.65 1117.06  706.26 1123.68
  718.15 1127.54   730.3 1129.38  758.58 1130.96  776.21 1133.73  788.74 1134.67
#Mann= 3 , 0 , 0
       0    .125       0  600.81    .048       0   614.7    .125       0
Bank Sta=600.81,614.7
Exp/Cntr=0.3,0.1

Type RM Length L Ch R = 1 ,5690.443,567.91,550.96,503.13
XS GIS Cut Line= 3
  1256744.157992   714200.421066  1256197.487431    713914.24457
  1255723.755513   713759.519948
#Sta/Elev= 30
       0 1094.22    88.2 1091.98  100.67 1091.28  116.02 1087.85  124.97 1089.02
  143.48 1086.59  224.85 1091.09  234.09 1091.96  247.09 1097.89     292 1108.69
   327.3 1113.74  346.27 1118.28   363.8 1117.97  400.44 1124.08  427.99 1126.88
  454.22 1124.58  471.92 1119.34  539.42 1085.58  554.87 1080.32  577.43  1079.8
  586.01 1074.41  591.68 1073.33  606.12 1074.53  642.99 1078.23  787.47 1083.66
  823.36 1089.52  860.49 1091.72  923.55 1092.45  971.35  1095.1  1115.4 1108.57
#Mann= 3 , 0 , 0
       0    .125       0  586.01    .048       0  606.12    .125       0
Bank Sta=586.01,606.12
Exp/Cntr=0.3,0.1

Type RM Length L Ch R = 1 ,5139.481,433.14,427,413.36
XS GIS Cut Line= 3
   1256604.73866   713387.753131  1255901.657768   713506.522032
  1255443.385398   713565.584628
#Sta/Elev= 30
       0 1122.61   25.13 1124.49   38.14 1127.28   83.07  1130.7  211.37 1123.25
  308.68 1128.52  378.23 1127.11  390.05 1126.03  411.87 1121.52  434.08 1119.61
  447.93  1113.7  478.16 1112.52  510.64 1106.14  537.01 1097.69  558.78 1096.14
  624.12  1078.7  647.84 1073.75   670.8 1064.71  693.68 1065.57  699.36 1062.99
   707.3 1062.99  709.39 1065.78  712.97  1067.1  761.54 1075.05  835.75 1090.43
  922.72 1110.86   989.1 1123.08 1093.43 1137.03 1136.28 1140.18  1175.1 1140.48
#Mann= 3 , 0 , 0
       0    .125       0  693.68    .048       0  712.97    .125       0
Bank Sta=693.68,712.97
Exp/Cntr=0.3,0.1

Type RM Length L Ch R = 1 ,4712.437,669.24,687.09,708.27
XS GIS Cut Line= 3
  1256531.360052   713057.549451  1255665.492633    713167.61731
  1255376.317729   713330.405739
#Sta/Elev= 30
       0 1075.26   68.17 1083.88   95.09  1085.4  184.73 1079.26  215.74 1080.13
  243.62  1087.6  306.05 1099.07   382.4 1098.39  409.07 1097.66  426.55 1092.43
   461.7 1092.07  533.12 1084.89  576.79 1079.64  589.54 1074.73  622.65 1075.53
  707.98 1070.76  759.75 1066.66  821.71 1056.52  854.63 1053.53  872.84 1056.09
  874.22 1052.02  887.79 1052.02  888.14 1057.99  900.09  1077.8  929.31 1088.64
 1000.75 1100.01 1027.74 1107.45 1086.58 1114.62 1172.07 1120.98 1204.68 1126.69
#Mann= 3 , 0 , 0
       0      .1       0  872.84    .045       0  888.14      .1       0
Bank Sta=872.84,888.14
Exp/Cntr=0.3,0.1

Type RM Length L Ch R = 1 ,4025.344,552.612,500.847,446.88
XS GIS Cut Line= 3
  1256440.522735   712850.590779  1255849.981202   712724.485538
  1255376.317729   713247.360809
#Sta/Elev= 30
       0 1070.74   40.25 1059.24   83.97 1055.97  138.02 1054.97  233.19 1051.19
  341.03 1050.92  347.32 1050.27  363.42  1045.2  381.55 1043.85  382.42 1042.18
   386.5 1042.18  389.21 1044.92  401.99 1048.54  415.52  1048.9  535.33 1047.22
  703.02 1048.81   768.3  1051.3  804.35 1066.61   851.8 1081.56  882.35 1086.13
  945.14 1089.53  965.71 1087.08  992.68 1089.76 1000.39  1091.5 1063.76 1093.23
 1080.73 1094.82 1097.11 1098.24 1169.24 1103.24 1251.75 1111.91 1309.37 1119.49
#Mann= 3 , 0 , 0
       0      .1       0  363.42    .045       0  389.21      .1       0
Bank Sta=363.42,389.21
Exp/Cntr=0.3,0.1

Type RM Length L Ch R = 1 ,3524.497,447.566,440.62,431.692
XS GIS Cut Line= 3
  1255714.088317   712180.404098  1255686.967138   712786.000261
  1255348.636086    713213.52773
#Sta/Elev= 30
       0 1154.36   13.59 1153.49   53.55 1146.74   66.93 1145.52  122.71 1130.97
   215.1 1096.03  232.79 1086.31  263.78 1072.65  269.19 1066.49  274.93 1063.25
     297 1060.57  304.55 1057.02  316.49 1054.08  346.61 1042.49   356.5 1039.14
  364.97 1039.15  374.82 1043.38  386.52 1045.82  435.59 1045.32   479.4 1047.63
   560.6  1047.7  626.03 1050.47  641.22 1053.45  665.17 1063.45  717.31 1075.87
  759.62 1080.46  808.91 1083.13  882.73 1090.98 1013.32 1102.46 1151.41 1118.79
#Mann= 3 , 0 , 0
       0      .1       0  346.61    .045       0  374.82      .1       0
Bank Sta=346.61,374.82
Exp/Cntr=0.3,0.1

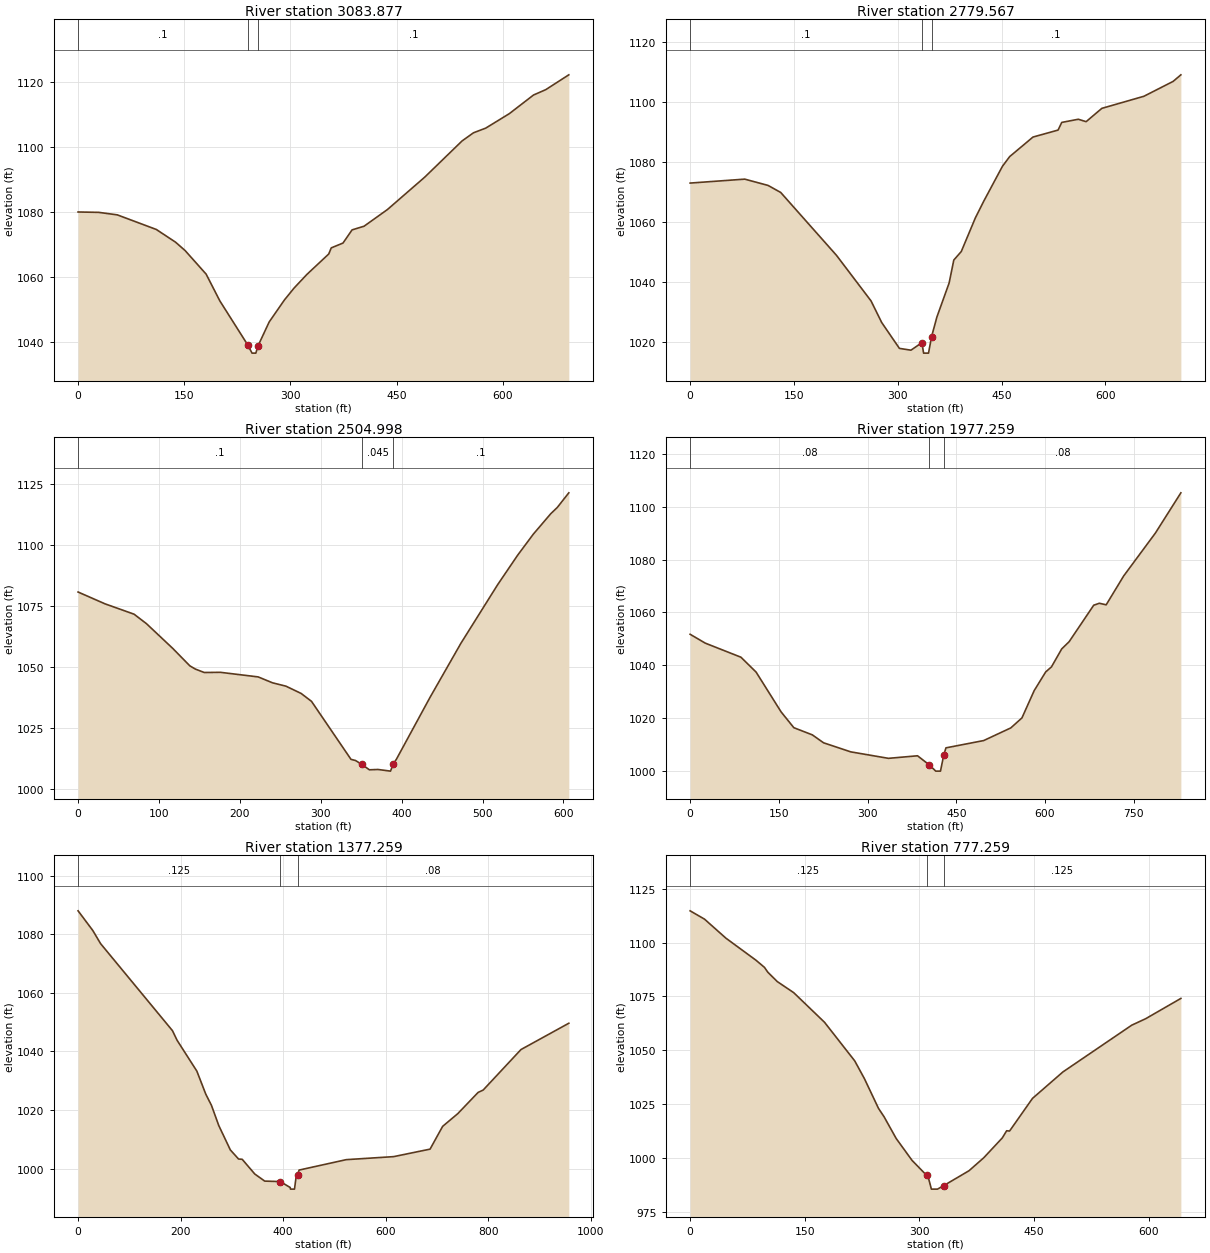
Type RM Length L Ch R = 1 ,3083.877,290.69,304.31,317.64
XS GIS Cut Line= 3
  1255334.056157    712531.51334  1255415.628886    712879.39705
  1255259.681027   713176.897623
#Sta/Elev= 30
       0 1080.07   29.21 1079.95   55.41 1079.18  110.51 1074.68  137.63 1070.77
  151.18 1068.18  180.92  1060.9  200.28 1052.65  239.76 1039.04  245.74 1036.55
  251.12 1036.55  254.05 1038.72  269.96 1046.16  291.55 1052.96  305.24 1056.64
  323.44 1060.86   354.1 1067.12  357.62    1069  374.23 1070.49  387.05 1074.55
  403.98 1075.68  436.93 1080.81  489.54 1090.78  542.36 1101.96  558.49 1104.48
  575.97 1105.94  609.12 1110.38  643.34 1116.13  660.74  1117.8  693.22 1122.36
#Mann= 3 , 0 , 0
       0      .1       0  239.76    .045       0  254.05      .1       0
Bank Sta=239.76,254.05
Exp/Cntr=0.3,0.1

Type RM Length L Ch R = 1 ,2779.567,253.54,274.57,295.26
XS GIS Cut Line= 3
  1255262.080226   712536.311739  1255118.128364   712728.247589
   1255017.36204    713186.49442
#Sta/Elev= 30
       0  1073.1   78.91 1074.41  112.66 1072.31  130.88 1069.97  211.52 1048.99
   261.4 1033.81   276.8 1026.61   302.4 1017.98   319.1 1017.38   334.9 1019.89
  337.35  1016.4  344.48  1016.4  348.81 1021.83  356.54 1028.42  374.26  1039.8
  380.99 1047.43  391.81 1050.28  412.09 1061.46  424.56 1067.19  451.26 1078.68
  461.65 1081.91   495.4 1088.44  531.67 1090.77  536.97 1093.32  560.86 1094.38
  572.18 1093.57  594.91 1098.01  655.71 1102.04  697.92    1107  709.11 1109.19
#Mann= 3 , 0 , 0
       0      .1       0   334.9    .045       0  348.81      .1       0
Bank Sta=334.9,348.81
Exp/Cntr=0.3,0.1

Type RM Length L Ch R = 1 ,2504.998,515.82,527.74,534.93
XS GIS Cut Line= 2
  1255210.227921    712398.45741  1254733.488704   712773.697337
#Sta/Elev= 30
       0 1080.73   33.34 1075.88   69.17 1071.65   84.51 1067.76   117.1 1057.59
  138.27 1050.43  145.23  1049.1  156.01 1047.73  176.02  1047.8  222.67 1045.92
  240.31 1043.51  256.98 1042.13  275.76 1039.14  288.59  1035.9   337.4 1012.12
  343.07 1011.63  350.58 1010.09  360.15 1007.83  370.72 1007.97  386.25 1007.29
  389.86 1010.34  393.54 1012.16  435.17 1037.57  473.33 1059.73  518.77 1083.76
  543.44 1095.82  562.76 1104.43  584.31 1112.81  592.44  1115.4   606.7  1121.4
#Mann= 3 , 0 , 0
       0      .1       0  350.58    .045       0  389.86      .1       0
Bank Sta=350.58,389.86
Exp/Cntr=0.3,0.1

Type RM Length L Ch R = 1 ,1977.259,584.38,600,603.96
XS GIS Cut Line= 3
  1255011.758427   712094.239438  1254607.069291   712215.822376
  1254232.688637   712375.970247
#Sta/Elev= 30
       0 1051.72   25.53 1048.37   85.87 1043.04  111.51 1037.41  153.81 1022.34
  175.36 1016.35  206.58 1013.64  225.63 1010.63  271.67  1007.2  335.33 1004.75
  384.47 1005.72  404.27 1002.29  415.32  999.91  423.27  999.91  428.92 1006.09
  432.53 1008.72  496.34 1011.48  542.18 1016.27  561.02 1020.05  581.68 1030.37
  601.14 1037.45  610.99 1039.39  628.24 1046.17  640.77  1048.9  682.38 1062.72
   691.9 1063.46  703.44 1062.87  733.04  1073.8   786.7 1090.05  829.75 1105.27
#Mann= 3 , 0 , 0
       0     .08       0  404.27    .048       0  428.92     .08       0
Bank Sta=404.27,428.92
Exp/Cntr=0.3,0.1

Type RM Length L Ch R = 1 ,1377.259,576.57,600,645.323
XS GIS Cut Line= 3
  1255004.355903    711718.41911  1254595.576104    711625.97049
  1254073.007605   711754.108961
#Sta/Elev= 30
       0 1088.01   28.59 1081.33      44 1076.79  184.08 1047.11  193.11 1043.83
  231.66  1033.3  249.11 1025.43  260.13 1021.62  274.32 1014.76  296.99  1006.4
  313.03 1003.29  320.07 1003.21  344.65  998.18     364  995.76  394.27   995.6
  413.76  993.58  414.17  993.02  422.12  993.02  425.13  997.02  428.03  997.68
  431.02  999.52  523.05 1003.08  615.47 1004.11  686.53 1006.67  711.03 1014.44
  740.55 1018.78  780.19 1026.02  790.14 1026.84  863.84 1040.66  957.15 1049.64
#Mann= 3 , 0 , 0
       0    .125       0  394.27    .048       0  428.03     .08       0
Bank Sta=394.27,428.03
Exp/Cntr=0.3,0.1

Type RM Length L Ch R = 1 ,777.259 ,531.46,550.37,553.4
XS GIS Cut Line= 3
  1255005.978972   711514.326631  1254739.242621   711336.007329
  1254454.479541   711187.350693
#Sta/Elev= 30
       0 1114.73   18.81 1110.87    46.8 1102.04   85.95 1091.85   97.24 1088.48
  101.59 1086.25  113.93  1081.9  135.49 1076.74  175.88 1062.96  215.39 1045.04
  228.04  1036.8  246.46    1023  253.64 1019.17  269.67 1008.98  290.36  998.85
  309.39  991.92  311.71   990.8  315.67  985.51  323.63  985.51  331.98  987.18
  364.89  994.05  384.22 1000.09  408.37 1009.26  414.13  1012.6  417.98 1012.49
  447.89 1027.62  487.74 1039.92  577.77 1061.63  596.03 1064.64  642.08 1074.06
#Mann= 3 , 0 , 0
       0    .125       0  309.39    .048       0  331.98    .125       0
Bank Sta=309.39,331.98
Exp/Cntr=0.3,0.1

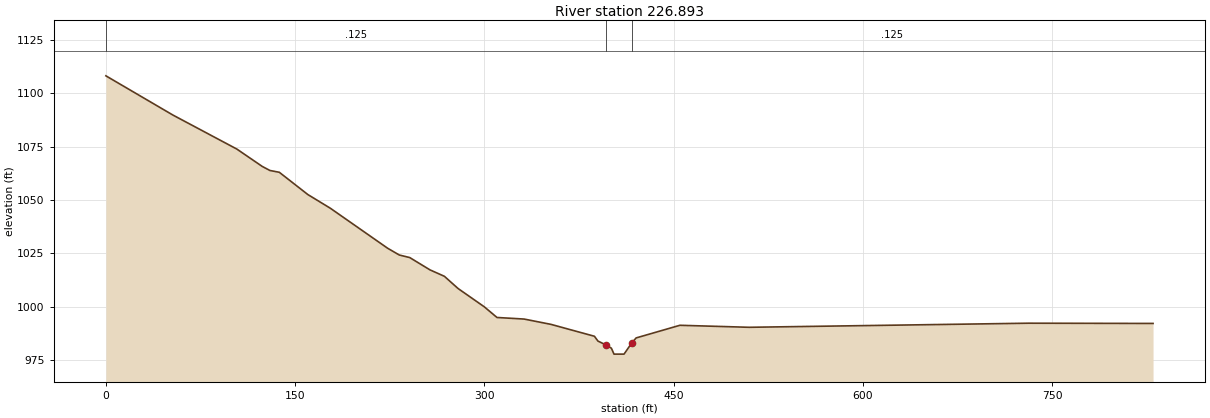
Type RM Length L Ch R = 1 ,226.893 ,223.1,226.89,252.06
XS GIS Cut Line= 3
  1255387.999656   711455.935954  1255223.859114     711080.3798
  1254846.850697   710895.252147
#Sta/Elev= 30
       0 1108.16   52.89 1089.84  103.81 1073.81  123.99 1065.65  130.01 1063.78
  137.45 1062.93  160.06 1052.49   177.9 1046.07  223.31 1027.31  232.54 1024.15
  240.81 1022.95  256.79  1017.2  268.25 1014.17  279.06 1008.46  299.95  999.83
  309.94  994.86  331.46  994.12  352.66  991.64  387.15  986.06  389.93  983.81
  396.68  981.88   400.6  980.45  402.67  977.68  410.62  977.68  416.61   982.8
  420.19  985.27  454.88   991.2  509.75  990.26  731.39  992.18  829.87  992.06
#Mann= 3 , 0 , 0
       0    .125       0  396.68    .048       0  416.61    .125       0
Bank Sta=396.68,416.61
Exp/Cntr=0.3,0.1

Chan Stop Cuts=-1
Use User Specified Reach Order=0
User Specified Reach Order=CubCreek        ,Main