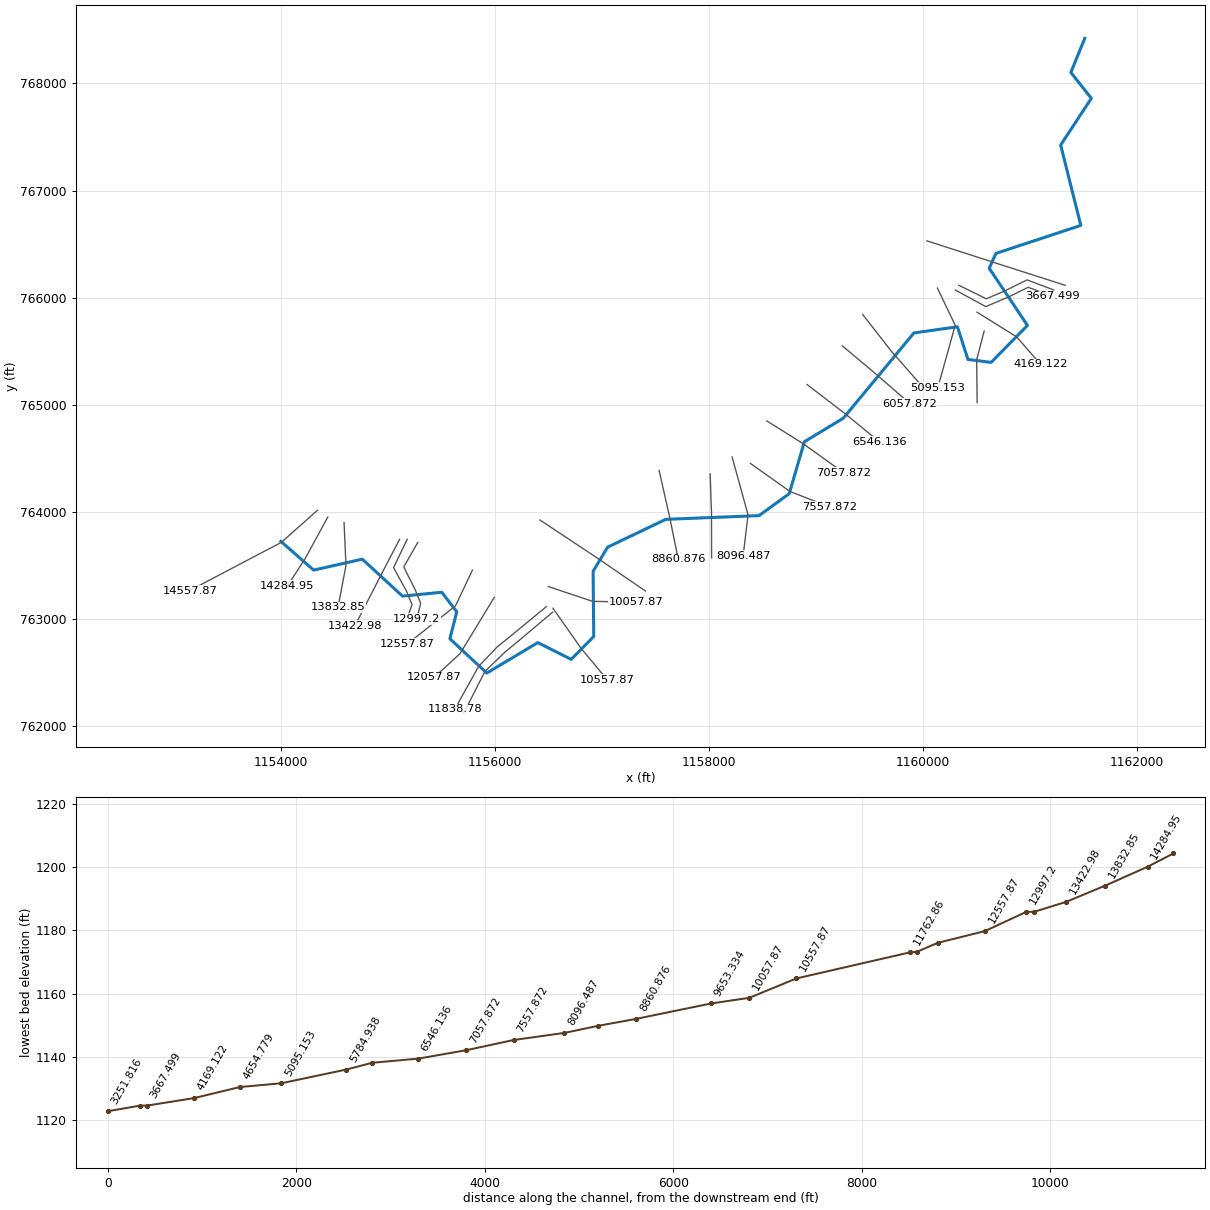
--- russell.prj (project) ---

Proj Title=RussellCreek
Current Plan=p01
Default Exp/Contr=0.3,0.1
English Units
Geom File=g01
Flow File=f01
Plan File=p01
Y Axis Title=Elevation
X Axis Title(PF)=Main Channel Distance
X Axis Title(XS)=Station
BEGIN DESCRIPTION:
END DESCRIPTION:
DSS File=dss
DSS Export Rating Curves= 0
DSS Export Rating Curve Sorted= 0
DSS Export Volume Flow Curves= 0
DXF OffsetX= 0
DXF OffsetY= 0
DXF ScaleX= 1
DXF ScaleY= 10

--- russell.p01 (plan) ---

Plan Title=RussellCreek
Program Version=3.12
Short Identifier=RussellCreek
Geom File=g01
Flow File=f01
Subcritical Flow
K Sum by GR= 0
Std Step Tol= 0.01
Critical Tol= 0.01
Num of Std Step Trials= 20
Max Error Tol= 0.3
Flow Tol Ratio= 0.001
Split Flow NTrial= 30
Split Flow Tol= 0.02
Split Flow Ratio= 0.02
Log Output Level= 0
Friction Slope Method= 1
Unsteady Friction Slope Method= 2
Unsteady Bridges Friction Slope Method= 1
Parabolic Critical Depth
Global Vel Dist= 0 , 0 , 0
Global Log Level= 0
CheckData=True
Encroach Param=-1 ,0,0, 2
Encroach River=RussellCreek
Encroach Reach=Main
Encroach Node=14557.87
       1     395     495
Encroach Node=14284.95
       1388.8116     480
Encroach Node=13832.85
       1 381.425  444.69
Encroach Node=13422.98
       1     350     410
Encroach Node=13080.22
       1     460     650
Encroach Node=12997.2
       1  465.58     660
Encroach Node=12557.87
       1     356     470
Encroach Node=12057.87
       1     408     705
Encroach Node=11838.78
       1     400     877
Encroach Node=11762.86
       1     400     866
Encroach Node=10557.87
       1     380     476
Encroach Node=10057.87
       1     416     485
Encroach Node=9653.334
       1     660     745
Encroach Node=8860.876
       1442.7252     508
Encroach Node=8448.592
       1     325 396.175
Encroach Node=8096.487
       1     520     600
Encroach Node=7557.872
       1426.8303     495
Encroach Node=7057.872
       1346.3482     435
Encroach Node=6546.136
       1     419     490
Encroach Node=6057.872
       1     320     473
Encroach Node=5784.938
       1     385     505
Encroach Node=5095.153
       1370.0807     475
Encroach Node=4654.779
       1243.1342302.2703
Encroach Node=4169.122
       1     400456.2384
Encroach Node=3667.499
       1     470     600
Encroach Node=3596.973
       1     430     560
Encroach Node=3251.816
       1610.8092 716.875
Encroach Node=2767.285
       1 440.515 493.215
Encroach Node=2521.348
       1 390.875 443.825
Encroach Node=2093.615
       1 390.986566.9318
Encroach Node=1798.582
       1 353.411  502.15
Encroach Node=1444.714
       1279.5883 401.615
Encroach Node=1298.291
       1 452.745 607.892
Encroach Node=983.267
       1     380463.1927
Encroach Node=515.246
       1     451     525
Encroach Node=426.391
       1     430     515
Encroach Node=284.171
       1     512     565
Computation Interval=1HOUR
Output Interval=1HOUR
Run HTab= 0
Run UNet= 0
Run PostProcess= 0
UNET Theta= 1
UNET Theta Warmup= 1
UNET ZTol= 0.02
UNET ZSATol= 0.05
UNET MxIter= 20
UNET MaxInSteps= 0
UNET DtIC= 0
UNET DtMin= 0
UNET MaxCRTS= 20
UNET WFStab= 2
UNET SFStab= 1
UNET WFX= 1
UNET SFX= 1
UNET DSS MLevel= 4
UNET DZMax Abort= 100
UNET Convert EG Bridges=-1
UNET Use Existing IB Tables=-1
UNET Froude Reduction=False
UNET Froude Limit= 1
UNET Froude Power= 10
Instantaneous Interval=1HOUR
DSS File=dss
Write IC File= 0
Echo Input=False
Echo Output=False
Write Detailed= 0
Detailed Automatic Start=False, 10

--- russell.f01 (steady flow) ---

Flow Title=RussellCreek
Program Version=3.12
Number of Profiles= 2
Profile Names=P100yr,encr
River Rch & RM=RussellCreek,Main            ,14557.87
    1730    1730
River Rch & RM=RussellCreek,Main            ,13422.98
    1900    1900
River Rch & RM=RussellCreek,Main            ,10557.87
    2070    2070
River Rch & RM=RussellCreek,Main            ,8096.487
    2250    2250
Boundary for River Rch & Prof#=RussellCreek,Main            , 1
Up Type= 0
Dn Type= 3
Dn Slope=0.005
DSS Import GetInterval= 0
DSS Import GetPeak= 0
DSS Import FillOption= 0

--- russell.g01 (geometry) ---

Geom Title=RussellCreek
Program Version=3.12

River Reach=RussellCreek    ,Main
Reach XY= 30
  1153999.882319   763727.029836   1154306.38074   763458.998086
   1154761.13092   763561.307972  1155136.127935   763216.498487
  1155503.756225   763252.498213  1155643.880381   763070.631764
  1155579.495312    762818.69088  1155924.251521   762498.498393
  1156401.632193   762782.691154  1156713.251784   762626.309943
  1156923.880351   762839.752486   1156918.12957   763448.311638
  1157053.629349   763673.309018  1157597.381521   763932.880712
  1158468.379544   763967.500087  1158750.999497    764172.30832
    1158892.3811   764656.881463  1159255.749506   764876.058434
  1159916.250004    765672.12834  1160322.880458   765729.689424
  1160421.000087   765425.000294  1160637.629385   765397.311305
  1160977.494989   765742.251832  1160620.000193   766276.001626
  1160682.881934   766414.499625  1161476.248484   766675.500874
  1161287.754652   767425.630016  1161574.630346   767861.440356
  1161382.876061   768103.190326  1161513.128881   768421.191493

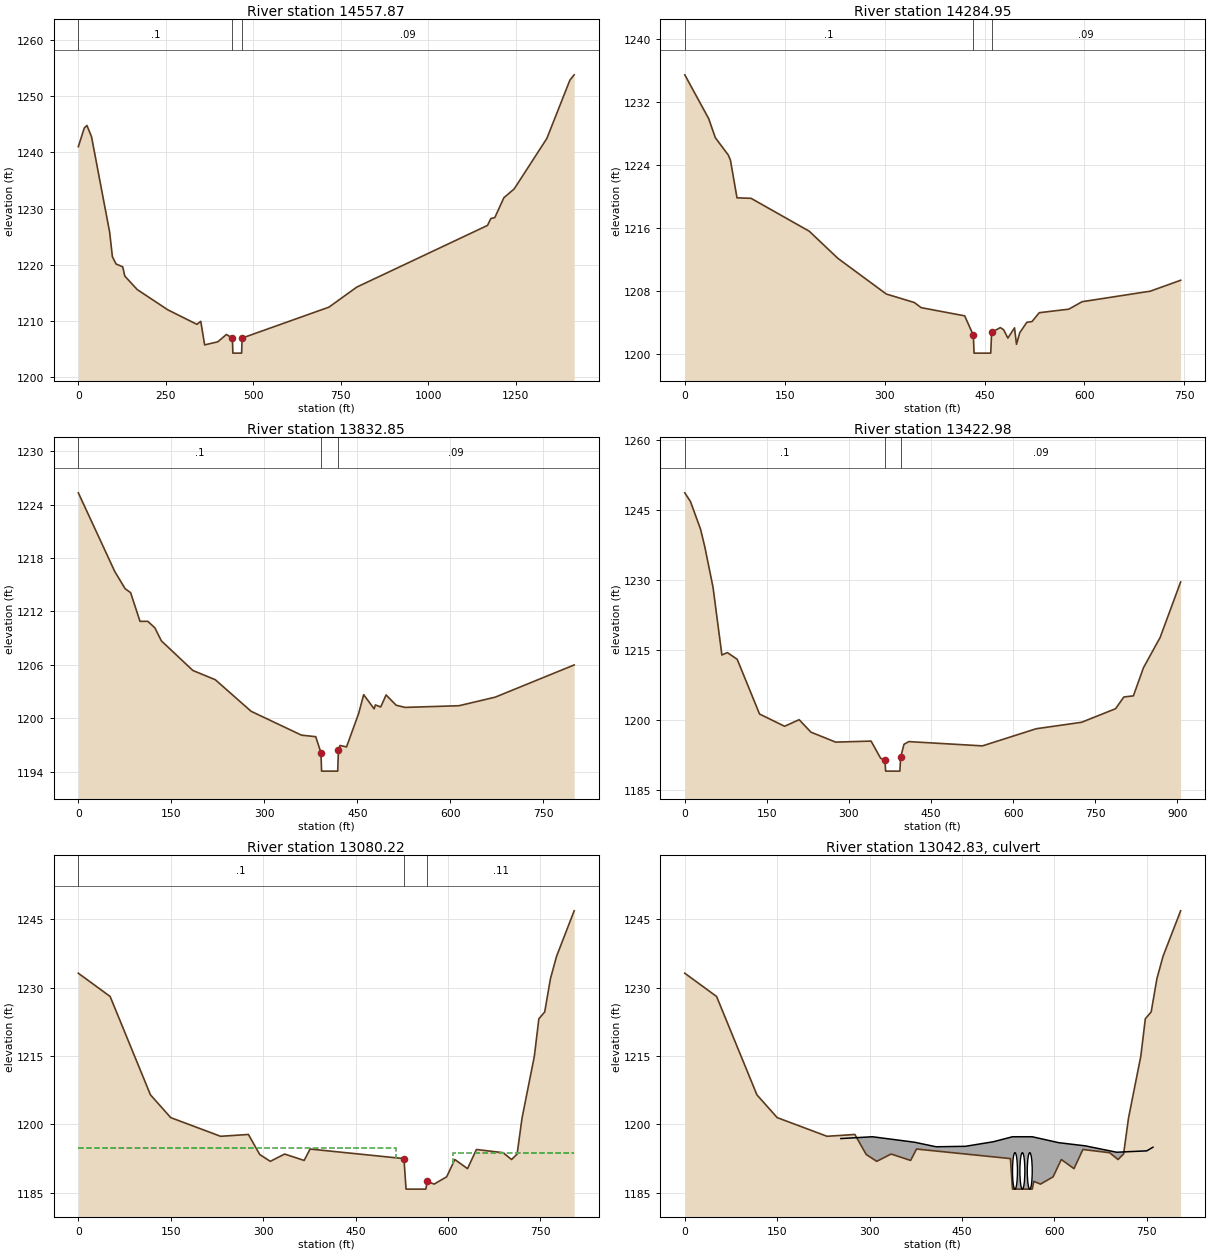
Type RM Length L Ch R = 1 ,14557.87,250.6,272.93,299.19
XS GIS Cut Line= 3
  1154341.235859    764017.20779  1154004.730304   763718.283573
   1153147.98929   763268.716791
#Sta/Elev= 30
       0 1241.03   16.95 1244.35   24.64  1244.8   37.72  1242.8   89.65 1225.76
   97.39 1221.43  107.83 1220.13  126.94 1219.62  132.89 1217.97  168.44 1215.57
  255.87 1211.96  339.03 1209.38  350.07 1209.91  361.14 1205.72  398.54 1206.26
   423.4 1207.57  440.54 1206.92  441.88 1204.25  466.88 1204.25  468.22 1206.93
  716.58 1212.44  796.07 1216.01 1169.94    1227 1179.37 1228.22 1190.75 1228.39
 1216.69 1231.93  1246.2  1233.5 1339.59 1242.49 1405.47 1252.88 1417.63 1253.82
#Mann= 3 , 0 , 0
       0      .1       0  440.54    .052       0  468.22     .09       0
Bank Sta=440.54,468.22
Exp/Cntr=0.3,0.1

Type RM Length L Ch R = 1 ,14284.95,382.45,452.1,467.71
XS GIS Cut Line= 3
  1154438.247065   763954.273069  1154225.844723    763564.62466
  1154061.782239   763312.671493
#Sta/Elev= 30
       0  1235.5   35.87 1229.92   45.85 1227.49   65.41 1225.27   68.51 1224.64
    78.4 1219.83   99.49 1219.77  186.84 1215.58  229.76 1212.13  302.49 1207.58
  344.54  1206.5  354.97 1205.84  420.24  1204.8   433.2 1202.33  434.34 1200.05
  459.34 1200.05  460.66 1202.69  473.68  1203.3  478.69 1203.03  485.08 1201.97
  495.06 1203.27     498 1201.17  502.85 1202.64  513.56 1203.98  521.29 1204.07
  532.21  1205.2  576.62 1205.65  596.55  1206.6   698.9 1207.94  744.44 1209.33
#Mann= 3 , 0 , 0
       0      .1       0   433.2    .052       0  460.66     .09       0
Bank Sta=433.2,460.66
Exp/Cntr=0.3,0.1

Type RM Length L Ch R = 1 ,13832.85,416.11,409.87,350.92
XS GIS Cut Line= 3
  1154590.590816   763903.003511  1154608.168952   763501.636368
  1154533.461928   763110.523034
#Sta/Elev= 30
       0 1225.33   58.72  1216.5   75.49 1214.56   84.37 1214.11   99.52 1210.89
  112.14 1210.89  123.49 1210.16  133.94  1208.7  184.77 1205.37  221.01 1204.33
  278.82 1200.78  360.09  1198.1  383.04 1197.93  391.44 1196.12  392.47 1194.06
  418.47 1194.06  419.66 1196.43  422.14 1196.94   432.7 1196.78  452.26 1200.54
  460.37 1202.65  477.25 1201.06  479.26  1201.5  487.85 1201.27  496.51 1202.62
  512.87 1201.46  527.29 1201.22  614.19 1201.41  672.56 1202.37  799.94 1205.99
#Mann= 3 , 0 , 0
       0      .1       0  391.44    .052       0  419.66     .09       0
Bank Sta=391.44,419.66
Exp/Cntr=0.3,0.1

Type RM Length L Ch R = 1 ,13422.98,243.51,342.76,365.82
BEGIN DESCRIPTION:
Ineffective area added to control expansion
END DESCRIPTION:
XS GIS Cut Line= 3
  1155109.252727   763746.015404  1154931.350558   763405.397804
  1154692.559369   762941.413226
#Sta/Elev= 30
       0 1248.73   10.23 1246.89   28.78 1240.93   36.72 1237.05    51.6 1228.46
   67.79 1213.91   77.72 1214.43   95.71    1213  136.62 1201.24  182.33 1198.61
  208.97 1200.02  230.49 1197.35  275.69 1195.21  340.43 1195.43  357.99 1191.72
   365.8  1191.4  367.01 1188.98  393.01 1188.98  394.49 1191.94  400.51 1194.73
  409.31 1195.32  543.93  1194.4  642.24 1198.08  725.25 1199.47   787.2 1202.38
  802.38  1204.9   819.8 1205.14   838.2 1211.18  868.67 1217.68   906.1 1229.59
#Mann= 3 , 0 , 0
       0      .1       0   365.8    .052       0  394.49     .09       0
Bank Sta=365.8,394.49
Exp/Cntr=0.5,0.3

Type RM Length L Ch R = 1 ,13080.22,83.18,83.02,82.94
BEGIN DESCRIPTION:
Upstream xs of Bridge 3723-269
END DESCRIPTION:
XS GIS Cut Line= 5
  1155181.049584   763747.343071   1155052.93503   763482.175687
  1155173.647045   763263.066494  1155225.740744    763136.56426
   1155184.02901   763020.367334
#Sta/Elev= 30
       0  1233.2    51.6  1228.1   117.1  1206.5     150  1201.5   230.9  1197.4
   276.1  1197.8   294.5  1193.4   311.6  1191.9   334.9  1193.5   366.6  1192.1
   376.2  1194.6   528.6  1192.5     532  1185.8     564  1185.8   566.6  1187.5
   577.5  1186.9   597.9  1188.5   611.2  1192.3   631.8  1190.3   646.3  1194.5
   689.5  1193.8   703.3  1192.3   712.3  1193.5   720.3  1201.4   740.3    1215
   747.6  1223.2   757.1  1224.7   766.4    1232   776.3  1236.9   804.9  1246.9
#Mann= 3 , 0 , 0
       0      .1       0   528.6    .052       0   566.6     .11       0
#XS Ineff= 2 , 0
          515.25 1194.78   607.5         1193.68
Permanent Ineff=
       F       F
Bank Sta=528.6,566.6
Exp/Cntr=0.5,0.3

Type RM Length L Ch R = 2 ,13042.83,,,
BEGIN DESCRIPTION:
Bridge : 3723-269 (Adventist Circle Road)
END DESCRIPTION:
Bridge Culvert--1,0,-1,-1, 0
Deck Dist Width WeirC Skew NumUp NumDn MinLoCord MaxHiCord MaxSubmerge Is_Ogee
12.4,50,2.6,0, 13, 13, 1195.1, , 0.95, 0, 0,0,,
   253.4   304.6   372.8   407.9   455.4   500.8     532     564   606.9   650.2
     701   749.9     760
  1196.9  1197.3  1196.1  1195.1  1195.2  1196.2  1197.3  1197.3    1196  1195.3
  1193.9  1194.2    1195
                                                                                
                        
   212.5     261   313.9   364.3   411.9   457.3     489     521   563.4   605.6
   657.4   706.3     760
  1196.8  1197.3  1196.2  1195.1  1195.2  1196.2  1197.3  1197.3    1196  1195.3
  1193.9  1194.2    1195
                                                                                
                        
BR Coef=-1 , 1 , 0 ,, 0 ,,,0.8,0,1.2,0,
WSPro=,,,, 1 ,,,, 0 ,,,, 0 ,,,,-1 ,-1 ,-1 , 0 , 0 , 0 , 0 , 0
Culvert=1,8,,50,0.027,0.7,1,2,2,1185.8,536,1185.8,493,Culvert #1  , 0 ,12.4
Culvert Bottom n=0.027
Culvert=1,8,,50,0.025,0.9,1,1,1,1185.8,548,1185.8,505,Culvert #2  , 0 ,12.4
Culvert Bottom n=0.025
Culvert=1,8,,50,0.025,0.9,1,1,1,1185.8,560,1185.8,517,Culvert #3  , 0 ,12.4
Culvert Bottom n=0.025
BC Design=,, 0 ,, 0 ,,,,,,

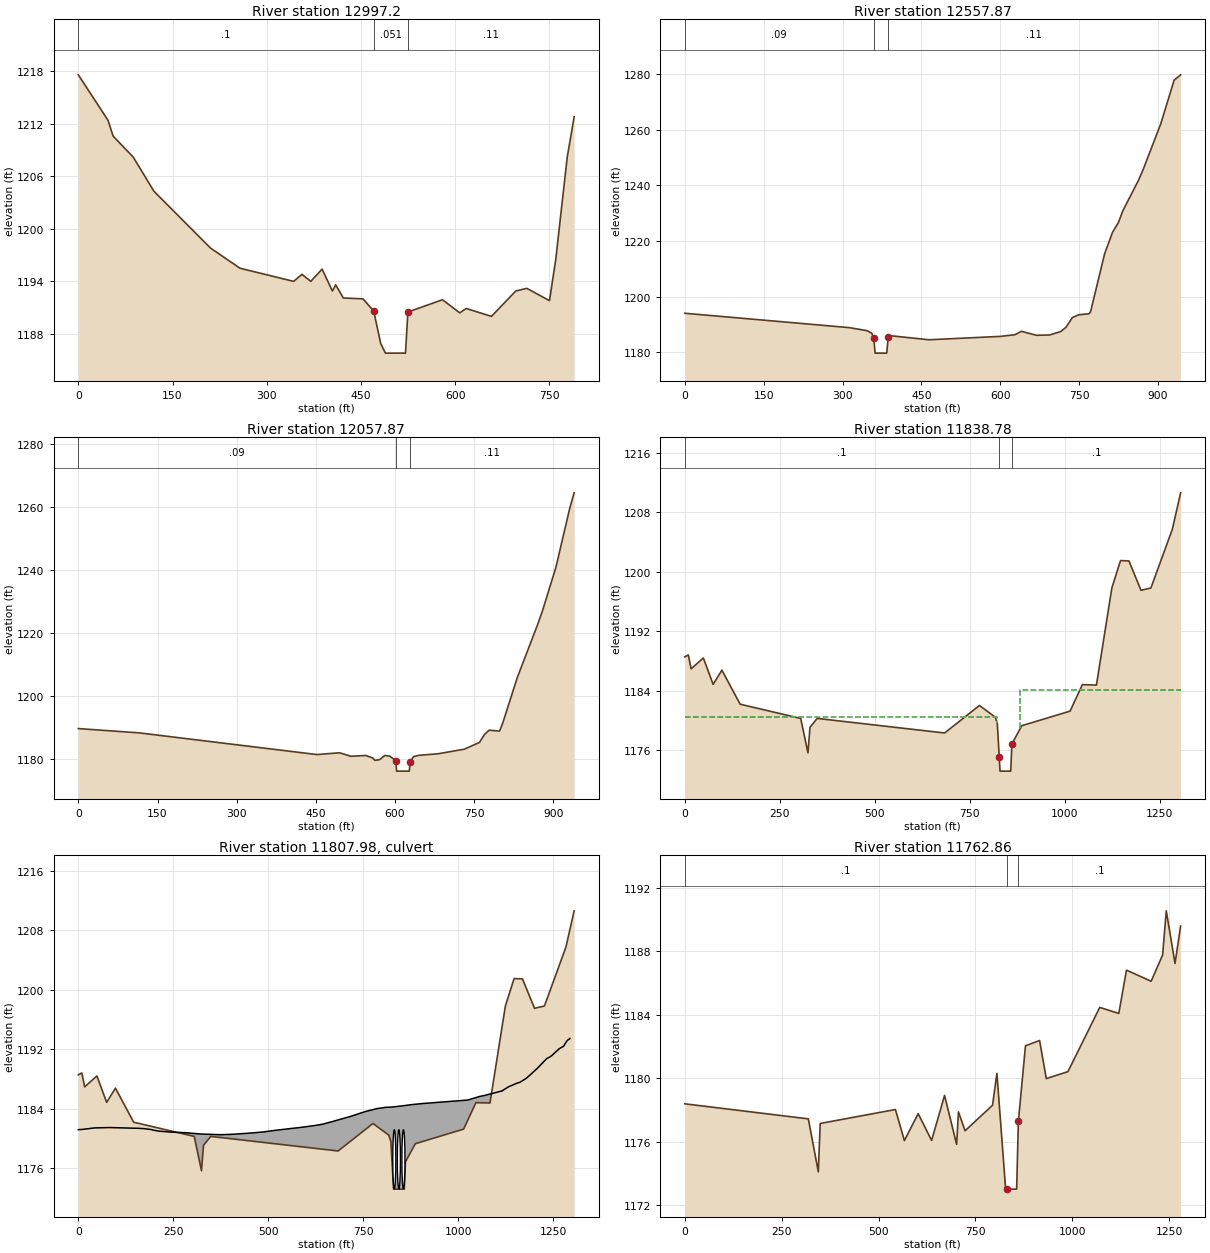
Type RM Length L Ch R = 1 ,12997.2 ,461.68,439.33,401.21
BEGIN DESCRIPTION:
Down stream xs of Bridge 3723-269
END DESCRIPTION:
XS GIS Cut Line= 5
  1155279.370106   763717.548965  1155148.276126   763488.134464
   1155255.97711   763273.787275  1155306.374432   763149.128962
   1155270.43183   763002.490855
#Sta/Elev= 30
       0  1217.6    47.3  1212.4    55.4  1210.6    87.4  1208.2   120.4  1204.3
   210.6  1197.8   257.5  1195.5   342.8    1194   356.2  1194.8   370.2    1194
   388.2  1195.4   404.6  1192.9   409.9  1193.6     422  1192.1   453.3    1192
  470.47  1190.6   481.5  1186.9     489  1185.8     521  1185.8  524.841190.498
   579.9  1191.9   607.5  1190.4   617.7  1190.9   657.9    1190   696.6  1192.9
   714.2  1193.2   750.3  1191.8   760.3  1196.5   778.6  1208.2   789.6  1212.8
#Mann= 3 , 0 , 0
       0      .1       0  470.47    .051       0  524.84     .11       0
#XS Ineff= 2 , 0
       0  465.41 1190.94  534.88       0  1190.5
Permanent Ineff=
       F       F
Bank Sta=470.47,524.84
Exp/Cntr=0.5,0.3

Type RM Length L Ch R = 1 ,12557.87,439.93,500,448.74
XS GIS Cut Line= 3
  1155790.258178   763458.671479  1155631.697856   763125.525602
  1155181.260022   762769.969364
#Sta/Elev= 30
       0 1194.03  313.22 1188.86  346.64 1187.77  355.47 1186.87  359.31 1184.98
  361.95 1179.71  383.95 1179.71  386.78 1185.38  390.87 1185.96  464.37 1184.51
  600.03 1185.72  628.21 1186.34   639.8 1187.54  668.74 1186.12  693.41 1186.22
  714.68 1187.45  724.84    1189   737.1 1192.51  749.07 1193.48  768.49 1193.84
  771.47 1194.51  798.29 1215.39  813.29 1223.08  824.49 1226.59   832.9 1230.83
  862.67 1241.76  872.36 1246.04  905.15 1262.13  930.42 1277.72  942.81 1279.67
#Mann= 3 , 0 , 0
       0     .09       0  359.31    .051       0  386.78     .11       0
Bank Sta=359.31,386.78
Exp/Cntr=0.3,0.1

Type RM Length L Ch R = 1 ,12057.87,215,219.09,222
XS GIS Cut Line= 3
  1155993.911148   763204.273046    1155674.3334   762679.600118
  1155434.429125   762460.273088
#Sta/Elev= 30
       0 1189.53  115.01 1188.17  452.19 1181.27  494.98 1181.84  516.55 1180.73
  544.89 1180.98  557.62 1180.19  561.92 1179.43  570.77 1179.66  580.63 1180.99
  589.96 1180.77  601.35 1179.37  603.03 1176.01  627.03 1176.01  628.51 1178.96
  635.35 1180.63  644.76 1181.02  681.22 1181.52  731.06 1182.97  760.06 1185.13
  769.26 1187.61  778.27 1189.02  798.09 1188.72  804.36 1191.43  831.77 1205.81
  869.98 1222.48  879.36 1226.94  904.79 1240.76  931.47 1259.81  939.39 1264.44
#Mann= 3 , 0 , 0
       0     .09       0  601.35    .051       0  628.51     .11       0
Bank Sta=601.35,628.51
Exp/Cntr=0.5,0.3

Type RM Length L Ch R = 1 ,11838.78,72,75.92,77
XS GIS Cut Line= 5
  1156481.657284   763118.707834  1156115.980575   762817.983279
  1156023.036501   762743.918445  1155848.083863   762561.038506
  1155624.318476   762159.283267
#Sta/Elev= 30
       0 1188.57    9.24 1188.83   16.66 1186.96   48.87 1188.42   74.57 1184.87
   97.73 1186.78  145.71  1182.2  305.06 1180.29  324.22 1175.67  329.53 1179.09
  348.56 1180.29  684.03 1178.33  775.63 1182.03  817.42 1180.45  822.73 1179.59
  827.75 1175.12  829.79  1173.2     858  1173.2  861.08 1176.85  887.18 1179.31
 1014.29 1181.27 1046.63 1184.83 1083.67 1184.78 1124.22 1197.83  1147.1 1201.52
  1169.2 1201.47 1200.95 1197.52 1227.01 1197.83 1283.46 1205.73 1305.25 1210.63
#Mann= 3 , 0 , 0
       0      .1       0  827.75    .045       0  861.08      .1       0
#XS Ineff= 2 , 0
          822.58 1180.49  883.36         1184.05
Permanent Ineff=
       F       F
Bank Sta=827.75,861.08
Exp/Cntr=0.3,0.1

Type RM Length L Ch R = 2 ,11807.98,,,
BEGIN DESCRIPTION:
Culvert: 3723-53 (SR 1240)
END DESCRIPTION:
Bridge Culvert--1,0,-1,-1, 0
Deck Dist Width WeirC Skew NumUp NumDn MinLoCord MaxHiCord MaxSubmerge Is_Ogee
15.8,30,2.6,0, 69, 69, 1180.52, , 0.95, 0, 0,0,,
       0    4.14   10.26   42.25   80.55   105.4  141.57  157.59  171.97  191.11
  199.45  201.21  211.72   243.6  282.17  319.67   373.4  403.33  444.32  462.42
  490.89  491.28  491.61  492.02  507.23  517.05  538.77  580.54     622  637.12
  643.74  663.73  670.62  718.43   742.5  756.16  785.28  786.26  804.98  806.13
  823.01  853.16  876.33  905.51 1024.91 1057.41 1060.89 1068.68 1114.92 1115.23
 1116.26 1132.03 1157.16 1162.14 1179.17 1179.94 1205.33 1207.08 1229.43  1233.2
 1240.51 1246.69 1265.97 1277.65 1283.87 1287.81 1292.29 1292.88  1294.1
  1181.2 1181.21 1181.23 1181.43 1181.48 1181.45  1181.4 1181.38 1181.34 1181.22
 1181.11  1181.1    1181 1180.87 1180.79 1180.62 1180.52 1180.57 1180.71 1180.78
 1180.91 1180.91 1180.91 1180.93 1181.03  1181.1 1181.23 1181.47 1181.75 1181.88
 1181.94 1182.22 1182.31 1183.01 1183.42 1183.64 1184.02 1184.03 1184.17 1184.19
 1184.23  1184.4 1184.56 1184.71 1185.18 1185.68 1185.71 1185.79  1186.4 1186.39
 1186.44 1186.95  1187.5 1187.56  1188.1 1188.13 1189.31 1189.38 1190.57 1190.77
 1190.95 1191.18 1192.08 1192.43 1192.96 1193.23 1193.36 1193.44 1193.48
                                                                                
                                                                                
                                                                                
                                                                                
                                                                                
                                                                                
                                                                        
       0    4.14   10.26   42.25   80.55   105.4  141.57  157.59  171.97  191.11
  199.45  201.21  211.72   243.6  282.17  319.67   373.4  403.33  444.32  462.42
  490.89  491.28  491.61  492.02  507.23  517.05  538.77  580.54     622  637.12
  643.74  663.73  670.62  718.43   742.5  756.16  785.28  786.26  804.98  806.13
  823.01  853.16  876.33  905.51 1024.91 1057.41 1060.89 1068.68 1114.92 1115.23
 1116.26 1132.03 1157.16 1162.14 1179.17 1179.94 1205.33 1207.08 1229.43  1233.2
 1240.51 1246.69 1265.97 1277.65 1283.87 1287.81 1292.29 1292.88  1294.1
  1181.2 1181.21 1181.23 1181.43 1181.48 1181.45  1181.4 1181.38 1181.34 1181.22
 1181.11  1181.1    1181 1180.87 1180.79 1180.62 1180.52 1180.57 1180.71 1180.78
 1180.91 1180.91 1180.91 1180.93 1181.03  1181.1 1181.23 1181.47 1181.75 1181.88
 1181.94 1182.22 1182.31 1183.01 1183.42 1183.64 1184.02 1184.03 1184.17 1184.19
 1184.23  1184.4 1184.56 1184.71 1185.18 1185.68 1185.71 1185.79  1186.4 1186.39
 1186.44 1186.95  1187.5 1187.56  1188.1 1188.13 1189.31 1189.38 1190.57 1190.77
 1190.95 1191.18 1192.08 1192.43 1192.96 1193.23 1193.36 1193.44 1193.48
                                                                                
                                                                                
                                                                                
                                                                                
                                                                                
                                                                                
                                                                        
BR Coef=-1 , 0 , 0 ,, 0 ,,,0.8,-1,,0,
WSPro=,,,, 1 ,,,, 0 ,,,, 0 ,,,,-1 ,-1 ,-1 , 0 , 0 , 0 , 0 , 0
Culvert=1,8,,50,0.027,0.7,1,2,2,1173.2,831.79,1173,830.11,Culvert #1  , 0 ,5.8
Culvert Bottom n=0.027
Culvert=1,8,,50,0.025,0.5,1,2,2,1173.2,843.79,1173,842.11,Culvert #2  , 0 ,5.8
Culvert Bottom n=0.025
Culvert=1,8,,50,0.025,0.5,1,2,2,1173.2,855.79,1173,854.11,Culvert #3  , 0 ,5.8
Culvert Bottom n=0.025
BC Design=,, 0 ,, 0 ,,,,,,

Type RM Length L Ch R = 1 ,11762.86,843.25,1204.99,1090.72
XS GIS Cut Line= 5
  1156539.445677    763066.57699  1156209.549673   762788.812791
  1156095.728088   762695.611811  1155906.881233   762513.425413
  1155707.481561   762122.295283
#Sta/Elev= 30
       0 1178.38  318.86 1177.43  344.65 1174.09  349.49 1177.14  543.67 1178.02
  566.78 1176.06   602.4 1177.76  637.09 1176.07  670.54 1178.91  701.59 1175.82
  706.37 1177.87  723.44 1176.68  794.33 1178.29  805.64  1180.3  828.11    1173
  830.76    1173  856.55    1173  861.04 1177.27  879.35 1182.04  915.76 1182.37
  933.09 1179.97  988.98 1180.41 1071.05 1184.46 1120.24 1184.08 1140.01 1186.81
 1203.72 1186.11 1233.27 1187.76 1242.78 1190.55 1265.31 1187.23  1279.8 1189.59
#Mann= 3 , 0 , 0
       0      .1       0  830.76    .045       0  861.04      .1       0
#XS Ineff= 2 , 0
          804.34 1178.37   871.2         1178.48
Permanent Ineff=
       F       F
Bank Sta=830.76,861.04
Exp/Cntr=0.3,0.1

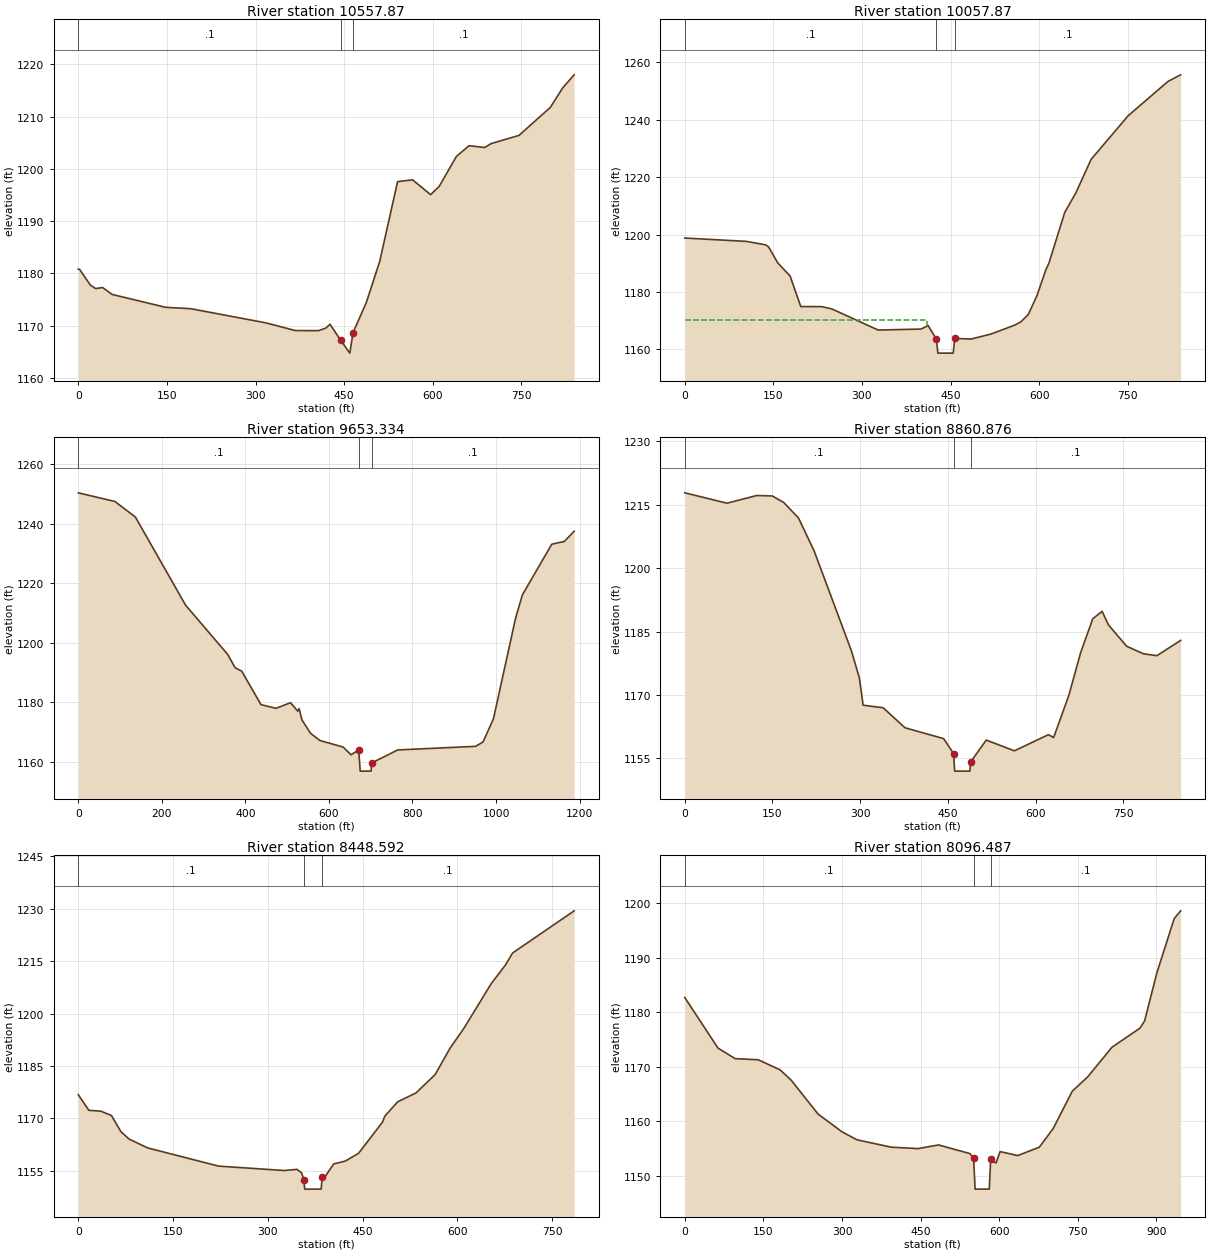
Type RM Length L Ch R = 1 ,10557.87,436.83,500,524.14
XS GIS Cut Line= 3
  1156542.678605   763103.351502    1156806.7699   762727.374738
  1157050.332861   762436.025688
#Sta/Elev= 30
       0 1180.82    1.95 1180.81   20.49 1177.76   29.37 1177.11    41.1 1177.31
    57.2 1175.99  147.89 1173.52  190.26 1173.26  317.56 1170.55  367.05 1169.08
   406.7 1169.06  419.25 1169.57  425.98 1170.29  443.98 1167.23  459.46 1164.76
  465.05 1168.69  487.69 1174.52  510.15 1182.33  540.36 1197.57  565.77 1197.91
  596.24 1195.08  610.68 1196.64  639.93 1202.39  661.35 1204.44  687.81  1204.1
  698.61 1204.84  745.92 1206.42  799.04 1211.79  819.75 1215.49  839.21    1218
#Mann= 3 , 0 , 0
       0      .1       0  443.98    .045       0  465.05      .1       0
Bank Sta=443.98,465.05
Exp/Cntr=0.3,0.1

Type RM Length L Ch R = 1 ,10057.87,407.75,404.54,360.44
XS GIS Cut Line= 3
  1156499.001749   763305.949768  1156911.047941   763168.194887
  1157316.022196   763158.318298
#Sta/Elev= 30
       0 1198.77  104.39  1197.6  137.06 1196.39  141.81  1195.7  157.56 1190.06
  178.23 1185.55  196.39 1174.88  231.82 1174.85  248.92 1174.06  327.43 1166.69
  399.97 1167.03  412.11 1168.24  426.12 1163.43  428.51 1158.64  454.51 1158.64
  457.08 1163.79   484.4 1163.53  518.43 1165.29  559.18 1168.45  569.02 1169.53
  581.71 1172.13   596.4 1178.72  611.56 1187.82  616.57    1190  643.36 1207.72
  662.03 1214.45  688.01 1226.21  750.97 1241.46  818.13 1253.37  839.56 1255.68
#Mann= 3 , 0 , 0
       0      .1       0  426.12    .052       0  457.08      .1       0
#XS Ineff= 2 , 0
          409.55 1170.14
Permanent Ineff=
       F       F
Bank Sta=426.12,457.08
Exp/Cntr=0.3,0.1

Type RM Length L Ch R = 1 ,9653.334,814.08,792.46,726.45
XS GIS Cut Line= 3
  1156421.311229   763926.604132  1156946.905673   763578.678112
  1157406.502358    763264.51329
#Sta/Elev= 30
       0 1250.45   87.54 1247.54  136.64  1242.3   256.7 1212.69  358.11 1196.02
  375.19 1191.64  391.07 1190.49  437.33 1179.22  473.35 1177.98  507.96 1179.88
  525.39 1177.02  528.52  1177.9  535.31  1174.1  556.07 1169.56  578.62 1167.15
  634.12 1164.95  652.71 1162.35  671.25 1163.97  674.81 1156.86  700.81 1156.86
  702.17 1159.59  764.52 1163.98  950.95  1165.2   968.9 1166.67  993.83 1174.47
 1046.68 1208.22 1063.08 1216.14 1133.42 1233.16  1163.8 1234.12 1187.03 1237.54
#Mann= 3 , 0 , 0
       0      .1       0  671.25    .052       0  702.17      .1       0
Bank Sta=671.25,702.17
Exp/Cntr=0.3,0.1

Type RM Length L Ch R = 1 ,8860.876,422.05,412.28,394.2
XS GIS Cut Line= 3
  1157534.926797   764389.331634  1157637.465841   763933.765231
  1157713.637716   763560.230107
#Sta/Elev= 30
       0 1217.81   72.25 1215.36  122.99 1217.17  149.65 1217.07  169.24 1215.53
  194.51 1211.86  221.21 1204.09  285.08 1180.43  298.67    1174  305.06  1167.6
  339.33 1166.99  376.72 1162.26  442.86 1159.69  459.68 1156.17  461.76 1152.01
  487.76 1152.01  488.83 1154.15  515.73 1159.35  563.84 1156.81  621.96 1160.63
  630.95 1159.95  656.95 1169.92   677.2 1180.03   697.9 1188.03  713.87 1189.79
  724.72 1186.59  755.84 1181.54  784.61 1179.75  807.57 1179.31  848.19 1182.92
#Mann= 3 , 0 , 0
       0      .1       0  459.68    .052       0  488.83      .1       0
Bank Sta=459.68,488.83
Exp/Cntr=0.3,0.1

Type RM Length L Ch R = 1 ,8448.592,329.89,352.1,339.4
XS GIS Cut Line= 3
  1158012.157632   764357.954361  1158024.184622   763995.288672
  1158025.597234   763573.077686
#Sta/Elev= 30
       0 1176.78   16.63 1172.33   35.78 1172.08   52.38 1170.85   67.37 1166.24
   80.38 1164.09  109.79 1161.56  221.97 1156.35  325.69 1155.09  346.17 1155.41
  353.46 1154.45  357.12 1152.46  358.47 1149.76  384.47 1149.76  386.16 1153.15
  391.73 1153.61  404.33 1156.97  422.88  1157.8  443.73 1160.02  481.31 1168.86
  485.57 1170.72   505.7 1174.76  534.75 1177.31  565.08 1182.58  588.55 1190.11
  610.67 1195.84  653.55 1208.53  676.18 1213.91  687.64 1217.37  785.08 1229.44
#Mann= 3 , 0 , 0
       0      .1       0  357.12    .052       0  386.16      .1       0
Bank Sta=357.12,386.16
Exp/Cntr=0.3,0.1

Type RM Length L Ch R = 1 ,8096.487,470.87,538.62,563.86
XS GIS Cut Line= 3
  1158216.901564   764514.540756    1158366.1438   763974.730962
  1158320.128451   763591.270117
#Sta/Elev= 30
       0 1182.68   63.41 1173.41   96.17 1171.48  140.03 1171.28  181.95 1169.42
  202.81 1167.56  254.21 1161.34   300.1 1158.06  328.68  1156.6   394.1 1155.25
  445.17 1154.99  484.38 1155.66  543.94 1154.08  551.17 1153.28  554.03 1147.56
  581.03 1147.56  583.77 1153.03  593.98 1152.35  601.79 1154.44  635.38 1153.71
  676.59 1155.25  703.39 1158.72  739.45 1165.51  768.91 1168.14  815.14 1173.56
   868.5 1177.06  877.55  1178.4  900.99 1187.23  934.02 1197.15  946.27 1198.58
#Mann= 3 , 0 , 0
       0      .1       0  551.17    .052       0  583.77      .1       0
Bank Sta=551.17,583.77
Exp/Cntr=0.3,0.1

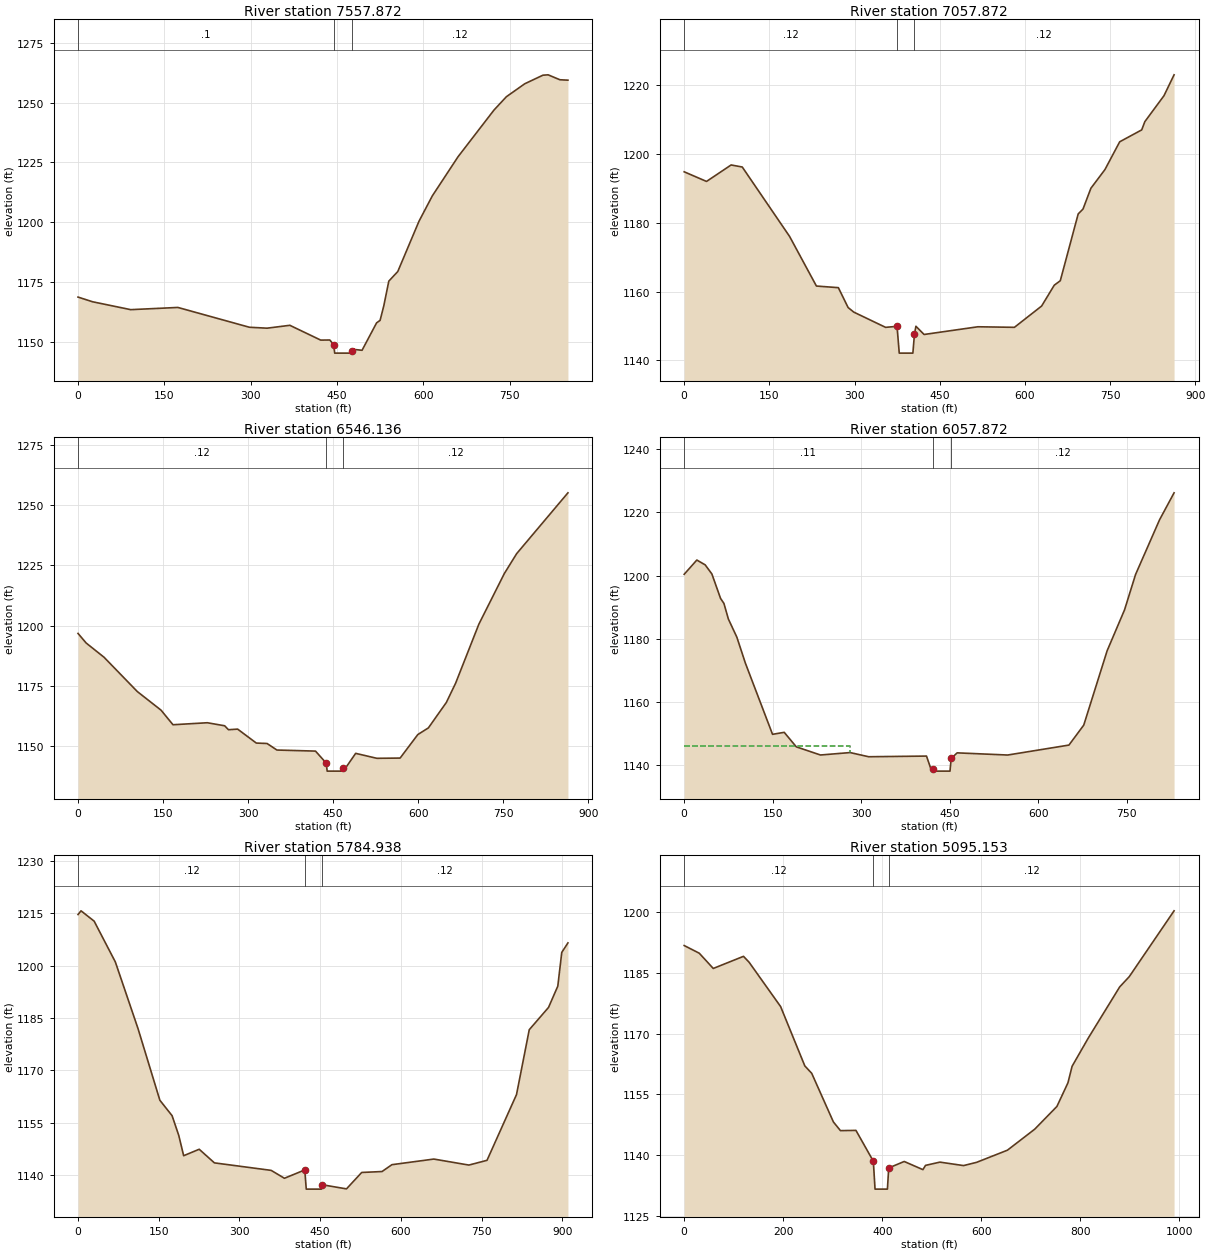
Type RM Length L Ch R = 1 ,7557.872,485.34,500,454.45
XS GIS Cut Line= 3
  1158387.465864   764455.249627   1158758.76209   764192.353032
  1159128.341221   764049.227919
#Sta/Elev= 30
       0 1168.73    25.5 1166.76   91.58 1163.48  173.51  1164.4  297.74 1156.13
  328.45 1155.74  368.06 1156.94  421.68 1150.76  437.57  1150.8  444.26 1148.81
  446.01 1145.32  475.01 1145.32  475.55 1146.41  477.47 1146.92  493.51  1146.5
  518.79 1157.96  524.87 1159.01  531.21 1164.98  540.03 1175.39  555.61 1179.41
  592.53 1200.44  615.65 1211.01  660.29 1227.34  722.87 1246.88  744.37 1252.43
  776.21 1257.83  807.84 1261.42  816.86 1261.57  837.33 1259.51  851.27 1259.34
#Mann= 3 , 0 , 0
       0      .1       0  444.26    .052       0  475.55     .12       0
Bank Sta=444.26,475.55
Exp/Cntr=0.3,0.1

Type RM Length L Ch R = 1 ,7057.872,502.72,511.74,475.86
XS GIS Cut Line= 3
  1158541.859755   764850.963364  1158881.105662   764638.848192
  1159257.104772   764369.082699
#Sta/Elev= 30
       0 1194.82   39.37 1192.02   82.71 1196.81   102.3 1196.21  185.65 1176.04
  232.92 1161.61  271.57 1161.14  288.75 1155.36  298.78 1154.03  354.78  1149.6
  374.93  1149.9  378.83 1142.11  402.83 1142.11  405.59 1147.63  408.16 1149.92
   422.6 1147.53  517.39 1149.77  581.68 1149.61  629.59  1155.8  651.86 1161.86
  662.45 1163.15  693.98 1182.57  702.48 1183.99  716.34 1190.03  741.01 1195.44
  767.08 1203.54  805.85    1207  811.42 1209.41  845.08 1216.94  862.86 1223.01
#Mann= 3 , 0 , 0
       0     .12       0  374.93    .052       0  405.59     .12       0
Bank Sta=374.93,405.59
Exp/Cntr=0.3,0.1

Type RM Length L Ch R = 1 ,6546.136,480.92,488.26,472.97
XS GIS Cut Line= 3
  1158917.739291   765190.601142  1159273.696278    764918.14021
   1159595.60438   764655.107023
#Sta/Elev= 30
       0  1196.7   14.43  1192.7   45.77 1186.82   104.6 1172.52  146.33 1164.81
  167.44 1158.73  227.98 1159.56  258.57  1158.3  265.28 1156.66  281.47 1156.91
  314.43 1151.11  333.38 1150.93  350.78 1148.21  418.77 1147.77  437.69 1142.79
  439.36 1139.44  466.36 1139.44  467.09  1140.9  472.84  1141.1   489.6 1146.83
     527 1144.77  568.03 1144.87   599.2 1154.64  617.91 1157.43  649.58 1168.01
  665.94 1176.03  706.85 1200.53  751.72 1221.57  773.49 1229.87  863.97 1255.18
#Mann= 3 , 0 , 0
       0     .12       0  437.69    .052       0  467.09     .12       0
Bank Sta=437.69,467.09
Exp/Cntr=0.3,0.1

Type RM Length L Ch R = 1 ,6057.872,277.34,272.93,247.23
BEGIN DESCRIPTION:
Ineffective area added to control expansion
END DESCRIPTION:
XS GIS Cut Line= 3
  1159247.691235   765551.378736  1159569.106984   765282.121135
  1159878.956722   765012.633192
#Sta/Elev= 30
       0 1200.39   21.46  1204.9   35.58 1203.37   46.91 1200.51   61.65 1192.76
   67.35 1191.17    74.9 1186.24   89.24 1180.51  103.67  1172.3   149.7 1149.77
  169.49  1150.4  189.96 1145.81  230.93 1143.23  281.14    1144  312.48 1142.68
  410.53 1142.89  419.29 1138.13  420.94 1138.93  421.34 1138.13  450.34 1138.13
  452.35 1142.15  462.46 1143.91  548.02 1143.22  651.85 1146.37  676.92 1152.68
  716.54  1176.2  746.01 1189.13  764.67 1200.31  805.35 1217.63  829.94 1226.16
#Mann= 3 , 0 , 0
       0     .11       0  420.94    .052       0  452.35     .12       0
#XS Ineff= 2 , 0
       0     281    1146               0
Permanent Ineff=
       F       F
Bank Sta=420.94,452.35
Exp/Cntr=0.3,0.1

Type RM Length L Ch R = 1 ,5784.938,691.85,689.78,557.02
XS GIS Cut Line= 3
  1159437.758837   765843.921525  1159705.825215   765501.148048
  1160019.650777    765144.45808
#Sta/Elev= 30
       0 1214.65    5.57 1215.71   29.95 1212.75   69.31 1201.07  111.43 1181.99
  152.04 1161.46  174.76 1157.03  187.16 1151.38  196.28 1145.57  225.12 1147.42
   253.4 1143.52  358.86 1141.37   383.5 1139.11  421.29  1141.5  424.04    1136
  452.04    1136  452.68 1137.28  498.77 1136.07  527.04 1140.77  564.87 1141.04
  583.18    1143  661.11 1144.61  726.16 1142.89  759.89 1144.25   814.7 1163.08
  838.39 1181.66  874.22 1188.05   891.4 1194.13  898.78  1203.8  910.24 1206.52
#Mann= 3 , 0 , 0
       0     .12       0  421.29    .052       0  452.68     .12       0
Bank Sta=421.29,452.68
Exp/Cntr=0.3,0.1

Type RM Length L Ch R = 1 ,5095.153,452.55,440.37,363.04
XS GIS Cut Line= 3
   1160135.67811   766091.087751   1160302.11009   765744.019613
  1160139.887604   765161.946314
#Sta/Elev= 30
       0 1191.68   30.46 1189.79   58.74 1186.03  119.78 1189.02  131.01 1187.58
  194.75 1176.64  243.58 1162.03  257.53  1160.2  301.28 1148.23  315.53 1146.08
  346.83 1146.14  381.94 1138.55  385.38 1131.67  410.38 1131.67  412.99 1136.89
  444.31 1138.48  482.04 1136.47   487.3 1137.52  516.41 1138.32  564.05 1137.47
  590.27 1138.26  652.67 1141.26  707.83 1146.44  752.62 1152.04  774.89 1157.86
  783.25 1161.93  815.61 1168.82   879.4 1181.49  898.66 1184.01  989.17 1200.23
#Mann= 3 , 0 , 0
       0     .12       0  381.94    .052       0  412.99     .12       0
Bank Sta=381.94,412.99
Exp/Cntr=0.3,0.1

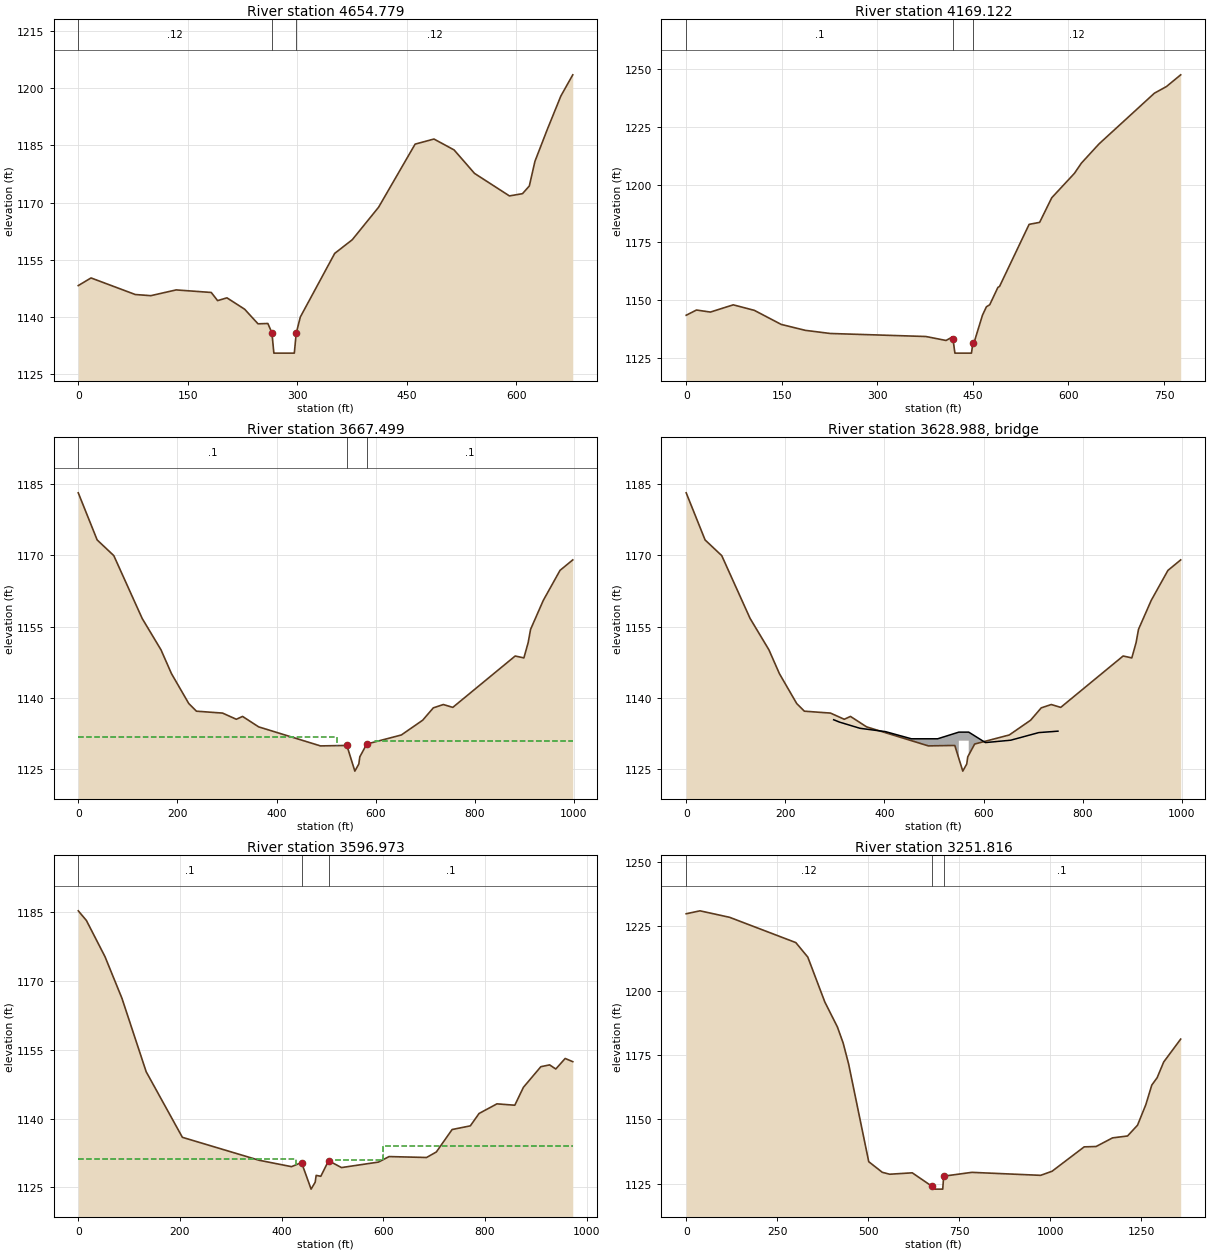
Type RM Length L Ch R = 1 ,4654.779,419.35,485.66,506.18
XS GIS Cut Line= 3
  1160573.012717   765690.112923  1160502.700244    765422.04647
  1160507.094723   765022.144179
#Sta/Elev= 30
       0  1148.2   17.51  1150.2   78.09 1145.85   99.36 1145.55  133.98 1147.06
  182.09 1146.39  190.79 1144.25  203.57 1144.98  227.77    1142  246.12 1138.16
   259.6 1138.25  265.15  1135.8  267.82 1130.47  295.82 1130.47  298.44  1135.7
  304.04 1139.95   351.1 1156.64  375.17 1160.23  411.21 1168.76  461.22 1185.32
  487.03 1186.66  514.58  1183.8  542.56 1177.64  590.35 1171.73  608.24 1172.32
  617.59 1174.34  625.29 1180.81  642.32 1189.24  660.82 1197.97  677.06 1203.51
#Mann= 3 , 0 , 0
       0     .12       0  265.15    .052       0  298.44     .12       0
Bank Sta=265.15,298.44
Exp/Cntr=0.3,0.1

Type RM Length L Ch R = 1 ,4169.122,372.81,501.62,538.96
XS GIS Cut Line= 3
  1160505.629872    765865.89414  1160875.460803   765636.426438
  1161099.522165   765379.474783
#Sta/Elev= 30
       0 1143.39   16.11 1145.65   37.98 1144.77    73.9  1147.9  106.97 1145.51
  149.14 1139.42  186.94 1136.85  226.15 1135.49  376.26 1134.18  407.88 1132.46
  416.56 1133.81  418.74 1133.07  421.78 1126.98  447.78 1126.98  449.98 1131.38
  452.99 1132.59  465.06 1143.43  471.29 1147.08  476.43 1147.94  489.23 1155.44
  491.85 1155.89  538.26 1182.77  554.76 1183.63  573.76 1194.29  609.39 1204.87
   620.2 1209.26  647.94 1217.61  734.89 1239.59  753.92 1242.49  776.16 1247.55
#Mann= 3 , 0 , 0
       0      .1       0  418.74    .052       0  449.98     .12       0
Bank Sta=418.74,449.98
Exp/Cntr=0.5,0.3

Type RM Length L Ch R = 1 ,3667.499,70.68,70.52,70.88
BEGIN DESCRIPTION:
Upstream xs of Bridge 3723-52
END DESCRIPTION:
XS GIS Cut Line= 5
  1160303.492512   766072.273256  1160588.386806   765917.714507
   1160813.39129   766013.976083  1160984.391486   766098.220288
  1161206.876414   766013.336187
#Sta/Elev= 30
       0  1183.1    38.1  1173.2    71.7  1169.9   128.9  1156.7   166.9  1150.1
     188  1145.1     223  1138.8   238.4  1137.2   291.1  1136.8   318.9  1135.5
   331.4  1136.1     364  1133.9   488.7  1129.9  541.861129.998     558  1124.6
     566  1126.1     568  1127.6  581.971130.292   651.8  1132.2   694.8  1135.3
   716.3  1137.9   736.5  1138.6   755.6    1138   881.5  1148.8     899  1148.4
   907.6  1151.6   912.5  1154.4   938.2  1160.5   971.9  1166.8   997.6    1169
#Mann= 3 , 0 , 0
       0      .1       0  541.86    .052       0  581.97      .1       0
#XS Ineff= 2 , 0
       0   521.5  1131.7   598.5       0  1130.9
Permanent Ineff=
       F       F
Bank Sta=541.86,581.97
Exp/Cntr=0.5,0.3

Type RM Length L Ch R = 3 ,3628.988,,,
BEGIN DESCRIPTION:
Bridge : 3723-52 (Fish Hatchery Road)
END DESCRIPTION:
Bridge Culvert--1,0,-1,-1, 0
Deck Dist Width WeirC Skew NumUp NumDn MinLoCord MaxHiCord MaxSubmerge Is_Ogee
28.5,20,2.6,0, 14, 14, 1131.4, , 0.95, 0, 0,0,,
   297.5   309.4   350.7   402.2   454.3   507.3     550     550     570     570
   603.7   654.7   711.2     750
  1135.4  1134.9  1133.6  1132.9  1131.4  1131.4  1132.8  1132.8  1132.8  1132.8
  1130.6  1131.1  1132.7    1133
                                                            1131    1131
                                
   250.3   301.8   353.9   406.9     450     450     470     470   503.3   545.9
   610.9     654   710.4     750
  1133.6  1132.9  1131.4  1131.4  1132.8  1132.8  1132.8  1132.8  1130.6  1131.9
  1132.7    1133  1136.9  1137.5
                                            1131    1131
                                
BR Coef=-1 , 1 , 0 ,, 0 ,,,0.8,0,1.2,0,
WSPro=,,,, 1 ,,,, 0 ,,,, 0 ,,,,-1 ,-1 ,-1 , 0 , 0 , 0 , 0 , 0
BC Design=,, 0 ,, 0 ,,,,,,

Type RM Length L Ch R = 1 ,3596.973,364.93,345.16,311.96
BEGIN DESCRIPTION:
Down stream xs of Bridge 3723-52
END DESCRIPTION:
XS GIS Cut Line= 5
  1160336.108216   766117.095976  1160592.389267   765991.115323
  1160754.082625   766058.968841  1160974.116294   766167.259257
  1161223.597483   766073.417715
#Sta/Elev= 30
       0  1185.3      16  1183.2    52.6  1175.3      86  1166.2   133.6  1150.2
   204.8  1135.9   355.6  1130.9   419.5  1129.5  439.181130.399     458  1124.6
     466  1126.1     468  1127.6   477.1  1127.4  492.381130.796   517.8  1129.3
   590.6  1130.5   611.4  1131.7   685.1  1131.5   704.3  1132.7   735.4  1137.6
   771.2  1138.4   788.4  1141.1   823.6  1143.2   858.7  1142.9   875.6  1146.8
   909.9  1151.3   927.2  1151.7   939.3  1150.8   957.8  1153.1   972.7  1152.4
#Mann= 3 , 0 , 0
       0      .1       0  439.18    .052       0  492.38      .1       0
#XS Ineff= 3 ,-1
       0     428  1131.2     492     600    1131     600    1000    1134
Permanent Ineff=
       F       F       F
Bank Sta=439.18,492.38
Exp/Cntr=0.5,0.3

Type RM Length L Ch R = 1 ,3251.816,461.36,484.53,287.7
XS GIS Cut Line= 3
  1160037.266428   766531.733497   1160678.89516   766325.144461
  1161329.936837   766116.811175
#Sta/Elev= 30
       0 1229.88   37.92 1231.02  119.15  1228.5  300.99 1218.67  333.86 1213.03
  380.59 1195.59  415.13 1185.88  430.84 1179.67  446.01 1171.44   501.2 1133.49
  538.37 1129.37  558.67 1128.62  620.64 1129.17   674.8 1123.93  675.35 1122.83
  704.35 1122.83  706.86 1127.86  784.07 1129.35  973.11 1128.19 1004.48 1129.78
 1092.68 1139.26 1125.38  1139.4 1170.55 1142.75 1211.72 1143.49 1239.09 1147.68
 1261.96 1155.68 1278.21 1163.26 1292.96 1166.14 1311.02 1172.26 1357.63 1181.16
#Mann= 3 , 0 , 0
       0     .12       0   674.8    .052       0  706.86      .1       0
Bank Sta=674.8,706.86
Exp/Cntr=0.3,0.1