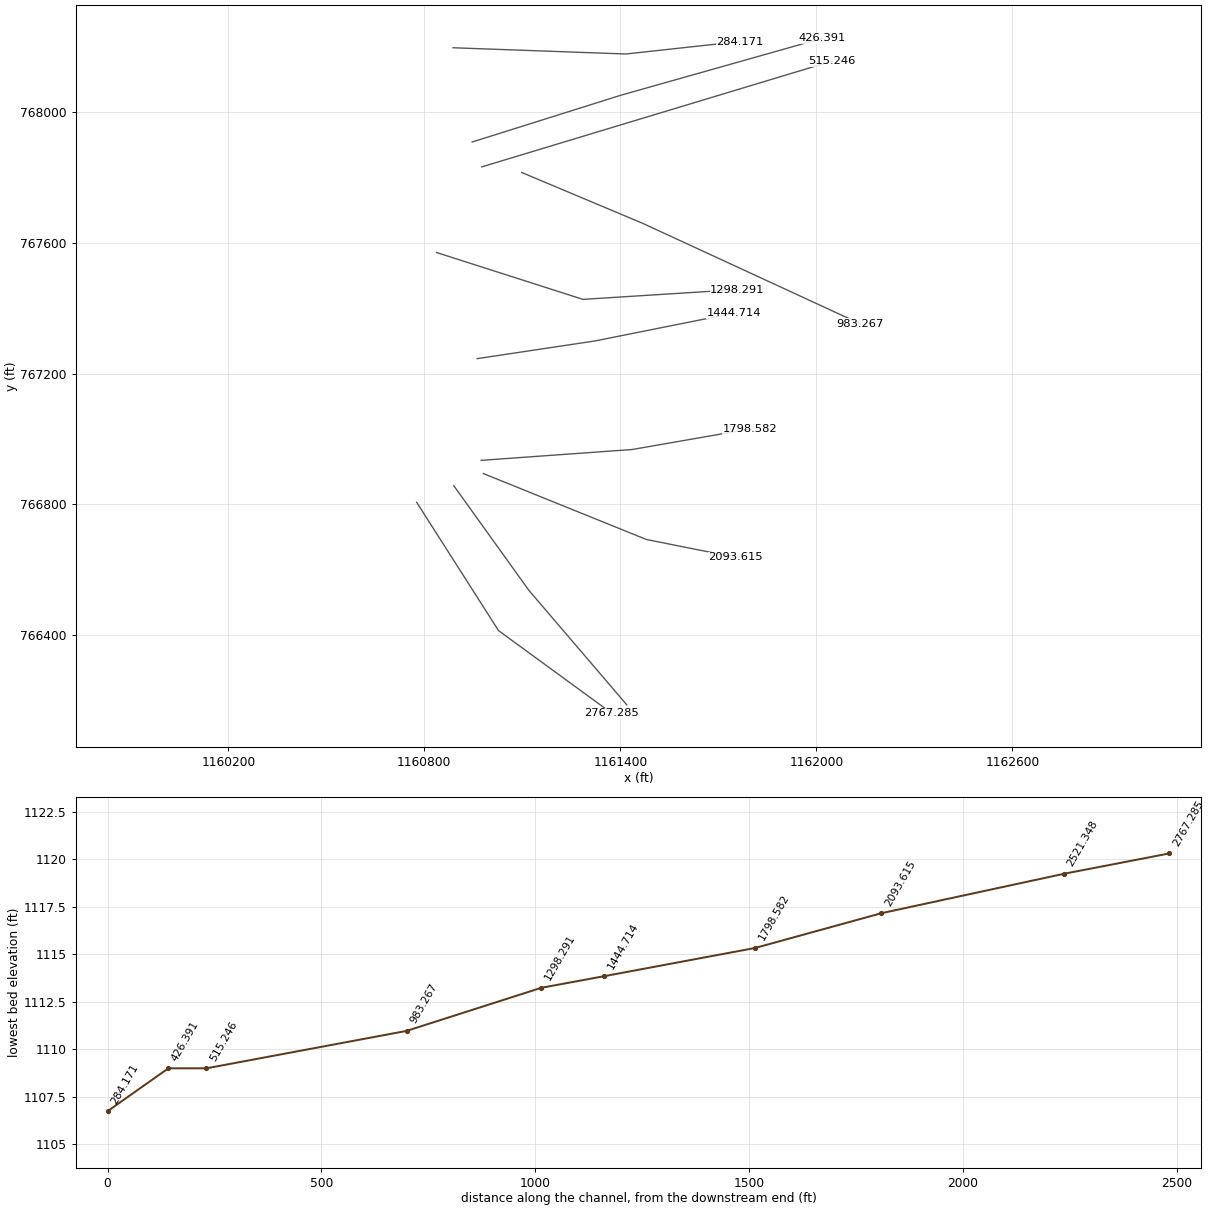
HEC-RAS study russell.prj: RussellCreek

--- russell.g01 (geometry) --- (continued)

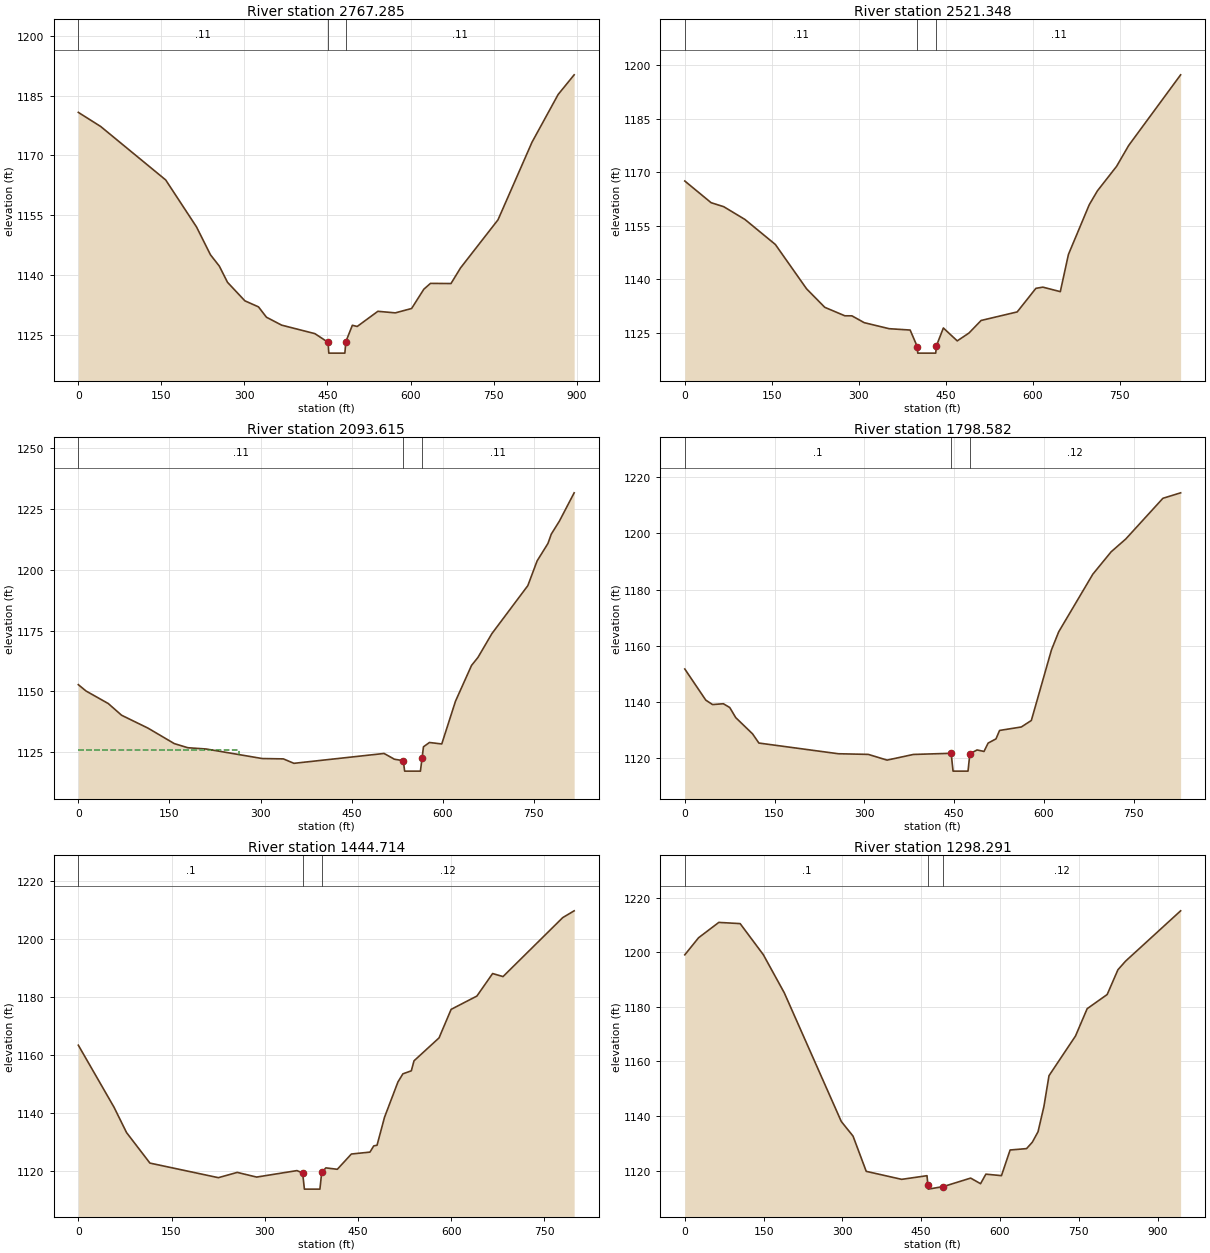
Type RM Length L Ch R = 1 ,2767.285,145.19,245.94,150.81
XS GIS Cut Line= 3
  1160776.626027   766806.323815  1161027.114269   766413.745704
  1161374.282224    766160.32776
#Sta/Elev= 30
       0 1180.83   40.32 1177.29  157.79 1163.85  213.39 1152.05  238.65 1145.04
  254.66 1142.19  269.42 1138.12  300.77 1133.47  325.44 1131.94  339.73 1129.35
  367.25 1127.35  427.22 1125.22  450.53 1123.09     451 1123.06  452.37 1120.32
  481.37 1120.32   483.2 1123.21  494.92 1127.32  503.65 1127.02  540.98 1130.83
  572.52 1130.44  601.97 1131.54  623.99 1136.38  636.02 1137.85  673.06 1137.81
  690.26 1141.73  758.02 1153.84   819.4 1173.34   866.6 1185.33  895.51 1190.27
#Mann= 3 , 0 , 0
       0     .11       0  450.53    .052       0   483.2     .11       0
Bank Sta=450.53,483.2
Exp/Cntr=0.3,0.1

Type RM Length L Ch R = 1 ,2521.348,308.6,427.73,411.63
XS GIS Cut Line= 3
  1160890.178718   766857.256999  1161119.819121    766537.18712
  1161419.583017   766186.691155
#Sta/Elev= 30
       0 1167.57   45.41 1161.48   67.15 1160.36  103.71 1156.78  156.21 1149.75
  210.04  1137.3  241.42 1132.11  276.06 1129.73  288.24 1129.72  309.48  1127.8
  352.41 1126.11  388.66 1125.73  400.89 1121.08  401.81 1119.25  432.81 1119.25
  433.81 1121.24  445.95 1126.31  469.87 1122.69  490.02 1124.88  511.07 1128.42
  573.29 1130.82  605.53 1137.44  617.57 1137.77  647.64 1136.51  661.61 1146.94
  697.51  1160.9   711.5 1164.78  744.69 1171.69  765.56 1177.55  855.13 1197.38
#Mann= 3 , 0 , 0
       0     .11       0  400.89    .052       0  433.81     .11       0
Bank Sta=400.89,433.81
Exp/Cntr=0.3,0.1

Type RM Length L Ch R = 1 ,2093.615,219.11,295.03,305.44
BEGIN DESCRIPTION:
Ineffective area added to control expansion
END DESCRIPTION:
XS GIS Cut Line= 3
  1160980.750632   766894.402294  1161479.761107   766692.616625
  1161752.444389   766638.079954
#Sta/Elev= 30
       0 1152.76   12.74 1150.14   49.25    1145   71.25 1140.17  114.71 1134.87
  157.92 1128.51   180.3  1126.8  210.46 1126.28  302.74 1122.35   337.6 1122.21
  354.96 1120.38   503.4 1124.44  520.46 1122.07  535.11 1121.45  537.25 1117.17
  563.25 1117.17     566 1122.67  568.26 1127.19   578.1 1128.96  598.36 1128.35
     621 1145.97  647.41 1160.69  657.91 1163.96  680.93 1173.78  740.06 1193.52
  755.43 1203.74  773.21 1210.89  778.74 1214.76     792 1220.06  816.35 1231.73
#Mann= 3 , 0 , 0
       0     .11       0  535.11    .052       0     566     .11       0
#XS Ineff= 2 , 0
       0     265    1126               0
Permanent Ineff=
       F       F
Bank Sta=535.11,566
Exp/Cntr=0.3,0.1

Type RM Length L Ch R = 1 ,1798.582,342.07,353.87,354.69
XS GIS Cut Line= 3
  1160974.008633   766934.829499  1161436.131755   766968.026792
   1161796.07374   767030.743972
#Sta/Elev= 30
       0 1151.71   35.12 1140.62   46.34 1139.05   64.48 1139.34   75.14 1137.99
   85.16 1134.39  113.18 1128.63  123.85 1125.34  256.67 1121.53  306.69  1121.3
  338.08 1119.26  381.96 1121.28  445.17 1121.69  448.35 1115.34  473.35 1115.34
  476.44 1121.52  488.47 1122.88  500.08 1122.35  506.95 1125.33   520.1 1126.82
  526.09 1129.83  562.39 1131.06  579.15 1133.37  612.82 1158.52  624.92 1164.96
  681.91 1185.47  712.49 1193.44  736.98 1198.01  799.08 1212.51  828.68 1214.46
#Mann= 3 , 0 , 0
       0      .1       0  445.17    .052       0  476.44     .12       0
Bank Sta=445.17,476.44
Exp/Cntr=0.3,0.1

Type RM Length L Ch R = 1 ,1444.714,156.32,146.42,128.09
XS GIS Cut Line= 3
  1160961.662805   767246.163771   1161322.20621   767300.288076
  1161746.990692    767385.23226
#Sta/Elev= 30
       0 1163.49   57.39 1142.12   77.57 1133.36   115.2 1122.83  225.34  1117.8
  255.66 1119.62  286.91 1118.01  351.79 1120.24  360.94 1119.41  363.72 1113.85
  388.72 1113.85   391.6 1119.61  398.31 1121.18  416.71 1120.69  439.33 1125.96
  469.24 1126.62  475.31 1128.76  480.62 1128.99  492.61 1138.61  514.26 1150.81
  522.23 1153.62  535.79 1154.66   540.1  1158.1  580.37 1166.01  599.82 1175.85
  641.28 1180.44  666.58 1188.21  683.32 1187.16  779.39  1207.5  797.78 1209.84
#Mann= 3 , 0 , 0
       0      .1       0  360.94    .052       0   391.6     .12       0
Bank Sta=360.94,391.6
Exp/Cntr=0.3,0.1

Type RM Length L Ch R = 1 ,1298.291,305.12,315.02,256.7
XS GIS Cut Line= 3
  1160837.349375   767571.067207  1161285.685791   767427.599577
  1161757.933454   767457.488692
#Sta/Elev= 30
       0 1199.05   26.22  1205.3   64.76 1210.92  105.37 1210.48  149.44 1199.11
  189.44 1185.12  297.92 1138.01  320.28 1132.66  345.42 1119.75  412.91 1116.82
  461.08 1118.16  462.76  1114.8  463.54 1113.24  492.32 1114.18   544.2 1117.28
  563.05 1115.23  573.14 1118.72  602.86 1118.18   619.3 1127.57  650.63 1128.08
  661.54 1130.41  672.47 1134.25  683.67 1143.52  693.35 1154.79  743.77 1169.31
  766.01 1179.32   804.1 1184.51   824.6 1193.59  839.12 1196.73  943.92 1215.16
#Mann= 3 , 0 , 0
       0      .1       0  462.76    .052       0  492.32     .12       0
Bank Sta=462.76,492.32
Exp/Cntr=0.3,0.1

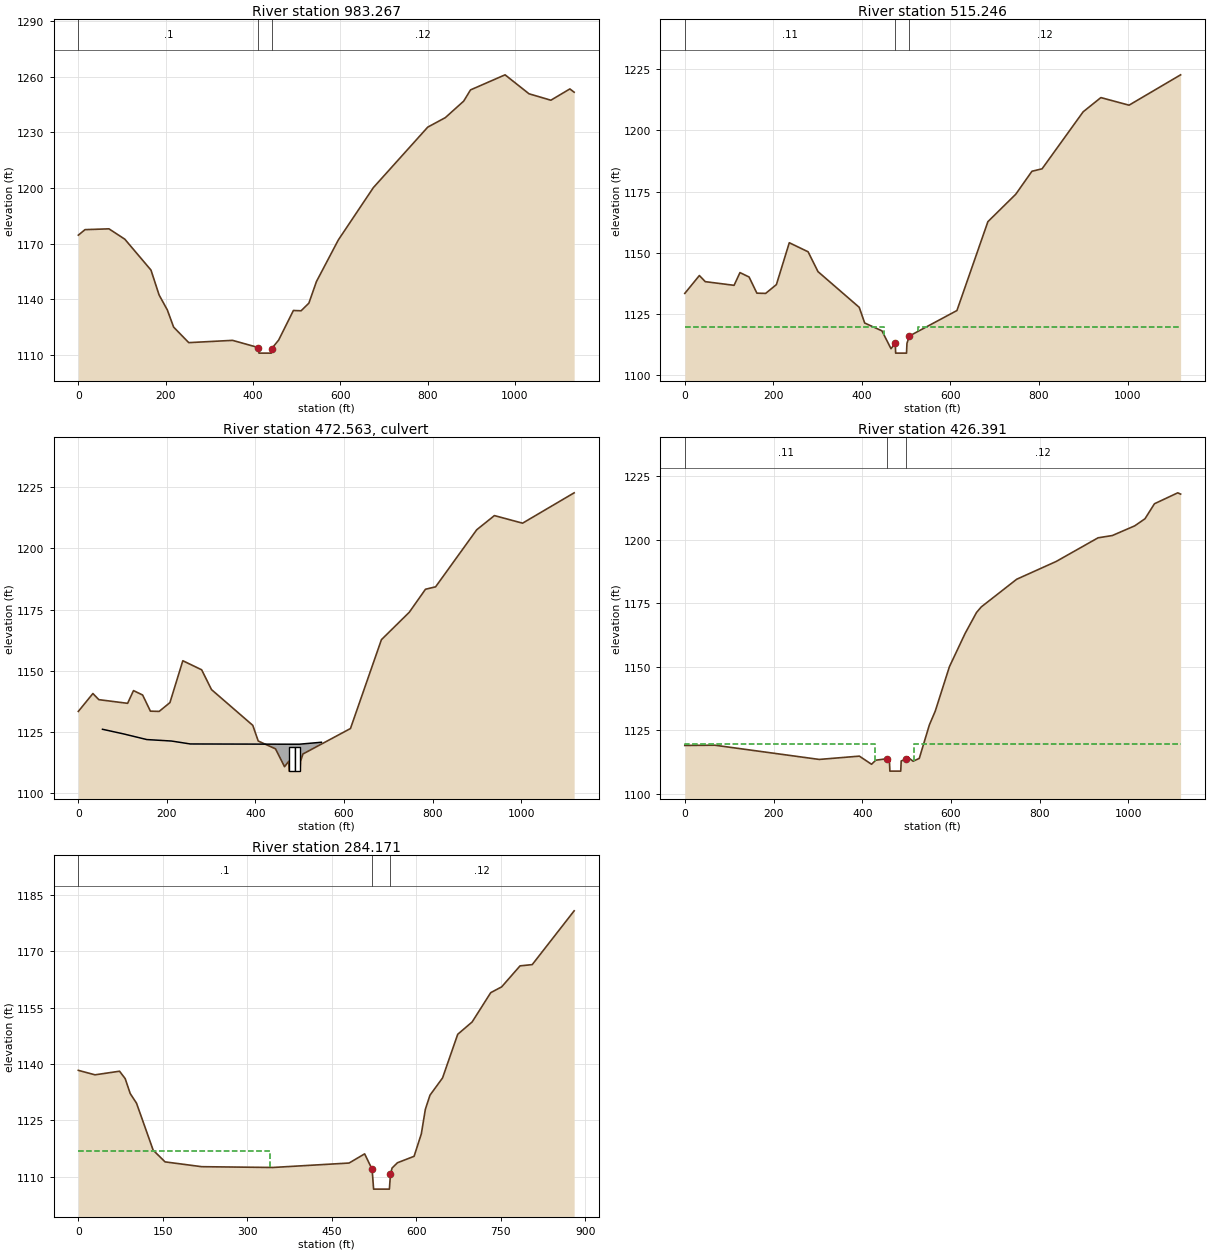
Type RM Length L Ch R = 1 ,983.267 ,351.43,468.02,490.73
XS GIS Cut Line= 3
  1161098.004483   767816.071859  1161468.763515   767660.256403
  1162134.535982   767352.876866
#Sta/Elev= 30
       0 1174.55   15.32 1177.51   70.18 1177.95  106.45 1172.37  166.36 1155.73
  184.95 1142.32   203.8 1134.25  218.23 1124.99  252.89 1116.62  353.19 1117.85
  412.22 1113.97  413.72 1110.97  441.72 1110.97  442.95 1113.44  458.68 1117.98
  492.52 1133.95  510.19 1133.79  527.96  1137.9  545.28 1149.53  595.36 1171.94
  675.56 1200.14  800.19 1232.76  840.44 1237.87  882.47 1246.76  898.14 1252.81
  977.25 1260.94 1032.12 1250.72 1082.16 1247.26 1125.68 1253.34 1135.47 1251.57
#Mann= 3 , 0 , 0
       0      .1       0  412.22    .052       0  442.95     .12       0
Bank Sta=412.22,442.95
Exp/Cntr=0.5,0.3

Type RM Length L Ch R = 1 ,515.246 ,87.69,88.85,91.01
BEGIN DESCRIPTION:
Upstream xs of Bridge 3723-39
END DESCRIPTION:
XS GIS Cut Line= 3
  1160975.844784   767833.179322  1161445.142471   767974.985648
   1162047.85761   768156.893386
#Sta/Elev= 30
       0  1133.4    32.9  1140.7    46.3  1138.2   111.3  1136.7   124.6  1141.9
   145.2  1140.1   162.8  1133.5   182.6  1133.4   206.9    1137     236  1154.1
   278.5  1150.4   300.8  1142.3     394  1127.7   406.3  1121.3   445.3  1118.1
   465.7  1110.8  475.25    1113  476.25    1109  500.75    1109  501.75    1113
   507.3    1116   614.6  1126.4   684.5  1162.7   747.4  1173.9     784  1183.3
   806.9  1184.3   899.7  1207.6   939.7  1213.4  1003.3  1210.3  1119.8  1222.7
#Mann= 3 , 0 , 0
       0     .11       0  475.25    .052       0   507.3     .12       0
#XS Ineff= 2 , 0
       0  450.48 1119.65  526.76       0 1119.75
Permanent Ineff=
       F       F
Bank Sta=475.25,507.3
Exp/Cntr=0.5,0.3

Type RM Length L Ch R = 2 ,472.563 ,,,
BEGIN DESCRIPTION:
Bridge : 3723-39 (gravel driveway)
END DESCRIPTION:
Bridge Culvert--1,0,-1,-1, 0
Deck Dist Width WeirC Skew NumUp NumDn MinLoCord MaxHiCord MaxSubmerge Is_Ogee
27.7,30,2.6,0, 8, 8, , , 0.95, 0, 0,0,,
    54.5   102.3   154.6   210.1   252.9     478     499     549
  1126.1  1124.2  1121.9  1121.3  1120.1    1120    1120  1120.8
                                                                
    -5.2    52.7   105.8   150.3   200.8     464     485   547.1
  1124.7  1125.5  1124.3  1122.7  1121.3    1120    1120  1122.9
                                                                
BR Coef=-1 , 1 , 0 ,, 0 ,,,0.8,0,1.2,0,
WSPro=,,,, 1 ,,,, 0 ,,,, 0 ,,,,-1 ,-1 ,-1 , 0 , 0 , 0 , 0 , 0
Culvert=2,10,12,30,0.015,0.4,1,8,1,1109,482.25,1109,468.25,Culvert #1  , 0 ,27.7
Culvert Bottom n=0.015
Culvert=2,10,12,30,0.015,0.4,1,8,1,1109,494.75,1109,480.75,Culvert #2  , 0 ,27.7
Culvert Bottom n=0.015
BC Design=,, 0 ,, 0 ,,,,,,

Type RM Length L Ch R = 1 ,426.391 ,151.77,142.22,133.1
BEGIN DESCRIPTION:
Down stream xs of Bridge 3723-39
END DESCRIPTION:
XS GIS Cut Line= 3
   1160946.54784   767909.351198  1161401.706982   768052.548899
   1162018.06195   768226.665779
#Sta/Elev= 30
       0  1119.1    67.6  1119.2     303  1113.6   393.5  1114.9   420.9  1111.7
   430.5  1113.3  456.321113.898  461.25    1113  462.25    1109  486.75    1109
  487.75    1113   497.9  1113.7   502.4  1114.5   514.6  1112.9   528.5    1114
   551.3  1127.2   564.5  1132.6   596.5  1150.1   631.9  1163.2   657.5  1171.4
   668.2  1173.6   748.1  1184.5   837.2  1191.5   931.5  1200.8   963.7  1201.7
  1014.1  1205.5  1037.3  1208.3  1058.6  1214.2  1111.1  1218.5  1117.6    1218
#Mann= 3 , 0 , 0
       0     .11       0  456.32    .053       0   497.9     .12       0
#XS Ineff= 2 , 0
          428.86 1119.77  516.66         1119.86
Permanent Ineff=
       F       F
Bank Sta=456.32,497.9
Exp/Cntr=0.5,0.3

Type RM Length L Ch R = 1 ,284.171 ,304.53,284.17,297.35
BEGIN DESCRIPTION:
Ineffective area added to control expansion
END DESCRIPTION:
XS GIS Cut Line= 3
  1160888.038306   768197.828557  1161417.043927   768178.740656
  1161766.078593   768216.916311
#Sta/Elev= 30
       0 1138.34   29.65 1137.15   73.16 1138.11   83.19 1136.15   92.13 1132.17
  103.34  1129.6  132.88 1117.11     154 1113.99     219 1112.71  345.41  1112.5
  480.79 1113.68  508.43 1116.12  521.71 1112.01  524.34 1106.74  552.34 1106.74
  554.32 1110.71  557.13 1112.35   566.6 1113.75  596.21 1115.47  609.11 1121.46
  616.23 1127.98  624.48 1131.74  646.77 1136.32   673.7 1147.93  699.29 1151.21
  732.33 1159.01  751.73 1160.55  784.39 1166.14  806.02 1166.47  880.47 1180.78
#Mann= 3 , 0 , 0
       0      .1       0  521.71    .053       0  554.32     .12       0
#XS Ineff= 2 , 0
       0     340    1117               0
Permanent Ineff=
       F       F
Bank Sta=521.71,554.32
Exp/Cntr=0.3,0.1

Chan Stop Cuts=-1
Chan Mod River=RussellCreek
Chan Mod Reach=Main
Chan Mod RS=14557.87,0,250.6,272.93,299.19,454.38,25,1204.25,0.5,0.5,,,,1204.25,,,,,,1204.25,,,
Chan Mod RS=14284.95,0,382.45,452.1,467.71,446.84,25,1200.05,0.5,0.5,,,,1200.05,,,,,,1200.05,,,
Chan Mod RS=13832.85,0,416.11,409.87,350.92,405.47,26,1194.06,0.5,0.5,,,,1194.06,,,,,,1194.06,,,
Chan Mod RS=13422.98,0,243.51,342.76,365.82,380.01,26,1188.98,0.5,0.5,,,,1188.98,,,,,,1188.98,,,
Chan Mod RS=13080.22,0,49.22,37.39,35.83,548.35,25,1186.14,0.5,0.5,,,,1186.14,,,,,,1186.14,,,
Chan Mod RS=13042.83,0,51.93,45.63,47.78,528.09,22,1185.85,0.5,0.5,,,,1185.85,,,,,,1185.85,,,
Chan Mod RS=12997.2 ,0,461.68,439.33,329.91,497.57,27,1185.39,0.5,0.5,,,,1185.39,,,,,,1185.39,,,
Chan Mod RS=12557.87,0,439.93,500,448.74,372.95,22,1179.71,0.5,0.5,,,,1179.71,,,,,,1179.71,,,
Chan Mod RS=12057.87,0,239.71,219.02,228.37,615.03,24,1176.01,0.5,0.5,,,,1176.01,,,,,,1176.01,,,
Chan Mod RS=11838.85,0,49.04,30.87,32.37,813.24,24,1174.71,0.5,0.5,,,,1174.71,,,,,,1174.71,,,
Chan Mod RS=11807.98,0,61.64,45.12,44.75,834.73,22,1174.19,0.5,0.5,,,,1174.19,,,,,,1174.19,,,
Chan Mod RS=11762.86,0,235.21,499.12,405.71,867.13,24,1173.34,0.5,0.5,,,,1173.34,,,,,,1173.34,,,
Chan Mod RS=11263.74,0,196.53,205.87,202.2,565.35,24,1168.6,0.5,0.5,,,,1168.6,,,,,,1168.6,,,
Chan Mod RS=11057.87,0,410.89,500,482.81,476.31,26,1167.67,0.5,0.5,,,,1167.67,,,,,,1167.67,,,
Chan Mod RS=10557.87,0,437.46,500,524.14,648.6,26,1164.76,0.5,0.5,,,,1164.76,,,,,,1164.76,,,
Chan Mod RS=10057.87,0,407.75,404.54,360.44,441.51,26,1158.64,0.5,0.5,,,,1158.64,,,,,,1158.64,,,
Chan Mod RS=9653.334,0,814.08,792.46,726.45,687.81,26,1156.86,0.5,0.5,,,,1156.86,,,,,,1156.86,,,
Chan Mod RS=8860.876,0,422.05,412.28,394.2,474.76,26,1152.01,0.5,0.5,,,,1152.01,,,,,,1152.01,,,
Chan Mod RS=8448.592,0,329.89,352.1,339.4,371.47,26,1149.76,0.5,0.5,,,,1149.76,,,,,,1149.76,,,
Chan Mod RS=8096.487,0,470.87,538.62,563.86,567.53,27,1147.56,0.5,0.5,,,,1147.56,,,,,,1147.56,,,
Chan Mod RS=7557.872,0,485.34,500,454.45,460.51,29,1145.32,0.5,0.5,,,,1145.32,,,,,,1145.32,,,
Chan Mod RS=7057.872,0,502.72,511.74,475.86,390.83,24,1142.11,0.5,0.5,,,,1142.11,,,,,,1142.11,,,
Chan Mod RS=6546.136,0,480.92,488.26,472.97,452.86,27,1139.44,0.5,0.5,,,,1139.44,,,,,,1139.44,,,
Chan Mod RS=6057.872,0,277.34,272.93,247.23,435.84,21,1138.13,0.5,0.5,,,,1138.13,,,,,,1138.13,,,
Chan Mod RS=5784.938,0,691.85,689.78,557.02,438.04,28,1136,0.5,0.5,,,,1136,,,,,,1136,,,
Chan Mod RS=5095.153,0,452.55,440.37,363.04,397.88,25,1131.67,0.5,0.5,,,,1131.67,,,,,,1131.67,,,
Chan Mod RS=4654.779,0,419.35,485.66,506.18,281.82,28,1130.47,0.5,0.5,,,,1130.47,,,,,,1130.47,,,
Chan Mod RS=4169.122,0,372.81,501.62,538.96,434.78,26,1126.98,0.5,0.5,,,,1126.98,,,,,,1126.98,,,
Chan Mod RS=3667.499,0,35.92,38.51,36.76,561.92,28,1124.58,0.5,0.5,,,,1124.58,,,,,,1124.58,,,
Chan Mod RS=3628.988,0,31.54,32.01,29.95,510.38,25,1124.54,0.5,0.5,,,,1124.54,,,,,,1124.54,,,
Chan Mod RS=3596.973,0,359.23,345.16,215.78,466.06,28,1124.5,0.5,0.5,,,,1124.5,,,,,,1124.5,,,
Chan Mod RS=3251.816,0,461.36,484.53,287.7,689.85,29,1122.83,0.5,0.5,,,,1122.83,,,,,,1122.83,,,
Chan Mod RS=2767.285,0,145.19,245.94,150.81,466.87,29,1120.32,0.5,0.5,,,,1120.32,,,,,,1120.32,,,
Chan Mod RS=2521.348,0,308.6,427.73,411.63,417.31,23,1119.25,0.5,0.5,,,,1119.25,,,,,,1119.25,,,
Chan Mod RS=2093.615,0,219.11,295.03,305.44,550.25,26,1117.17,0.5,0.5,,,,1117.17,,,,,,1117.17,,,
Chan Mod RS=1798.582,0,342.07,353.87,354.69,460.85,25,1115.34,0.5,0.5,,,,1115.34,,,,,,1115.34,,,
Chan Mod RS=1444.714,0,156.32,146.42,128.09,376.22,25,1113.85,0.5,0.5,,,,1113.85,,,,,,1113.85,,,
Chan Mod RS=1298.291,0,305.12,315.02,256.7,477.54,28,1113.24,0.5,0.5,,,,1113.24,,,,,,1113.24,,,
Chan Mod RS=983.267 ,0,351.43,468.02,490.73,427.72,28,1110.97,0.5,0.5,,,,1110.97,,,,,,1110.97,,,
Chan Mod RS=515.246 ,0,44.2,42.68,45.35,479.63,28,1109.1,0.5,0.5,,,,1109.1,,,,,,1109.1,,,
Chan Mod RS=472.563 ,0,52.33,46.17,45.66,478.68,26,1108.36,0.5,0.5,,,,1108.36,,,,,,1108.36,,,
Chan Mod RS=426.391 ,0,172.65,142.22,133.1,480.93,27,1107.86,0.5,0.5,,,,1107.86,,,,,,1107.86,,,
Chan Mod RS=284.171 ,0,304.53,284.17,297.35,538.34,28,1106.74,0.5,0.5,,,,1106.74,,,,,,1106.74,,,
Use User Specified Reach Order=0
User Specified Reach Order=RussellCreek    ,Main