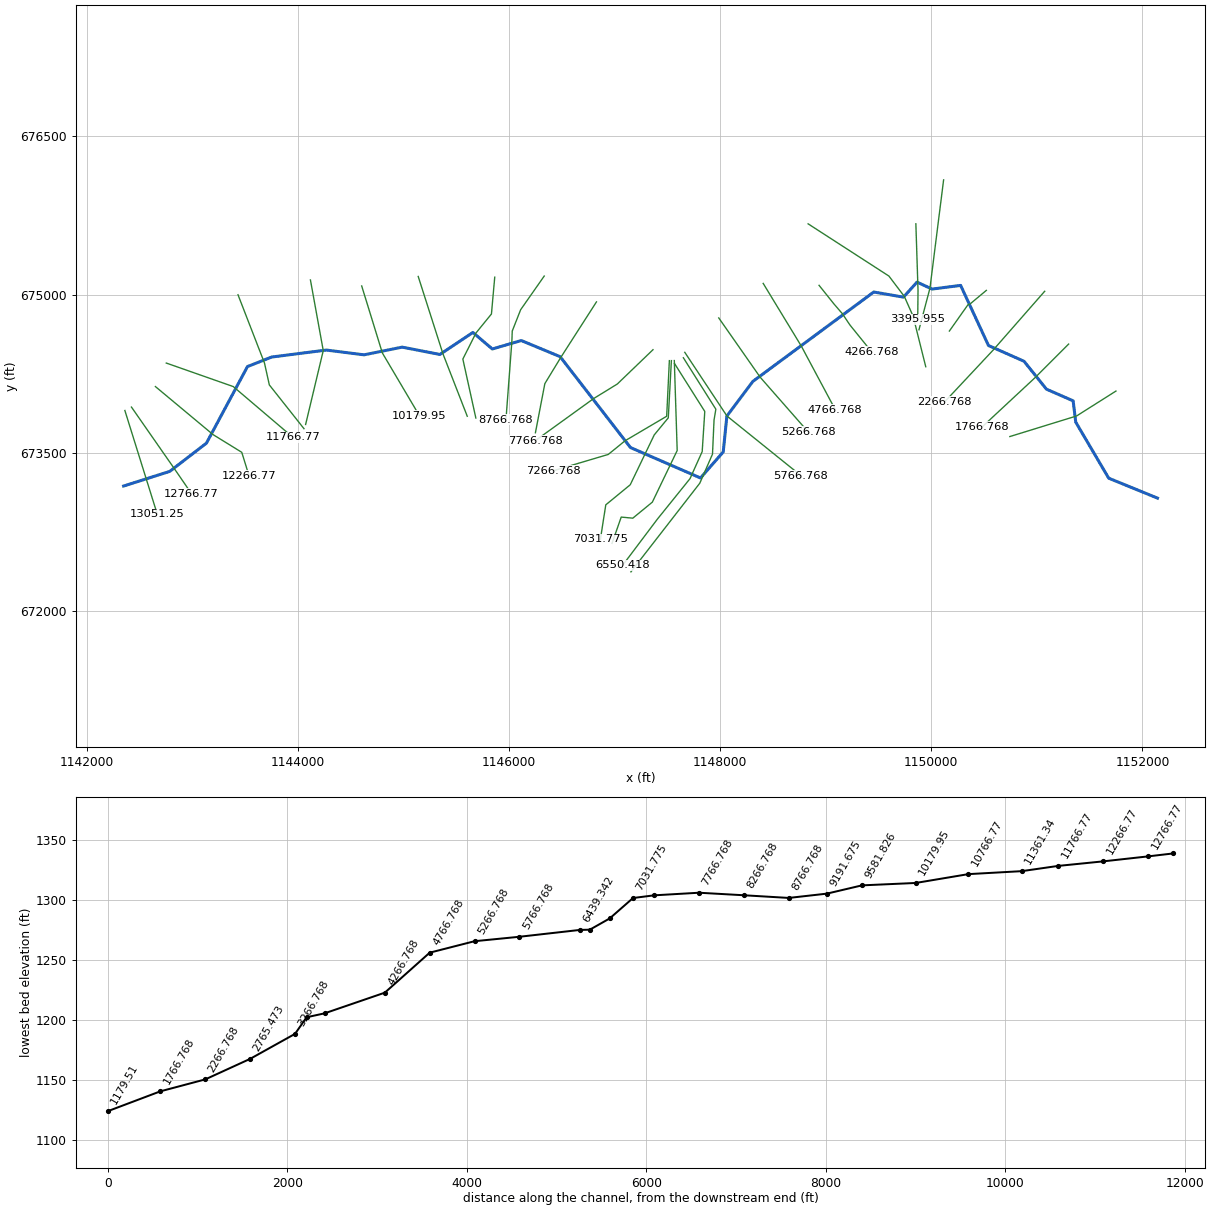
--- ShoalCr.prj (project) ---

Proj Title=ShoalCr
Current Plan=p01
Default Exp/Contr=0.3,0.1
English Units
Geom File=g01
Flow File=f01
Plan File=p01
Y Axis Title=Elevation
X Axis Title(PF)=Main Channel Distance
X Axis Title(XS)=Station
BEGIN DESCRIPTION:
END DESCRIPTION:
DSS Export Rating Curves= 0
DSS Export Rating Curve Sorted= 0
DSS Export Volume Flow Curves= 0
DXF OffsetX= 0
DXF OffsetY= 0
DXF ScaleX= 1
DXF ScaleY= 10

--- ShoalCr.p01 (plan) ---

Plan Title=LDS Shoal Creek
Program Version=3.12
Short Identifier=100 Yr
Geom File=g01
Flow File=f01
Subcritical Flow
K Sum by GR= 0
Std Step Tol= 0.01
Critical Tol= 0.01
Num of Std Step Trials= 20
Max Error Tol= 0.3
Flow Tol Ratio= 0.001
Split Flow NTrial= 30
Split Flow Tol= 0.02
Split Flow Ratio= 0.02
Log Output Level= 0
Friction Slope Method= 1
Unsteady Friction Slope Method= 2
Unsteady Bridges Friction Slope Method= 1
Parabolic Critical Depth
Global Vel Dist= 0 , 0 , 0
Global Log Level= 0
CheckData=True
Encroach Param=-1 ,0,0, 2
Encroach River=ShoalCr
Encroach Reach=Main
Encroach Node=13051.25
       1  661.56   702.2
Encroach Node=12766.77
       1685.7297  752.16
Encroach Node=12266.77
       1     655     745
Encroach Node=11766.77
       1629.0177714.8654
Encroach Node=11361.34
       1   675.5714.8838
Encroach Node=10766.77
       1618.5079726.0975
Encroach Node=10179.95
       1607.4605711.0921
Encroach Node=9581.826
       1726.6333818.2716
Encroach Node=9191.675
       1558.1959686.4015
Encroach Node=8766.768
       1     664     786
Encroach Node=8266.768
       1  425.94  972.59
Encroach Node=7766.768
       1570.4293  914.85
Encroach Node=7266.768
       1  727.96 1319.33
Encroach Node=7031.775
       1797.26611489.673
Encroach Node=6771.772
       1948.11521017.868
Encroach Node=6550.418
       1 1146.65 1203.15
Encroach Node=6439.342
       1  1162.21268.794
Encroach Node=5766.768
       1  707.43 771.606
Encroach Node=5266.768
       1     670697.5383
Encroach Node=4766.768
       1676.2844715.9014
Encroach Node=4266.768
       1  338.81  370.17
Encroach Node=3595.638
       1 1139.861209.796
Encroach Node=3395.955
       1522.7901582.2205
Encroach Node=3266.768
       11024.1231071.766
Encroach Node=2765.473
       1186.9616233.0465
Encroach Node=2266.768
       1686.5122766.3674
Encroach Node=1766.768
       1415.5375456.7918
Encroach Node=1179.51
       1446.9191 490.163
Encroach Node=851.703
       1496.2752  536.65
Encroach Node=266.768
       1318.6381  383.37
Encroach Node=76.626
       1371.5253     755
Computation Interval=1HOUR
Output Interval=1HOUR
Run HTab= 0
Run UNet= 0
Run PostProcess= 0
UNET Theta= 1
UNET Theta Warmup= 1
UNET ZTol= 0.02
UNET ZSATol= 0.05
UNET MxIter= 20
UNET MaxInSteps= 0
UNET DtIC= 0
UNET DtMin= 0
UNET MaxCRTS= 20
UNET WFStab= 2
UNET SFStab= 1
UNET WFX= 1
UNET SFX= 1
UNET DSS MLevel= 4
UNET DZMax Abort= 100
UNET Convert EG Bridges=-1
UNET Use Existing IB Tables=-1
UNET Froude Reduction=False
UNET Froude Limit= 1
UNET Froude Power= 10
Instantaneous Interval=1HOUR
Write IC File= 0
Echo Input=False
Echo Output=False
Write Detailed= 0
Detailed Automatic Start=False, 10

--- ShoalCr.f01 (steady flow) ---

Flow Title=ShoalCr
Program Version=3.12
Number of Profiles= 2
Profile Names=P100yr,Encroachments
River Rch & RM=ShoalCr,Main            ,13051.25
    1120    1120
River Rch & RM=ShoalCr,Main            ,10766.77
    1240    1240
River Rch & RM=ShoalCr,Main            ,6771.772
    1490    1490
Boundary for River Rch & Prof#=ShoalCr,Main            , 1
Up Type= 0
Dn Type= 3
Dn Slope=0.06
Gate Openings=ShoalCr         ,Main            ,6922    ,Gate #1     ,
    4.43       1       0       0
DSS Import GetInterval= 0
DSS Import GetPeak= 0
DSS Import FillOption= 0

--- ShoalCr.g01 (geometry) ---

Geom Title=ShoalCr
Program Version=3.12

River Reach=ShoalCr         ,Main
Reach XY= 30
  1142347.879314   673188.249335  1142785.381271   673327.128315
  1143132.631964   673594.498814  1143521.502117   674320.191239
   1143750.74702    674410.49981  1144268.129172   674476.441325
  1144625.750934   674431.311606  1144986.878867   674504.249071
   1145344.50063   674434.809603   1145656.99676   674643.132138
  1145841.001372   674486.877921   1146115.24903   674566.749941
  1146483.381132   674413.940456  1147150.001072   673552.809696
  1147813.249935   673264.631533  1148028.498851   673511.190279
  1148063.249327   673851.440891   1148309.00111   674179.251958
  1149454.881693   675026.439908  1149736.129432   674977.808105
  1149864.629168   675120.189169  1150007.002014   675054.247654
  1150277.751719   675088.940778  1150541.628307   674519.498483
  1150878.499757   674370.191082  1151090.246545   674106.310407
  1151343.752108   673995.189995  1151368.131469   673793.810145
  1151680.631731   673262.558971  1152142.631839   673073.880812

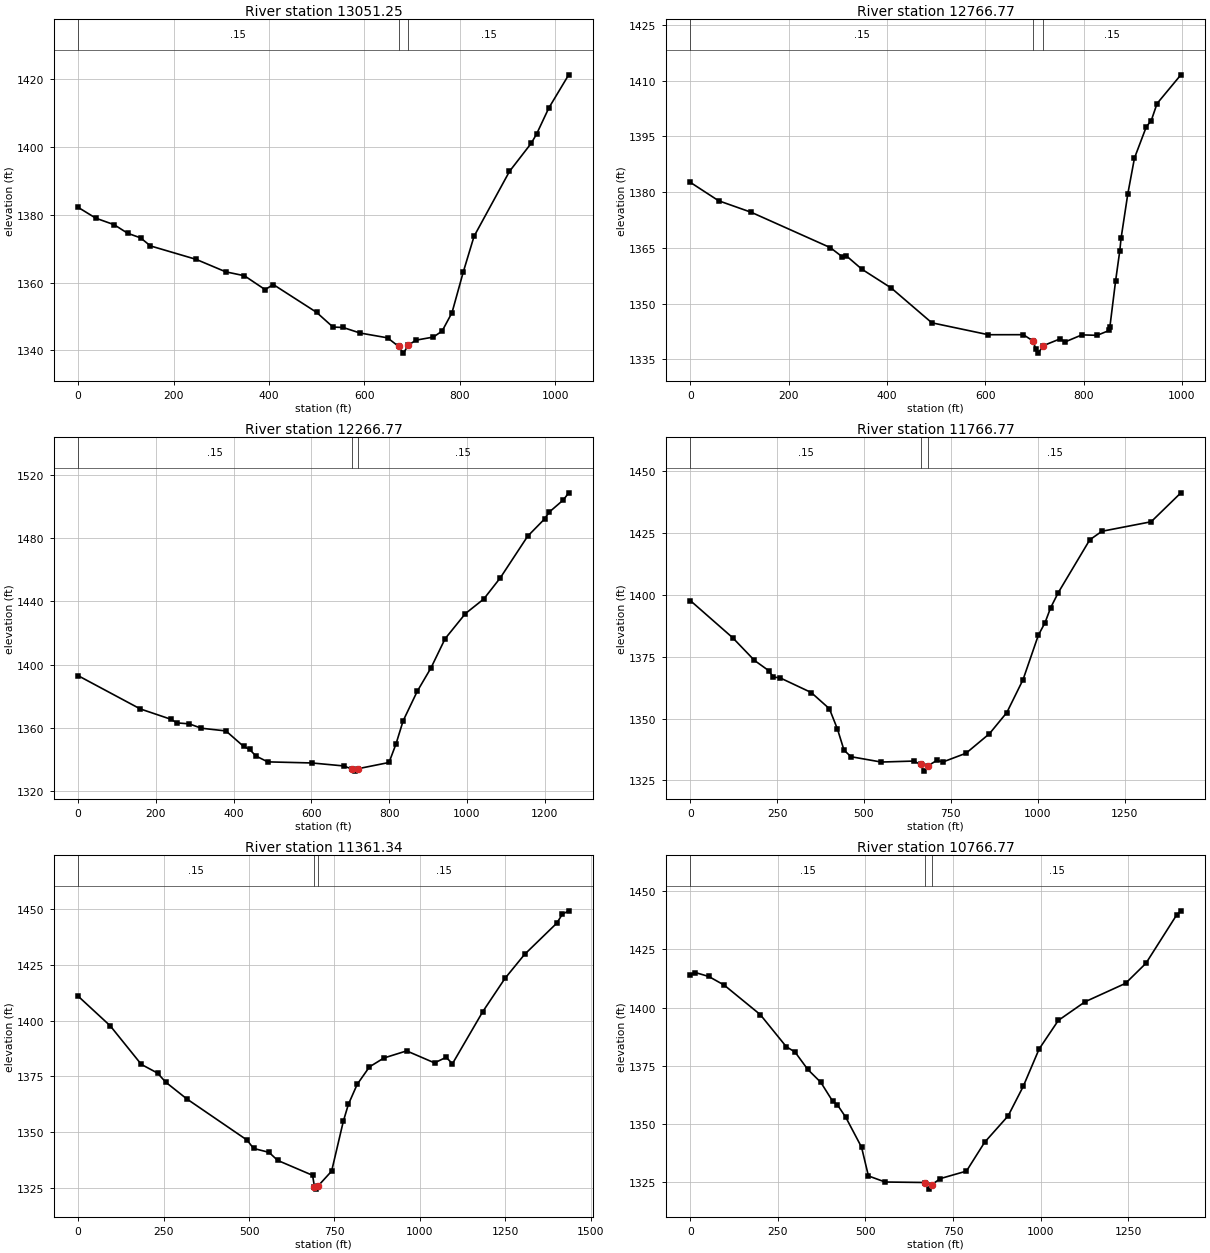
Type RM Length L Ch R = 1 ,13051.25,275.29,284.48,293.44
XS GIS Cut Line= 3
  1142359.924239   673903.951583  1142563.477759   673252.512997
  1142666.592107    672922.51311
#Sta/Elev= 30
       0 1382.21   37.26    1379   75.47 1377.09     104 1374.55  131.03  1373.2
   151.6 1370.83  247.44 1366.86  309.37 1363.19  348.58 1362.03  391.97 1357.94
  409.13 1359.44  499.71 1351.25  534.19  1346.9  555.52 1346.77  590.91 1345.14
  648.56 1343.72  671.56 1341.21  681.88 1339.21   692.2 1341.58  708.37 1343.04
  744.71 1343.95  762.99 1345.73  783.65 1351.14  807.06 1363.03  829.87 1373.66
  904.13 1392.81  949.55 1401.07  960.93 1403.82  986.47 1411.48 1028.23 1421.28
#Mann= 3 , 0 , 0
       0     .15       0  671.56     .05       0   692.2     .15       0
Bank Sta=671.56,692.2
Exp/Cntr=0.3,0.1

Type RM Length L Ch R = 1 ,12766.77,491.55,500,512.44
XS GIS Cut Line= 3
  1142422.255275   673936.369305  1142826.797403   673355.560531
  1142990.964395   673116.424738
#Sta/Elev= 30
       0 1382.66    57.6  1377.7  124.14 1374.59  284.66  1365.1  309.49 1362.59
  317.02 1362.93   349.1 1359.28  408.87 1354.22  491.28 1344.87   606.3 1341.66
  677.47 1341.67  697.58 1339.94  702.77 1337.72  707.81 1336.71  717.82 1338.71
  752.16 1340.54  762.44 1339.73  796.54 1341.62  827.53  1341.5   851.9  1342.8
  853.48 1343.78  865.03 1356.09  873.68  1364.3  876.19 1367.58  889.97 1379.59
  903.51  1389.2  927.53 1397.58  937.66 1399.28  949.39 1403.84  997.87 1411.57
#Mann= 3 , 0 , 0
       0     .15       0  697.58     .05       0  717.82     .15       0
Bank Sta=697.58,717.82
Exp/Cntr=0.3,0.1

Type RM Length L Ch R = 1 ,12266.77,489.2,500,494.82
XS GIS Cut Line= 4
  1142649.260982   674130.781459  1143195.563258   673675.433814
  1143467.400998   673507.728354  1143535.838303   673286.926027
#Sta/Elev= 30
       0 1392.99  159.83 1371.94  239.17 1365.35  254.34 1363.09  285.67 1362.49
  317.13 1359.71  380.33    1358  425.65 1348.21  441.18 1346.28  457.27 1342.15
   487.7 1338.42  601.18 1337.73  683.35 1335.84   703.6 1333.93  711.19 1332.56
  719.93 1334.09  799.71 1338.03  817.56 1349.73  835.98  1364.4  872.11 1383.02
  907.66 1397.93  943.93 1416.39  996.17 1432.28  1043.4 1441.52 1085.83 1454.89
 1156.22 1481.25 1199.56 1492.13 1211.64 1496.49 1248.26 1504.28 1261.76 1508.71
#Mann= 3 , 0 , 0
       0     .15       0   703.6     .05       0  719.93     .15       0
Bank Sta=703.6,719.93
Exp/Cntr=0.3,0.1

Type RM Length L Ch R = 1 ,11766.77,431.52,405.43,385.95
XS GIS Cut Line= 3
  1142752.520241   674353.311395  1143386.937294   674130.623309
  1143950.440665   673651.080973
#Sta/Elev= 30
       0 1397.76  122.31 1382.69  184.74 1373.55  225.31 1369.46  239.29  1366.8
  258.43  1366.5  348.17 1360.56  400.49 1354.01  423.83 1345.74  442.63 1337.25
  462.68 1334.61  549.74 1332.45  643.31 1332.85  663.02 1331.47  672.37 1328.78
  684.23 1330.91  709.76 1333.13  727.25 1332.48  793.87 1336.02  861.23 1343.91
  911.32 1352.48  957.85 1365.74    1002 1383.73 1021.34 1388.84 1037.32 1394.82
 1059.43 1400.97 1150.01  1422.3 1184.92 1425.75 1326.66  1429.6  1412.3  1441.3
#Mann= 3 , 0 , 0
       0     .15       0  663.02     .05       0  684.23     .15       0
Bank Sta=663.02,684.23
Exp/Cntr=0.3,0.1

Type RM Length L Ch R = 1 ,11361.34,598.98,594.57,577.29
XS GIS Cut Line= 4
  1143431.671638   675000.467676  1143682.675592   674353.275278
  1143728.546616   674146.301014  1144056.863941   673731.663379
#Sta/Elev= 30
       0 1410.96   93.99 1397.65  184.94 1380.35  232.43 1376.45  256.33 1372.38
  317.66 1364.91   494.3  1346.4  513.27 1342.66  558.52  1340.9  583.69  1337.3
  685.95  1330.6  691.41 1325.44  695.82 1324.41  702.26 1325.87  741.61 1332.48
  775.77 1354.79  790.51 1362.38  816.38  1371.4   852.3 1379.24  894.45 1383.21
     961  1386.4 1042.61 1381.02 1076.59 1383.52 1094.99 1380.64 1183.86 1404.04
 1248.62  1418.9 1305.78 1429.64 1399.77 1443.62 1416.51 1447.68 1435.04 1449.21
#Mann= 3 , 0 , 0
       0     .15       0  691.41     .05       0  702.26     .15       0
Bank Sta=691.41,702.26
Exp/Cntr=0.3,0.1

Type RM Length L Ch R = 1 ,10766.77,580.78,586.82,608.84
XS GIS Cut Line= 3
  1144117.915252   675140.789329  1144239.408733   674471.229936
  1144072.296646   673771.300993
#Sta/Elev= 30
       0 1414.08   14.07 1415.09   52.42 1413.41    96.6  1409.7  199.79 1396.99
  274.06 1383.18  298.94  1380.9  335.43 1373.39   372.5 1367.87  406.07 1359.81
  419.63 1358.24  443.77 1352.83  488.75 1339.99  508.45  1327.6  556.07 1324.99
  670.89 1324.78  680.49 1321.93  689.76 1323.91  713.85 1326.47  788.18 1329.68
  840.13 1342.09  907.11 1353.43  950.09 1366.08  995.48 1382.17 1050.35 1394.49
 1126.77 1402.51 1242.14 1410.43 1300.34 1419.05 1388.67    1440 1400.09 1441.62
#Mann= 3 , 0 , 0
       0     .15       0  670.89     .05       0  689.76     .15       0
Bank Sta=670.89,689.76
Exp/Cntr=0.3,0.1

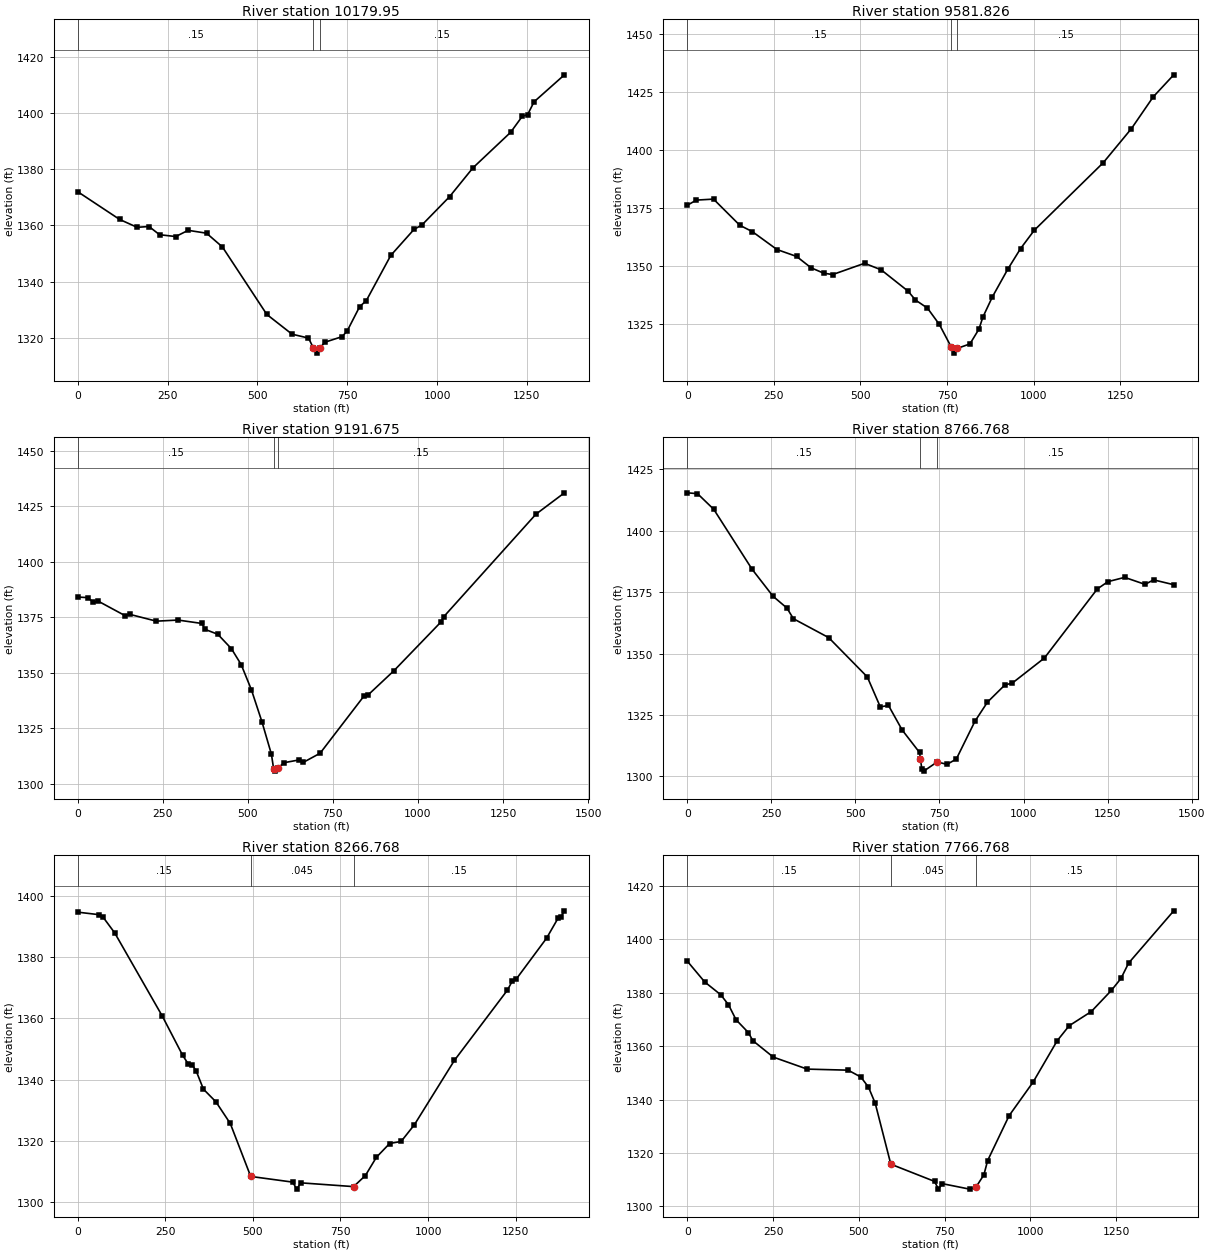
Type RM Length L Ch R = 1 ,10179.95,597.65,598.12,592.64
XS GIS Cut Line= 3
   1144603.54662      675083.801  1144799.187944   674449.120867
  1145150.421612   673854.634361
#Sta/Elev= 30
       0 1371.93  116.32  1362.1  165.04  1359.3  198.13 1359.59  227.39 1356.67
  272.48 1356.02   307.1 1358.23  358.19 1357.21  402.43 1352.32  526.04 1328.32
  596.23  1321.3   642.1 1319.91  655.68 1316.42  664.62 1314.56  673.61 1316.35
  687.75 1318.44  735.53 1320.42  749.74 1322.42  784.65 1331.12  802.91  1333.2
  871.15  1349.3  935.81 1358.55  958.25 1360.17  1034.8 1370.19 1099.95 1380.45
 1204.83 1393.08 1237.32 1398.78 1252.14 1399.37 1270.08 1403.93 1354.64 1413.53
#Mann= 3 , 0 , 0
       0     .15       0  655.68     .05       0  673.61     .15       0
Bank Sta=655.68,673.61
Exp/Cntr=0.3,0.1

Type RM Length L Ch R = 1 ,9581.826,419.93,390.15,363.54
XS GIS Cut Line= 3
  1145138.978056   675173.772037  1145373.520665   674440.405261
  1145603.546632   673849.426036
#Sta/Elev= 30
       0 1376.13   26.48 1378.37   76.01  1378.8  151.83 1367.55  188.15  1364.8
  259.02 1357.12  315.75 1354.14   357.7 1349.24  393.69 1346.96  419.66 1346.34
  511.89  1351.2   559.8 1348.38  637.38 1339.22  658.83 1335.39  693.34 1331.93
  727.75 1324.89  762.67 1314.99  770.45 1312.56  778.79 1314.56  815.95 1316.52
   841.9 1322.86  853.46  1328.1  880.88 1336.79  925.07 1348.62  962.06 1357.52
 1001.59 1365.39 1200.74 1394.46 1282.17 1409.15 1344.89 1422.77 1404.13 1432.25
#Mann= 3 , 0 , 0
       0     .15       0  762.67     .05       0  778.79     .15       0
Bank Sta=762.67,778.79
Exp/Cntr=0.3,0.1

Type RM Length L Ch R = 1 ,9191.675,405.94,424.91,425.81
XS GIS Cut Line= 5
  1145863.963294   675167.134367  1145832.713304   674818.176013
  1145686.257396   674638.321898  1145561.879948   674391.092659
  1145684.873008   673833.018044
#Sta/Elev= 30
       0  1384.1    29.5 1383.84   45.64 1381.69   60.28 1382.21  139.75 1375.64
  152.24 1376.32  230.72 1373.24  294.72 1373.73  364.37 1372.21  374.39 1369.51
  411.44 1367.33  451.47 1360.83  480.06  1353.7  510.14 1342.36   541.2 1327.91
  569.07 1313.27  575.61 1306.67  580.49 1305.67  587.35 1307.04  606.94 1309.49
  650.07 1310.71  662.11 1309.56  712.22 1313.73  842.33 1339.73  852.14 1339.83
  929.38 1350.93 1067.76  1372.9 1075.62 1375.22 1346.74 1421.43 1430.52 1431.06
#Mann= 3 , 0 , 0
       0     .15       0  575.61     .05       0  587.35     .15       0
Bank Sta=575.61,587.35
Exp/Cntr=0.3,0.1

Type RM Length L Ch R = 1 ,8766.768,574.87,500,438.68
XS GIS Cut Line= 5
  1146332.713287   675177.551016  1146109.299934   674858.519614
  1146029.813204   674656.560163  1146026.341595    674559.76954
    1145970.3453    673818.52744
#Sta/Elev= 30
       0 1415.48   30.61 1415.15   78.98 1408.76  193.04 1384.32  255.45  1373.3
  296.52 1368.54  315.79 1364.19  420.74 1356.48  535.56 1340.46  574.16 1328.26
  598.56 1328.84  639.17 1318.84  690.91 1309.68   693.6 1307.08  697.47 1303.08
  703.37 1302.08  743.16 1305.81  772.67 1304.85  800.19 1306.99  855.74 1322.43
  892.94 1330.21  944.47 1337.17  966.94 1337.98 1062.19 1348.17 1219.51 1376.32
 1251.15 1379.29  1300.8 1381.03  1361.5 1378.17 1386.71 1380.02 1446.73 1378.04
#Mann= 3 , 0 , 0
       0     .15       0   693.6    .045       0  743.16     .15       0
Bank Sta=693.6,743.16
Exp/Cntr=0.3,0.1

Type RM Length L Ch R = 1 ,8266.768,593.2,500,443.54
XS GIS Cut Line= 4
  1146827.504946   674932.759326  1146489.725158   674406.670543
  1146338.663316   674158.307023  1146249.379964   673693.175994
#Sta/Elev= 30
       0 1394.69   60.17 1393.88   72.27 1393.02  105.18 1387.93  241.34 1360.73
   299.3 1347.97  314.94 1345.21   326.8 1344.87  338.43 1342.71  358.63 1336.92
  394.14 1332.82  435.27 1325.73  493.61 1308.45  613.38  1306.6  625.19 1304.31
  636.67 1306.36  787.44 1305.13  821.09 1308.74   852.6 1314.71  890.35  1319.2
   923.2 1319.87  960.99 1325.31 1075.54 1346.36 1226.35 1369.19 1240.76 1372.22
 1252.22  1372.9 1338.43 1386.18 1371.38 1392.73 1378.63 1392.96 1389.51 1395.13
#Mann= 3 , 0 , 0
       0     .15       0  493.61    .045       0  787.44     .15       0
Bank Sta=493.61,787.44
Exp/Cntr=0.3,0.1

Type RM Length L Ch R = 1 ,7766.768,583.64,500,522.47
XS GIS Cut Line= 4
  1147363.124918   674479.821288  1147025.152684    674154.76518
   1146801.04405   674017.064859  1146245.096771   673615.896652
#Sta/Elev= 30
       0  1391.9   51.09 1384.06   97.86 1379.25  120.32 1375.53  142.35  1369.9
  178.07 1365.11   191.3 1362.06   250.8  1355.9  349.56  1351.4  468.92    1351
  505.93 1348.43  528.14 1344.65  547.81  1338.6  593.23 1315.77  720.57 1309.32
  731.95 1306.45  743.32 1308.47  822.76 1306.42  841.04 1307.12  864.36 1311.76
  875.33 1317.12  937.93 1333.96 1007.87 1346.55    1078 1362.04 1112.94 1367.66
 1177.34 1372.97 1236.12 1380.94  1263.9  1385.4 1285.93 1391.11 1417.53 1410.72
#Mann= 3 , 0 , 0
       0     .15       0  593.23    .045       0  841.04     .15       0
Bank Sta=593.23,841.04
Exp/Cntr=0.3,0.1

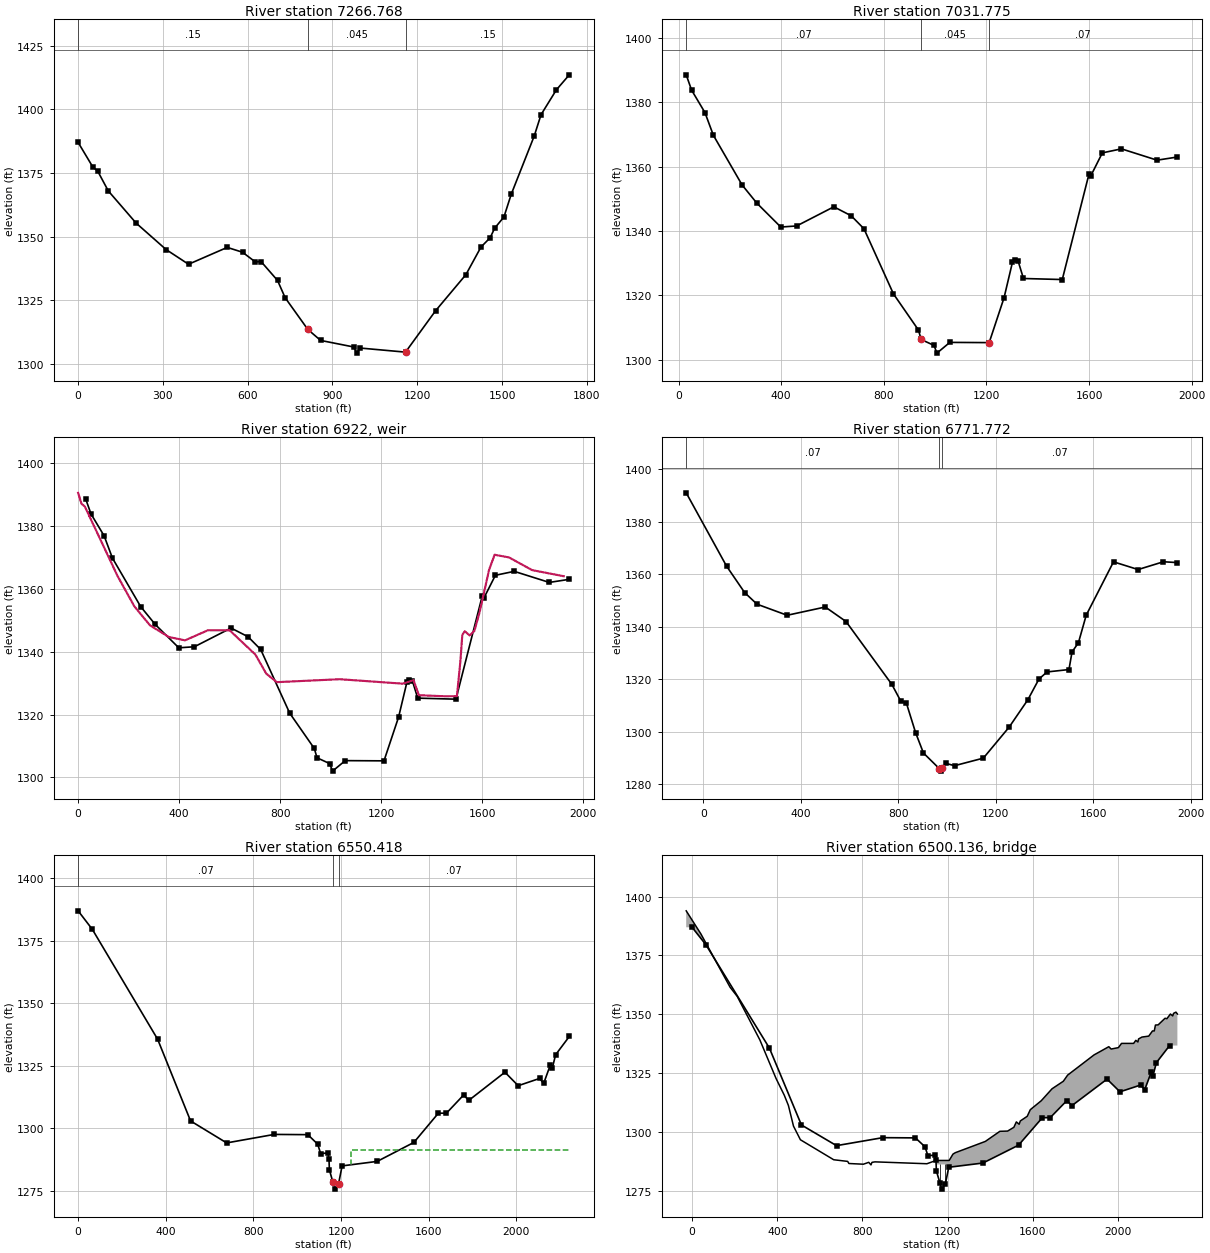
Type RM Length L Ch R = 1 ,7266.768,152.49,234.99,336
XS GIS Cut Line= 5
  1147518.294477   674376.354213  1147492.841652   673849.331724
  1147097.669275   673616.434051  1146939.639294   673487.675366
  1146414.451341    673331.73416
#Sta/Elev= 30
       0 1387.01   51.79  1377.4   69.57 1375.68  106.77 1367.96  205.14 1355.33
  311.18 1344.94  390.73 1339.15  527.64 1345.77  581.87 1343.87  626.72 1340.09
  647.24 1340.23  705.69 1332.79  732.61    1326  812.86 1313.55  858.08 1309.24
  974.83 1306.67  986.33 1304.25  997.83 1306.25  1158.5 1304.64 1264.72 1320.87
  1372.2 1335.07 1425.47  1345.9  1457.9 1349.56 1474.25 1353.36 1506.76 1357.72
 1532.54 1366.63 1614.03 1389.54 1637.99 1397.88 1692.41 1407.66 1738.03 1413.54
#Mann= 3 , 0 , 0
       0     .15       0  812.86    .045       0  1158.5     .15       0
Bank Sta=812.86,1158.5
Exp/Cntr=0.5,0.3

Type RM Length L Ch R = 1 ,7031.775,277.62,260,267.99
XS GIS Cut Line= 6
  1147537.544589   674376.567937  1147508.021807   673834.280843
  1147375.334034   673673.178314   1147147.71101   673200.398301
  1146915.911545   673009.976052  1146864.809363   672682.259297
#Sta/Elev= 30
      30 1388.59   51.07 1383.82  102.99 1376.86  135.87 1369.78  247.81 1354.33
  305.42 1348.66  398.59 1341.24  460.31 1341.57  605.38 1347.53  673.03 1344.74
   722.7 1340.71   837.6 1320.45  934.89 1309.22  945.78 1306.25   995.7 1304.41
 1007.17 1302.01 1057.39 1305.35 1210.76 1305.28 1268.68 1319.23 1301.31 1330.23
 1310.47 1331.04 1323.25 1330.72 1344.32 1325.23 1495.61  1324.9 1599.83 1357.76
 1606.51 1357.11 1651.75 1364.31 1726.26 1365.56 1865.05 1362.04 1944.28 1363.02
#Mann= 3 , 0 , 0
      30     .07       0  945.78    .045       0 1210.76     .07       0
Bank Sta=945.78,1210.76
Exp/Cntr=0.5,0.3

Type RM Length L Ch R = 5 ,6922    ,,,
BEGIN DESCRIPTION:
37111-0404 - Dam Note: The gate 4.43x4.43 is the equivalent of the 30" primary structure pipe
END DESCRIPTION:
IW Pilot Flow=0
#Inline Weir SE= 30
       0 1390.54    13.4 1387.09   26.74 1386.16  156.02  1364.1  222.51 1354.44
   284.6 1348.38  359.52 1344.67  423.31 1343.61  514.07 1346.83     600  1346.8
  701.76 1339.08  744.63 1333.04  786.39 1330.31 1034.87 1331.25 1285.69 1329.83
 1327.78 1330.96 1348.85 1326.16 1452.52 1325.82 1499.48 1325.86 1513.14 1336.91
 1520.79 1345.34 1530.76  1346.5 1549.63 1345.18 1568.45 1346.58 1589.25 1352.57
 1627.04 1366.13 1648.73 1370.84 1705.67 1369.99 1797.31 1365.95 1922.42 1364.01
IW Dist,WD,Coef,Skew,MaxSub,Min_El,Is_Ogee,SpillHt,DesHd
100,20,3,0,0.95,, 0 ,,,0,0,
IW Gate Name Wd,H,Inv,GCoef,Exp_T,Exp_O,Exp_H,Type,WCoef,Is_Ogee,SpillHt,DesHd,#Openings
Gate #1     ,4.43,4.43,1302.5,0.7,0,1,0.5, 0 ,3, 0 ,,, 1 ,0,0.8, 0
  1007.5

Type RM Length L Ch R = 1 ,6771.772,221.88,221.35,281.39
XS GIS Cut Line= 6
  1147565.191831   674377.070196   1147592.48599   673524.851441
  1147357.084752   673035.915854  1147172.026934   672883.891653
   1147062.06608    672894.16379  1146975.155951    672645.15159
#Sta/Elev= 30
     -70 1391.01   95.47  1363.1  169.84    1353  220.62 1348.58  344.29 1344.36
  500.72 1347.51  585.76 1341.98  774.08 1317.99     810 1311.73  833.51  1310.9
  871.41  1299.6  903.57 1291.87  968.53 1285.94  974.42 1284.98  980.32 1286.01
  994.92 1287.95 1031.02 1287.05 1149.27 1289.93 1254.77  1301.7 1331.87 1312.16
 1377.57 1320.08 1410.82 1322.77  1500.6 1323.68 1513.21 1330.39 1539.38 1333.88
 1571.36 1344.38  1683.4 1364.72  1784.3 1361.78 1888.39 1364.75 1945.54 1364.43
#Mann= 3 , 0 , 0
     -70     .07       0  968.53    .045       0  980.32     .07       0
Bank Sta=968.53,980.32
Exp/Cntr=0.5,0.3

Type RM Length L Ch R = 1 ,6550.418,179.73,111.07,103.01
XS GIS Cut Line= 6
  1147566.383507   674350.213925  1147853.811169   673894.932916
   1147829.34025   673514.719062  1147714.206566   673258.523265
   1147403.82982   672873.513298  1147076.313551   672438.284877
#Sta/Elev= 30
       0    1387    64.8  1379.6     363  1335.6   513.3  1302.9   678.1  1294.1
   895.4  1297.5  1048.5  1297.4  1093.6  1293.6  1107.2  1289.8  1139.8  1290.1
    1145  1287.8    1147  1283.3    1163  1278.4    1172  1275.6    1189  1277.8
    1205  1284.9  1365.3  1286.7  1532.7  1294.3  1644.4    1306  1681.2    1306
  1759.9  1313.3  1782.9  1311.1  1948.2  1322.4  2008.8    1317  2106.3  1319.9
    2125  1317.9  2155.4  1325.3  2163.9  1323.9  2179.7  1329.4    2242  1336.7
#Mann= 3 , 0 , 0
       0     .07       0    1163    .045       0    1189     .07       0
#XS Ineff= 2 , 0
       0 1104.72  1286.6 1247.28       0 1291.27
Permanent Ineff=
       F       F
Bank Sta=1163,1189
Exp/Cntr=0.5,0.3

Type RM Length L Ch R = 3 ,6500.136,,,
BEGIN DESCRIPTION:
Bridge : 37111-0379 - SR 1775
END DESCRIPTION:
Bridge Culvert--1,0,-1,-1, 0
Deck Dist Width WeirC Skew NumUp NumDn MinLoCord MaxHiCord MaxSubmerge Is_Ogee
40.28,20,2.6,0, 60, 60, , , 0.95, 0, 0,0,,
   -27.6    41.2   178.4   211.9   318.1   394.1   433.1   452.2   476.1   508.6
   664.9   730.5   736.2   804.1   829.4   839.9   844.6   858.9  1102.6    1145
    1145    1207    1207  1224.8  1235.6  1376.7    1445  1481.2  1510.6  1522.3
  1535.4  1540.9  1573.5  1587.8  1639.1    1690  1742.9    1763    1887  1956.4
  1967.3  2001.3  2016.1  2072.8  2083.2    2093  2096.1  2112.1  2143.8  2161.5
  2169.8  2175.3  2188.2  2220.5  2228.9  2245.7  2256.3  2260.5  2271.6  2278.4
    1394  1384.2  1361.5  1357.6  1339.1  1322.7  1315.5  1311.2  1302.4  1296.6
  1288.1  1287.4  1286.5  1286.2    1287  1285.9    1287  1287.2  1286.4  1287.8
  1287.8  1287.8  1287.8  1290.5  1291.1  1295.9  1300.2  1300.3  1301.9  1304.2
  1303.2  1304.6  1306.6  1309.4  1313.2  1318.3  1321.5  1324.1  1332.7  1336.2
  1335.2  1335.8  1337.6  1337.6  1338.9  1338.2  1339.5  1340.3  1340.7  1342.9
  1342.9  1345.4  1345.5  1348.3  1348.1  1350.1  1349.3  1350.4  1350.9  1350.1
                                                                                
                                                                                
  1286.1  1286.1
                                                                                
                                                                                
                                                                                
    40.6   109.4   246.6   280.1   386.3   462.3   501.3   520.4   544.3   576.8
   733.1   798.7   804.4   872.3   897.6   908.1   912.8   927.1  1170.8    1213
    1213    1275    1275    1293  1303.8  1444.9  1513.2  1549.4  1578.8  1590.5
  1603.6  1609.1  1641.7    1656  1707.3  1758.2  1811.1  1831.2  1955.2  2024.6
  2035.5  2069.5  2084.3    2141  2151.4  2161.2  2164.3  2180.3    2212  2229.7
    2238  2243.5  2256.4  2288.7  2297.1  2313.9  2324.5  2328.7  2339.8  2346.6
    1394  1384.2  1361.5  1357.6  1339.1  1322.7  1315.5  1311.2  1302.4  1296.6
  1288.1  1287.4  1286.5  1286.2    1287  1285.9    1287  1287.2  1286.4  1287.6
  1287.6  1287.6  1287.6  1290.5  1291.1  1295.9  1300.2  1300.3  1301.9  1304.2
  1303.2  1304.6  1306.6  1309.4  1313.2  1318.3  1321.5  1324.1  1332.7  1336.2
  1335.2  1335.8  1337.6  1337.6  1338.9  1338.2  1339.5  1340.3  1340.7  1342.9
  1342.9  1345.4  1345.5  1348.3  1348.1  1350.1  1349.3  1350.4  1350.9  1350.1
                                                                                
                                                                                
  1285.9  1285.9
                                                                                
                                                                                
                                                                                
Pier Skew, UpSta & Num, DnSta & Num=  ,1163, 2 ,1231, 2 , 0 , 0 , 0 ,,
       1       1
  1275.6  1286.6
       1       1
  1275.4  1286.4
Pier Skew, UpSta & Num, DnSta & Num=  ,1189, 2 ,1257, 2 , 0 , 0 , 0 ,,
       1       1
  1276.8  1286.6
       1       1
  1276.6  1286.4
BR Coef=-1 , 1 , 1 ,1.25, 0 ,,,0.8,0,2,0,
WSPro=,,,, 1 ,,,, 0 ,,,, 0 ,,,,-1 ,-1 ,-1 , 0 , 0 , 0 , 0 , 0
BC Design=,, 0 ,, 0 ,,,,,,

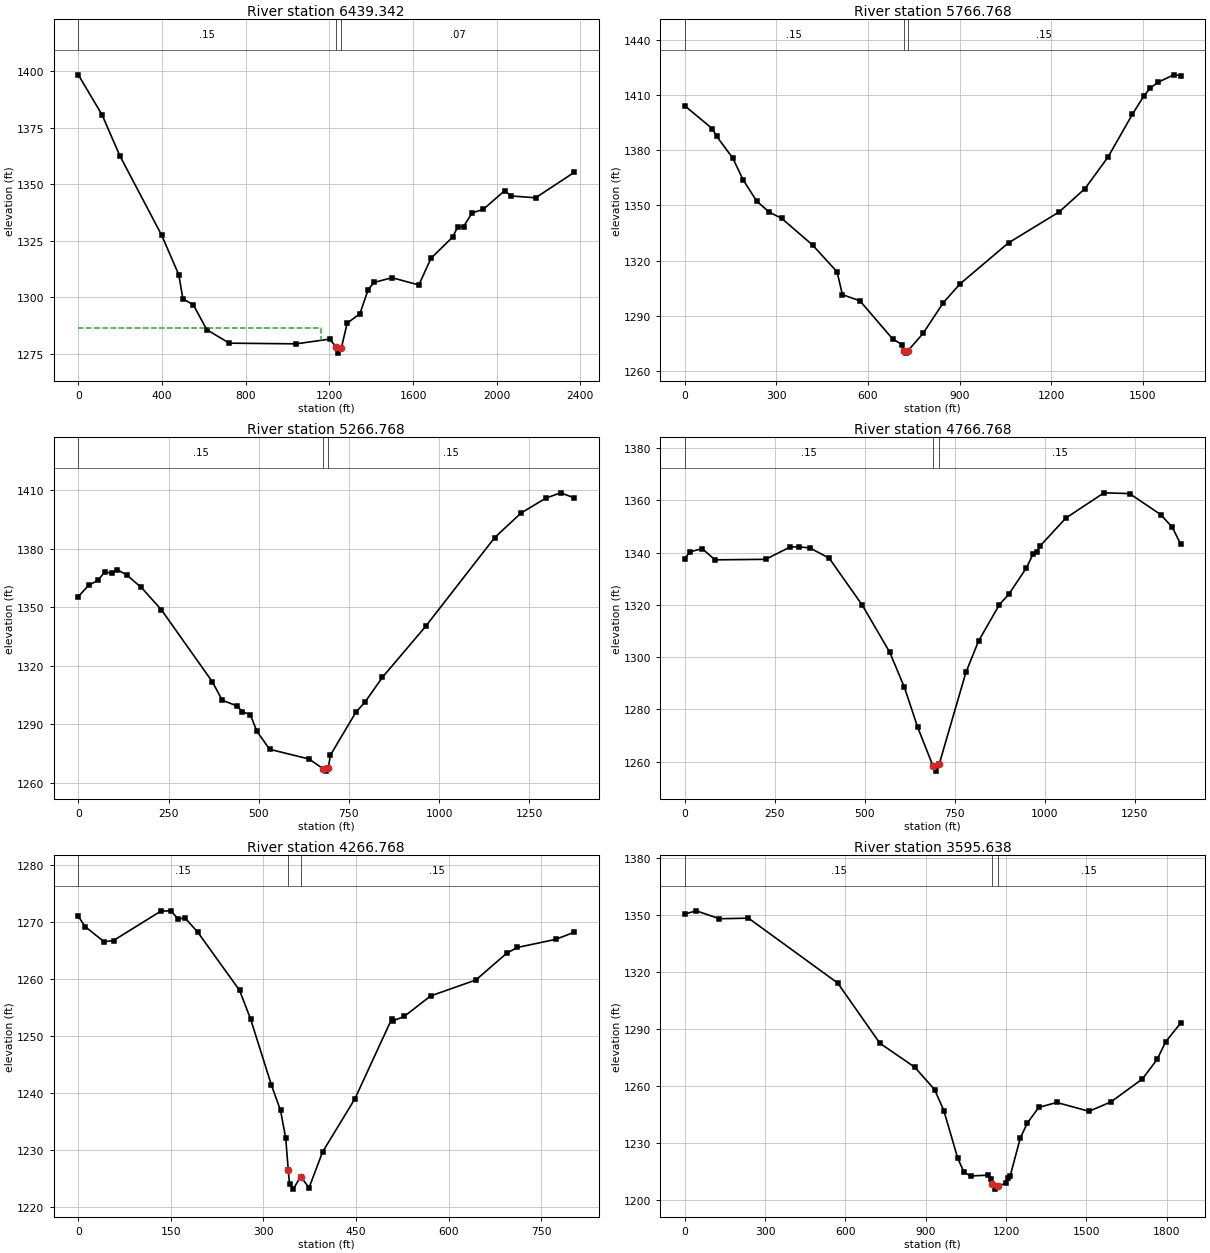
Type RM Length L Ch R = 1 ,6439.342,571.01,672.57,714.77
XS GIS Cut Line= 6
  1147650.942269   674403.597551  1147958.718739    673916.08429
  1147941.554027   673813.144973  1147926.950631   673490.530058
  1147806.364868   673214.846036  1147154.188175   672375.550958
#Sta/Elev= 30
       0  1398.3   113.6  1380.6   198.2  1362.6   398.7  1327.4   480.2    1310
     500  1299.3   549.3  1296.8   614.2  1285.7   722.4  1279.8  1041.5  1279.5
  1201.7  1281.6    1231  1278.2    1240  1275.4    1257  1277.6    1285  1288.6
  1345.9  1292.8  1385.3  1303.4  1412.8  1306.6  1499.4  1308.7  1627.6  1305.5
  1685.9  1317.3  1788.6  1326.6  1813.6  1331.1  1841.5  1331.3  1882.1  1337.3
  1935.9  1338.9  2037.4  1347.1  2069.8  1344.8  2185.7    1344  2370.1  1355.2
#Mann= 3 , 0 , 0
       0     .15       0    1231     .05       0    1257     .07       0
#XS Ineff= 2 , 0
       0  1162.2  1286.6  1325.8       0 1291.27
Permanent Ineff=
       F       F
Bank Sta=1231,1257
Exp/Cntr=0.5,0.3

Type RM Length L Ch R = 1 ,5766.768,498.84,500,495.03
XS GIS Cut Line= 3
  1147664.489127   674454.878629  1148063.692679   673851.835377
  1148765.004943   673286.926027
#Sta/Elev= 30
       0 1403.99   90.09 1391.62  103.99 1387.53  157.44 1375.52  190.57 1363.95
  235.06 1352.34   275.9 1346.32   317.3 1342.89  418.92 1328.33  498.66 1313.84
  516.16 1301.45  573.56 1298.11  681.13  1277.3  712.67 1274.27  717.43 1270.73
   723.2  1269.7  729.35 1270.74  780.15 1280.37  846.93 1297.17  901.49 1307.31
 1060.08 1329.59  1225.5 1346.33 1310.72 1359.07    1386 1376.19 1465.65 1399.35
 1502.74 1409.22 1524.25 1413.64 1549.33 1416.77 1601.36 1420.84 1623.74 1420.41
#Mann= 3 , 0 , 0
       0     .15       0  717.43     .05       0  729.35     .15       0
Bank Sta=717.43,729.35
Exp/Cntr=0.3,0.1

Type RM Length L Ch R = 1 ,5266.768,501.89,500,492.56
XS GIS Cut Line= 3
  1147986.364471   674780.790833  1148379.376637   674218.383093
  1148833.477477    673700.98255
#Sta/Elev= 30
       0 1355.51   28.54 1361.31   54.25 1363.79   73.57 1368.24   93.74 1367.38
  108.27 1369.26  133.57 1366.68  174.64 1360.19  229.89 1348.82  371.38 1311.84
  399.05 1302.33  440.75  1299.4  454.65 1296.46  476.71 1294.95  494.86 1286.49
  530.17  1277.2  639.68 1272.21  678.82 1267.19  686.12    1266  693.07 1267.75
  698.68 1274.16  769.79 1296.32  794.47 1301.35  843.18 1314.15  962.78 1340.23
 1154.07 1385.73 1226.91 1398.29 1296.05 1405.99 1337.03 1408.71 1374.53 1406.13
#Mann= 3 , 0 , 0
       0     .15       0  678.82     .05       0  693.07     .15       0
Bank Sta=678.82,693.07
Exp/Cntr=0.3,0.1

Type RM Length L Ch R = 1 ,4766.768,495,500,505
XS GIS Cut Line= 3
  1148407.239691    675107.93976  1148769.475384   674511.985837
  1149089.821117   673912.660925
#Sta/Elev= 30
       0 1337.67   14.57 1340.31    48.7 1341.49   83.83 1337.23  224.34 1337.43
  292.94 1342.16  316.47 1342.22  347.52 1341.76  400.81  1337.9  493.15 1319.84
  568.99 1301.93  610.02 1288.43  646.59 1273.26   689.2  1258.4  697.41 1256.43
  706.57 1259.12  780.58 1294.15  815.77 1306.18   873.9 1320.15  901.02 1324.29
  948.49 1334.13  967.34 1339.48  977.88 1340.13  986.71 1342.54 1058.14  1353.2
 1164.01 1362.86 1235.24 1362.57 1321.54 1354.54 1353.62 1349.74 1376.97 1343.29
#Mann= 3 , 0 , 0
       0     .15       0   689.2     .05       0  706.57     .15       0
Bank Sta=689.2,706.57
Exp/Cntr=0.3,0.1

Type RM Length L Ch R = 1 ,4266.768,672.53,671.13,665.19
XS GIS Cut Line= 5
  1148936.601464   675089.800917  1149076.084034   674915.192488
  1149157.639639   674820.630443  1149228.795387   674714.175627
  1149434.627774   674459.944174
#Sta/Elev= 30
       0 1270.96   10.91 1269.16   41.91 1266.48      57 1266.71  133.81 1271.87
  150.01 1271.92  161.03 1270.57  173.63 1270.58  193.52 1268.17  261.32 1257.96
  279.17 1252.92  312.94 1241.33  327.69 1236.88  336.07 1232.03  340.23 1226.39
  342.21 1224.06  348.35 1223.08  360.17 1225.28  373.93 1223.33  395.73 1229.59
  448.24 1238.94  507.75 1252.92  509.86 1252.62  528.06 1253.38   570.8 1256.98
  644.16 1259.78  694.58 1264.51  711.51 1265.49  773.48 1266.91  803.51 1268.15
#Mann= 3 , 0 , 0
       0     .15       0  340.23     .05       0  360.17     .15       0
Bank Sta=340.23,360.17
Exp/Cntr=0.3,0.1

Type RM Length L Ch R = 1 ,3595.638,216.14,199.68,186.43
XS GIS Cut Line= 5
  1148832.713293   675672.342675  1149598.338308   675177.551016
  1149744.171613   674984.842703   1149827.50498   674797.342671
  1149947.296619   674318.176029
#Sta/Elev= 30
       0  1350.4   42.65 1352.08  129.49 1347.92   237.8 1348.23  571.19 1314.15
  728.94 1282.47  858.58 1269.97  933.29 1258.15  967.71 1247.13 1019.81    1222
 1043.55 1214.59 1069.09 1212.77 1133.22 1213.17 1145.04 1211.26 1149.14  1208.4
 1158.19 1205.84  1169.9 1207.59 1199.47 1208.85 1205.91 1211.79  1215.2 1212.53
 1253.46 1232.73 1279.76 1240.59 1322.33 1248.79 1389.58 1251.38 1510.05 1246.74
 1591.41 1251.62 1709.56 1263.74 1764.63    1274  1796.5 1283.25 1852.36 1293.09
#Mann= 3 , 0 , 0
       0     .15       0 1149.14     .05       0  1169.9     .15       0
Bank Sta=1149.14,1169.9
Exp/Cntr=0.3,0.1

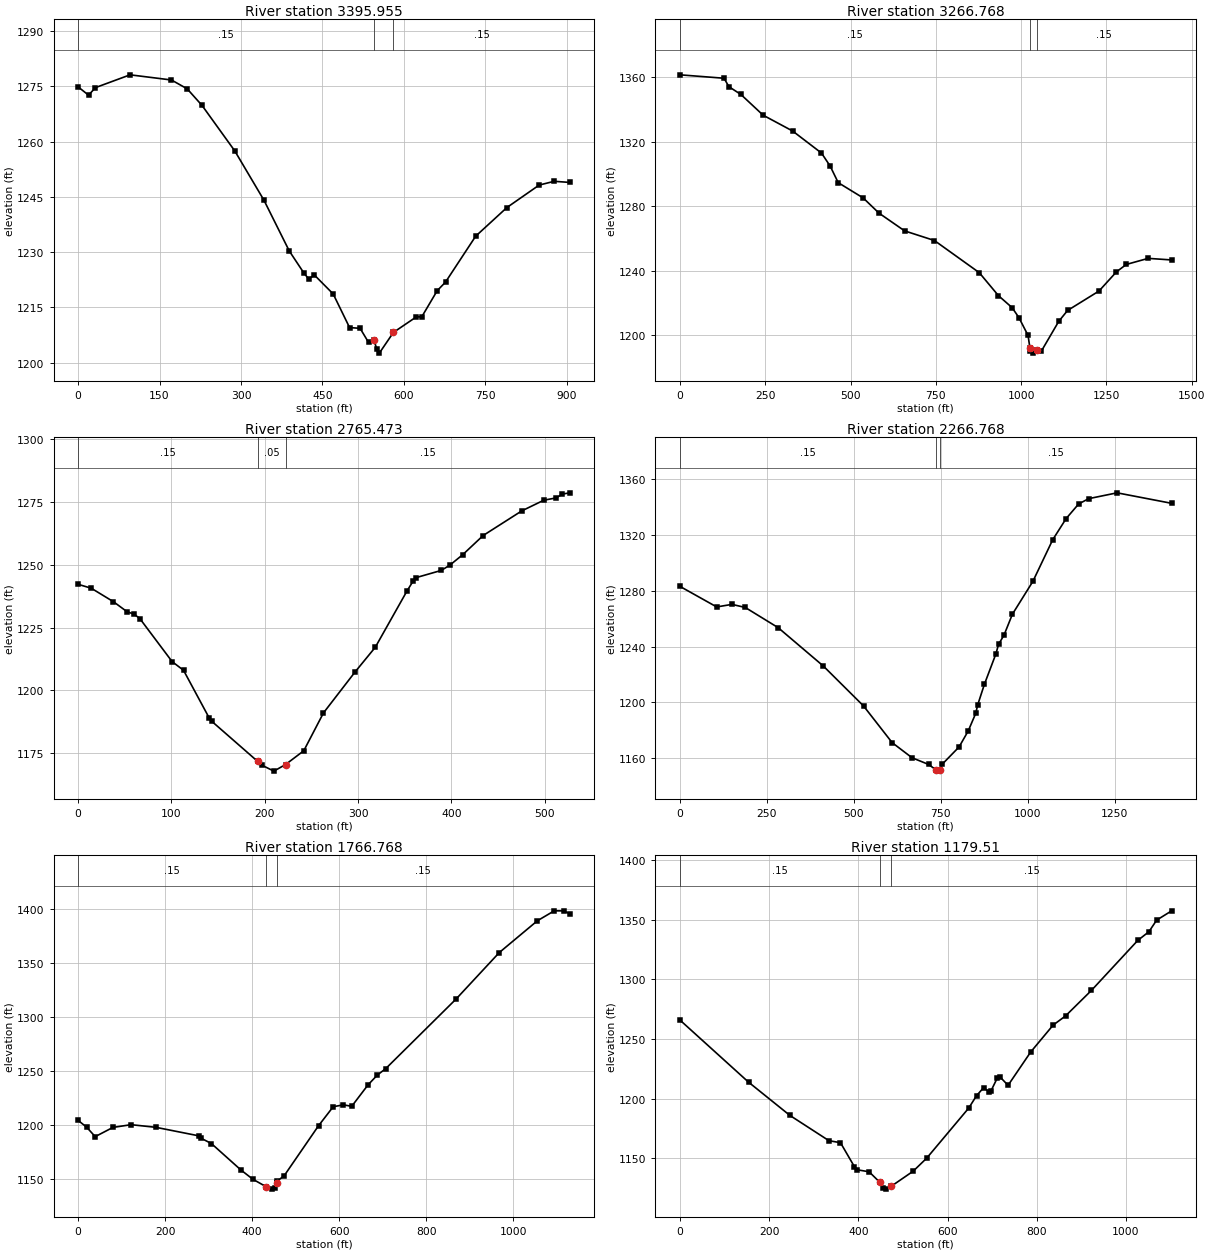
Type RM Length L Ch R = 1 ,3395.955,133.87,129.19,120.1
XS GIS Cut Line= 3
  1149853.555754    675672.78465  1149874.062712   675042.927863
  1149871.133165   674767.548635
#Sta/Elev= 30
       0 1274.84   19.23 1272.59   31.89 1274.64   95.74 1278.11   171.9 1276.71
  200.89 1274.31  228.19 1269.81  288.51 1257.47  342.37 1244.06   388.9 1230.31
  415.83 1224.32   424.6 1222.72  435.27 1223.76  469.83 1218.63  499.98 1209.52
  519.36 1209.31  535.01 1205.48  545.31 1206.04  550.11 1203.58  554.79 1202.58
  580.74  1208.2  623.18 1212.44  632.89 1212.41   661.4 1219.53  676.68 1221.85
  732.29 1234.32  789.74 1242.09  849.18 1248.19  876.94 1249.21  905.59 1248.91
#Mann= 3 , 0 , 0
       0     .15       0  545.31     .05       0  580.74     .15       0
Bank Sta=545.31,580.74
Exp/Cntr=0.3,0.1

Type RM Length L Ch R = 1 ,3266.768,526.88,501.3,483.39
XS GIS Cut Line= 3
   1150116.41854   676088.699833  1149987.156442   675063.259346
  1149883.025138   674668.977761
#Sta/Elev= 30
       0 1361.66  129.07 1359.54   143.4 1354.29  178.37 1349.48  243.68 1336.58
  330.16 1326.75   414.8 1313.05  440.29 1304.92  463.85 1294.65  536.89 1285.18
  583.61 1275.68  658.57 1264.68  745.78 1258.71  877.28 1238.74  933.55 1224.45
  973.64 1216.99  993.52 1210.82 1020.42 1199.69  1025.8  1191.9 1026.98    1190
 1033.56 1188.73 1046.28 1190.77  1059.6 1190.06 1110.32 1208.47 1136.18 1215.23
 1228.31 1227.31 1279.41 1239.21 1308.34 1243.83 1372.44 1247.61 1441.36 1246.63
#Mann= 3 , 0 , 0
       0     .15       0  1025.8     .05       0 1046.28     .15       0
Bank Sta=1025.8,1046.28
Exp/Cntr=0.3,0.1

Type RM Length L Ch R = 1 ,2765.473,490.5,498.7,500.61
XS GIS Cut Line= 4
  1150521.293581    675041.87248  1150369.907844   674915.534997
  1150347.106337   674905.875913  1150171.229645   674656.735549
#Sta/Elev= 30
       0 1242.22   14.05 1240.67   37.91 1235.28   52.16 1231.39   60.36 1230.24
   66.16 1228.57  100.71 1211.46  112.98 1207.98  140.47 1189.01  143.26 1187.67
  192.48 1171.69  197.18 1170.16  209.78 1167.84  222.33 1170.47  241.83 1175.95
  262.93 1191.02  296.76 1207.31  318.47 1217.16  352.66 1239.71  359.18  1243.6
  362.23 1244.89  389.23 1247.76  398.49 1249.89   412.1 1253.99  434.06 1261.65
  475.46 1271.46  499.14 1275.72  512.27 1276.62  518.93 1278.15   526.9 1278.65
#Mann= 3 , 0 , 0
       0     .15       0  192.48     .05       0  222.33     .15       0
Bank Sta=192.48,222.33
Exp/Cntr=0.3,0.1

Type RM Length L Ch R = 1 ,2266.768,495,500,505
XS GIS Cut Line= 3
  1151074.162093   675033.662554  1150585.284169   674475.846309
  1150126.051947   673985.508209
#Sta/Elev= 30
       0 1283.03  105.42 1268.33  149.45 1270.16  187.59 1267.95  282.36 1253.46
  412.23 1225.98  527.92 1197.36  609.89 1171.17  667.23 1160.32  714.59 1155.56
   735.5 1151.75  741.73 1150.76  748.02 1151.77   753.9 1155.71  802.36 1168.08
  828.62 1179.53  850.47 1192.28  855.44 1197.83  875.04 1212.86  908.06 1234.61
  915.85 1241.54   931.6 1248.17  955.65 1263.12 1014.51 1286.62 1071.64 1316.49
 1110.24 1331.63 1146.16 1342.08 1175.06 1345.87 1256.63 1350.04 1413.54 1342.52
#Mann= 3 , 0 , 0
       0     .15       0   735.5     .05       0  748.02     .15       0
Bank Sta=735.5,748.02
Exp/Cntr=0.3,0.1

Type RM Length L Ch R = 1 ,1766.768,598.93,587.26,572.51
XS GIS Cut Line= 4
  1151300.761542   674533.183323  1151048.700694   674281.357568
  1150986.250823   674218.281362  1150484.760234   673751.429788
#Sta/Elev= 30
       0 1204.35    19.4 1198.14   39.25 1189.35   80.04 1197.87   121.8 1200.39
  178.64 1197.96  278.82 1189.97  283.39 1187.71  306.33 1182.96   374.3 1158.49
  401.61 1149.97  432.21 1143.04  445.06 1140.81  451.65 1141.81  456.57 1146.64
  458.08 1148.31   473.8 1153.26  552.72 1199.45  586.39    1217  609.78 1218.73
  628.98 1217.38  666.47 1237.21   687.8 1246.27  707.08  1252.2   869.2 1316.71
  968.25 1359.56  1055.8 1388.94 1094.52 1398.11 1116.38 1398.06 1130.22 1395.38
#Mann= 3 , 0 , 0
       0     .15       0  432.21     .05       0  456.57     .15       0
Bank Sta=432.21,456.57
Exp/Cntr=0.3,0.1

Type RM Length L Ch R = 1 ,1179.51 ,320.34,327.81,338.56
XS GIS Cut Line= 3
  1151748.985208   674087.889248  1151375.988624   673852.006809
  1150744.143948    673657.24295
#Sta/Elev= 30
       0 1265.77  153.73  1213.8  246.49 1185.93  334.01 1164.78  359.85 1163.11
  391.06 1143.03  397.63 1140.38     424 1138.76  448.18 1129.92  454.47 1125.34
  460.88 1124.21  473.58 1126.59  522.79 1139.21  553.17 1150.14  647.48 1192.11
  665.04 1202.52  680.75 1209.17  693.92 1205.56  697.46 1206.55  711.53 1217.31
  717.64 1218.18  735.65 1211.15  786.47 1239.08  836.67 1261.57  864.58 1269.29
  922.65 1290.66 1026.59 1332.54 1051.48 1339.79 1068.87 1349.51 1102.51  1357.3
#Mann= 3 , 0 , 0
       0     .15       0  448.18     .05       0  473.58     .15       0
Bank Sta=448.18,473.58
Exp/Cntr=0.3,0.1