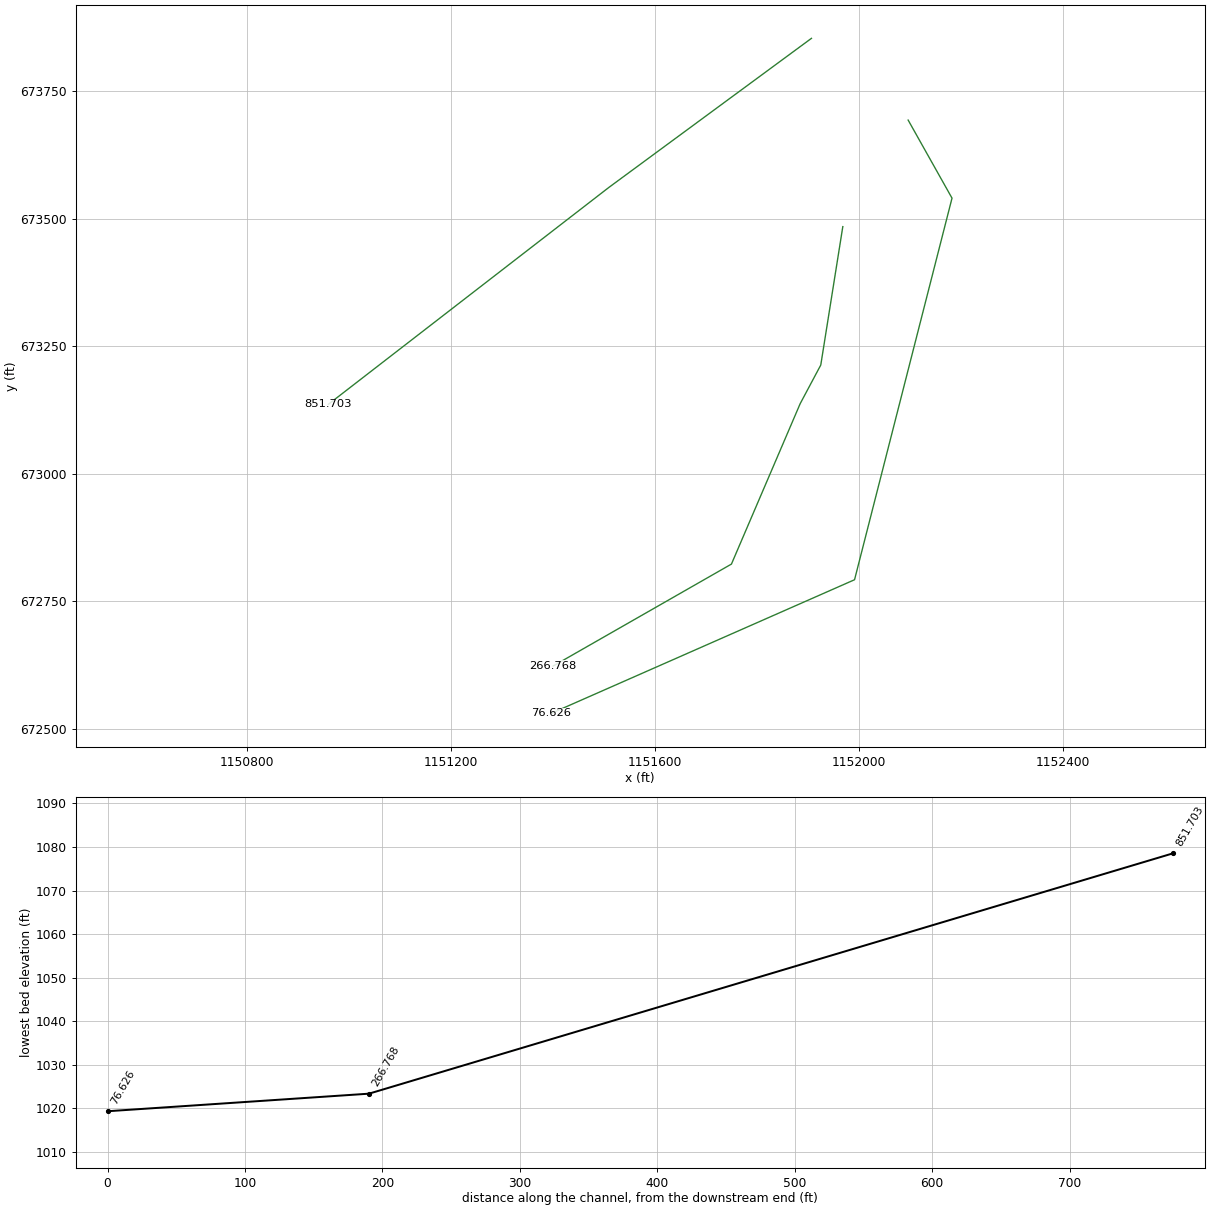
HEC-RAS study ShoalCr.prj: ShoalCr

--- ShoalCr.g01 (geometry) --- (continued)

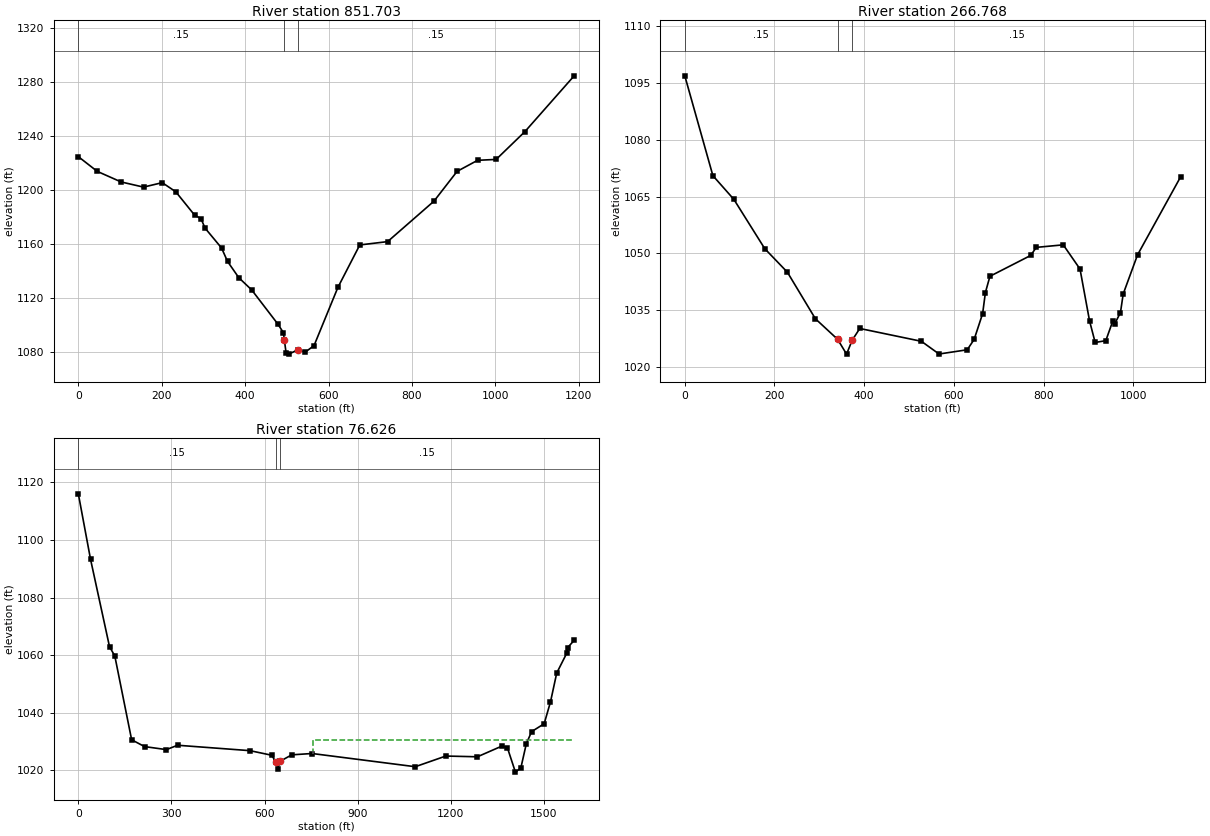
Type RM Length L Ch R = 1 ,851.703 ,571.66,584.93,600.16
XS GIS Cut Line= 3
   1151907.18178   673853.523936  1151509.283896   673560.933484
  1150959.391132   673136.098789
#Sta/Elev= 30
       0 1224.67   45.25  1213.8   102.5 1205.96  156.32 1202.13  201.13 1205.43
  233.62 1198.68  278.69 1181.42  294.05 1178.81  303.81 1171.79  343.38 1157.08
  357.77 1147.11  384.87 1135.05  415.74 1126.03  478.33 1100.81  491.65 1094.44
  493.89 1089.19  498.03 1079.63  504.41 1078.54  526.65 1081.76  544.51 1080.12
  565.15 1084.86  622.31  1127.9   674.8 1159.34  741.49 1161.79  852.69 1191.74
  908.12 1213.78  957.25 1221.96 1001.78 1222.63 1070.79 1243.22 1188.78 1284.48
#Mann= 3 , 0 , 0
       0     .15       0  493.89     .05       0  526.65     .15       0
Bank Sta=493.89,526.65
Exp/Cntr=0.3,0.1

Type RM Length L Ch R = 1 ,266.768 ,187,190.14,193
XS GIS Cut Line= 5
  1151968.702654   673484.398557  1151925.468733   673213.137175
  1151884.990527   673137.256214  1151750.197852   672822.922348
  1151400.366786   672623.106048
#Sta/Elev= 30
       0 1096.95   62.62 1070.56  109.47 1064.28  178.29 1051.26   228.7 1045.04
  291.18 1032.73  340.82 1027.28  360.69 1023.38  373.37 1027.09  390.17 1030.16
  527.57 1026.77  566.93 1023.41  629.71 1024.53  645.17 1027.27  664.11  1034.1
  670.23 1039.64  680.36 1043.96  771.14 1049.46  783.83  1051.6  843.87 1052.27
  881.25 1045.87  902.52 1032.16  915.01 1026.46  938.76 1026.94  954.04 1032.03
  958.67  1031.4  971.45 1034.38  977.52 1039.28 1009.48 1049.61 1105.58 1070.25
#Mann= 3 , 0 , 0
       0     .15       0  340.82     .05       0  373.37     .15       0
Bank Sta=340.82,373.37
Exp/Cntr=0.3,0.1

Type RM Length L Ch R = 1 ,76.626  ,104.56,76.63,108.69
XS GIS Cut Line= 4
  1152096.868988   673693.283012  1152182.953628   673540.243632
  1151991.725215   672792.236899  1151396.580876   672530.271657
#Sta/Elev= 30
       0 1116.05   39.34  1093.3  100.46 1062.94  117.54 1059.71  171.75  1030.6
  213.49 1028.22  283.91 1027.17  319.77 1028.69  553.08 1026.81  623.55 1025.21
  635.52 1022.99  642.62  1020.4  649.15 1023.06  687.91 1025.36  753.26 1025.82
 1085.77 1021.23 1184.31 1024.94 1286.12 1024.68 1365.43 1028.42  1382.9 1027.78
 1408.59 1019.35 1426.09  1020.8 1443.79 1029.25 1460.88 1033.43 1501.22 1036.16
 1521.64 1043.76 1541.67 1053.77 1574.09 1060.69 1577.14 1062.64  1597.9 1065.15
#Mann= 3 , 0 , 0
       0     .15       0  635.52     .05       0  649.15     .15       0
#XS Ineff= 2 , 0
                          755.36         1030.48
Permanent Ineff=
       F       F
Bank Sta=635.52,649.15
Exp/Cntr=0.3,0.1

Chan Stop Cuts=-1
Use User Specified Reach Order=0
User Specified Reach Order=ShoalCr         ,Main