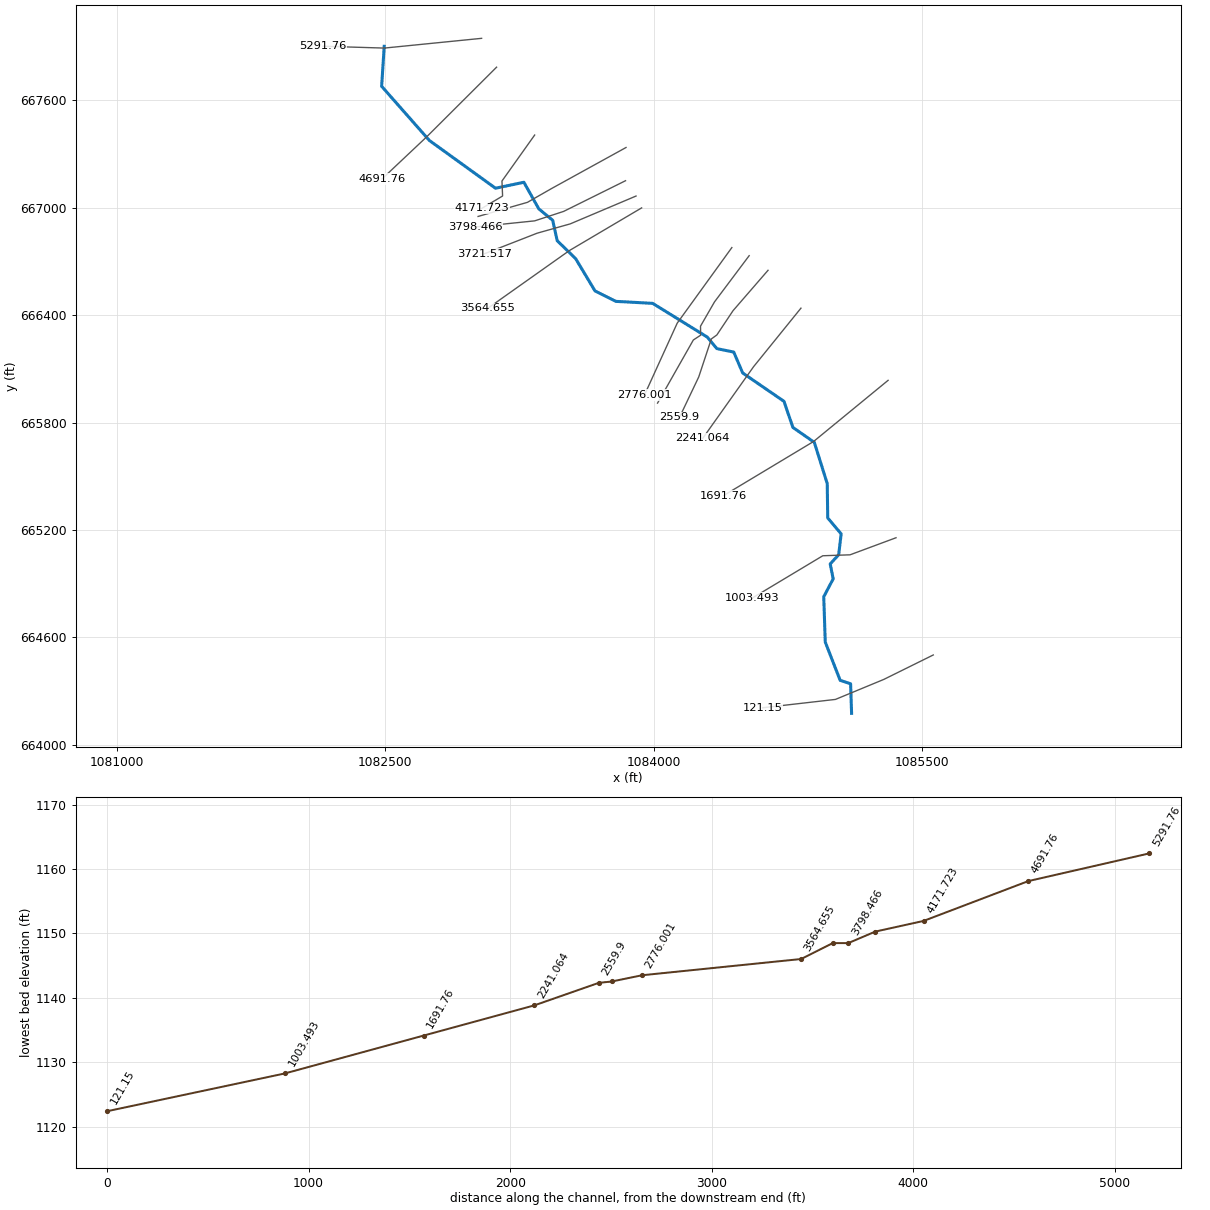
--- HarrisCr.prj (project) ---

Proj Title=HarrisCr
Current Plan=p01
Default Exp/Contr=0.3,0.1
English Units
Geom File=g01
Flow File=f01
Plan File=p01
Y Axis Title=Elevation
X Axis Title(PF)=Main Channel Distance
X Axis Title(XS)=Station
BEGIN DESCRIPTION:
END DESCRIPTION:
DSS Export Rating Curves= 0
DSS Export Rating Curve Sorted= 0
DSS Export Volume Flow Curves= 0
DXF OffsetX= 0
DXF OffsetY= 0
DXF ScaleX= 1
DXF ScaleY= 10

--- HarrisCr.p01 (plan) ---

Plan Title=LD Study - 100 YR
Program Version=3.12
Short Identifier=LDS-100yr
Geom File=g01
Flow File=f01
Subcritical Flow
K Sum by GR= 0
Std Step Tol= 0.01
Critical Tol= 0.01
Num of Std Step Trials= 20
Max Error Tol= 0.3
Flow Tol Ratio= 0.001
Split Flow NTrial= 30
Split Flow Tol= 0.02
Split Flow Ratio= 0.02
Log Output Level= 0
Friction Slope Method= 1
Unsteady Friction Slope Method= 2
Unsteady Bridges Friction Slope Method= 1
Calc Critical at every XS
Parabolic Critical Depth
Global Vel Dist= 0 , 0 , 0
Global Log Level= 0
CheckData=True
Encroach Param=-1 ,0,0, 2
Encroach River=HarrisCr
Encroach Reach=Main
Encroach Node=5291.76
       1     497     580
Encroach Node=4691.76
       1     357     556
Encroach Node=4171.723
       1     225     425
Encroach Node=3932.882
       1     507     607
Encroach Node=3798.466
       1     410     488
Encroach Node=3721.517
       1   443.8515.3866
Encroach Node=3564.655
       1     455     505
Encroach Node=2776.001
       1     490     590
Encroach Node=2625.236
       1     490     625
Encroach Node=2559.9
       1     490     630
Encroach Node=2241.064
       1463.5274 574.678
Encroach Node=1691.76
       1512.2023571.2732
Encroach Node=1003.493
       1283.5061440.8857
Encroach Node=121.15
       1     440     570
Computation Interval=1HOUR
Output Interval=1HOUR
Run HTab= 0
Run UNet= 0
Run PostProcess= 0
UNET Theta= 1
UNET Theta Warmup= 1
UNET ZTol= 0.02
UNET ZSATol= 0.05
UNET MxIter= 20
UNET MaxInSteps= 0
UNET DtIC= 0
UNET DtMin= 0
UNET MaxCRTS= 20
UNET WFStab= 2
UNET SFStab= 1
UNET WFX= 1
UNET SFX= 1
UNET DSS MLevel= 4
UNET DZMax Abort= 100
UNET Convert EG Bridges=-1
UNET Use Existing IB Tables=-1
UNET Froude Reduction=False
UNET Froude Limit= 1
UNET Froude Power= 10
Instantaneous Interval=1HOUR
Write IC File= 0
Echo Input=False
Echo Output=False
Write Detailed= 0
Detailed Automatic Start=False, 10

--- HarrisCr.f01 (steady flow) ---

Flow Title=HarrisCr
Program Version=3.12
Number of Profiles= 2
Profile Names=P100yr,Enchroachments
River Rch & RM=HarrisCr,Main            ,5291.76
    1260    1260
River Rch & RM=HarrisCr,Main            ,3932.882
    1470    1470
Boundary for River Rch & Prof#=HarrisCr,Main            , 1
Up Type= 0
Dn Type= 3
Dn Slope=0.007537
DSS Import GetInterval= 0
DSS Import GetPeak= 0
DSS Import FillOption= 0

--- HarrisCr.g01 (geometry) ---

Geom Title=HarrisCr
Program Version=3.12

River Reach=HarrisCr        ,Main
Reach XY= 30
  1082495.000349   667901.440175  1082480.500508   667678.059705
  1082747.250435   667375.310004  1083116.629772   667108.629702
  1083274.999583   667141.940413  1083358.379808   666993.379521
  1083436.130063   666929.439921  1083461.129989   666815.559864
  1083563.880207   666715.560122  1083672.250129   666535.000254
  1083788.879617    666476.68958  1083994.499851    666465.55974
  1084300.000028   666276.690096  1084352.750356   666212.809928
  1084447.250192   666193.379496  1084497.250081   666076.689604
  1084727.750406   665918.380232  1084777.750295   665772.500155
  1084897.250058   665689.189554  1084969.500442   665458.629834
  1084972.249873    665266.94009  1085047.249689   665178.059959
  1085033.379602   665061.380296  1084986.130189   665010.000055
  1085002.749706   664926.690499  1084950.000386   664826.689712
  1084958.379787   664573.880505  1085041.629984   664359.999661
  1085100.000017   664340.560044  1085105.499923    664175.31001

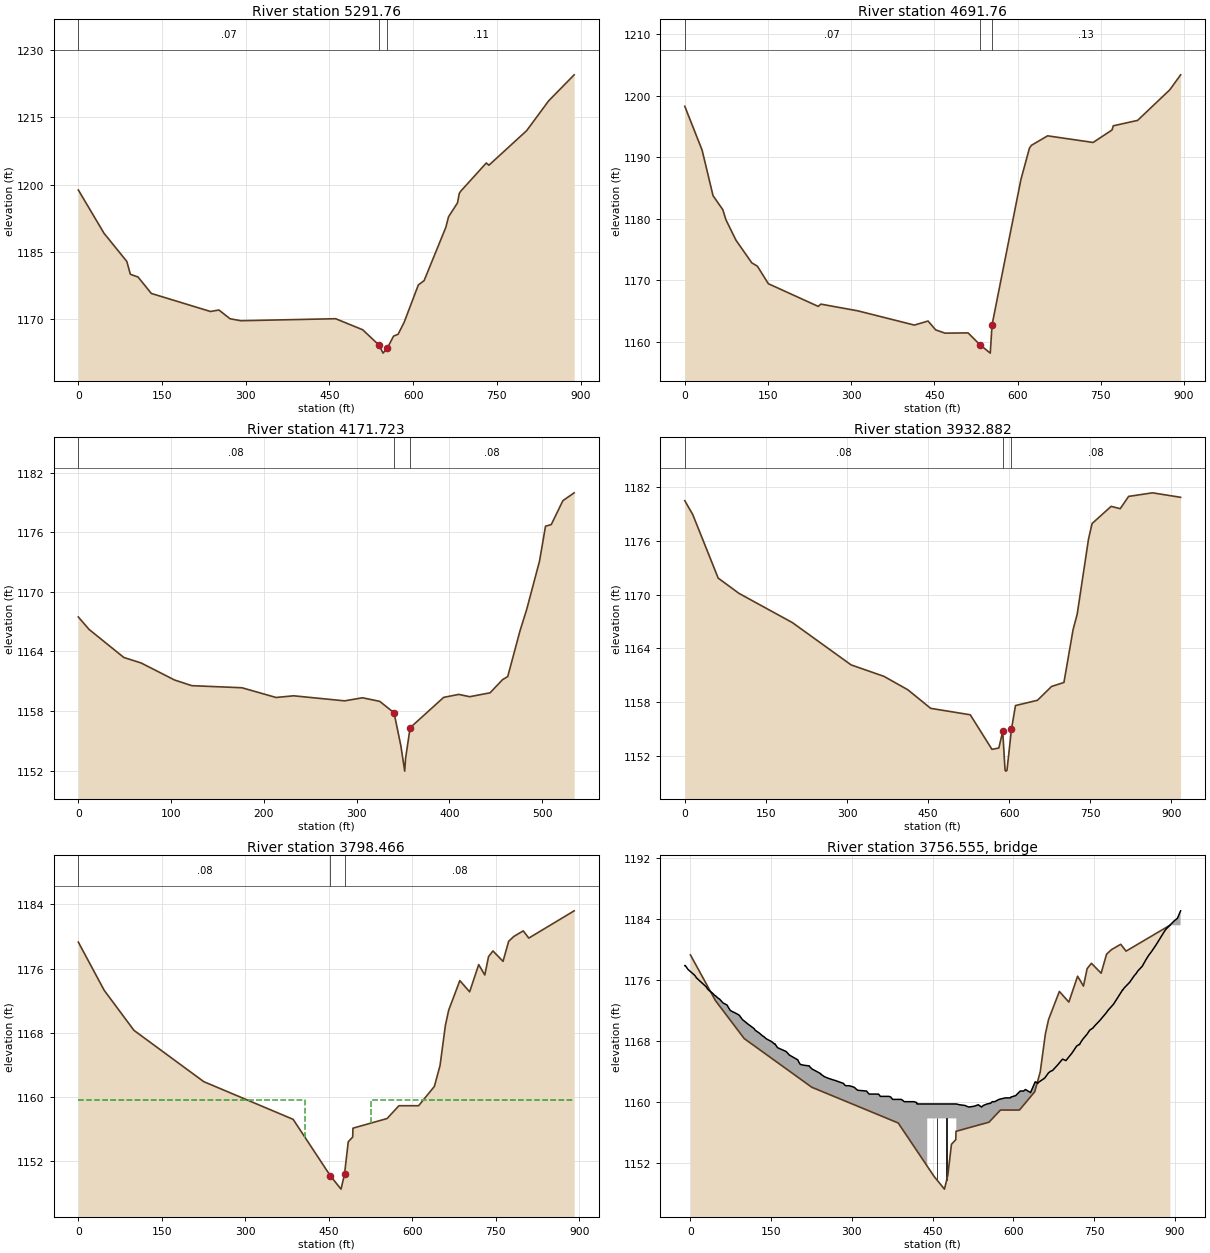
Type RM Length L Ch R = 1 ,5291.76 ,578.79,600,623.29
XS GIS Cut Line= 3
  1083038.873826   667945.900645  1082495.542433   667891.454871
  1082153.239621   667901.839768
#Sta/Elev= 30
       0 1198.79      46 1189.15   86.82 1182.88   93.29    1180  106.98 1179.39
  130.84 1175.73  236.77 1171.71   251.9 1172.04   271.9 1170.09  291.41 1169.65
  461.15  1170.1  509.54 1167.64  539.16 1164.17  546.05 1162.43  553.83 1163.57
  564.88 1166.22     573 1166.63  583.89 1169.31  609.28 1177.62  619.64 1178.59
  658.54 1190.46  663.42 1192.82  679.45 1195.91  682.67 1198.03  685.41 1198.54
  731.11 1204.81  735.69  1204.3   803.4 1212.01  842.79 1218.65  888.51 1224.45
#Mann= 3 , 0 , 0
       0     .07       0  539.16    .051       0  553.83     .11       0
Bank Sta=539.16,553.83
Exp/Cntr=0.3,0.1

Type RM Length L Ch R = 1 ,4691.76 ,527.1,520.037,527.1
XS GIS Cut Line= 3
   1083122.53806    667784.81897  1082732.429918   667396.012263
  1082482.684694   667160.588335
#Sta/Elev= 30
       0 1198.27   31.23 1191.14   50.95 1183.73   68.59 1181.45   74.18 1179.82
   92.12 1176.52  120.83 1172.81  130.91 1172.27  150.67 1169.42  240.56 1165.73
  245.37  1166.1  311.83 1165.01     414 1162.69   438.6 1163.35  452.35 1161.91
  469.17 1161.38  510.78 1161.42  531.85 1159.52  550.78 1158.13  553.97 1162.71
  605.98 1186.34  621.34 1191.45  624.86 1191.92  654.14 1193.47  736.22 1192.39
  770.42 1194.43  772.55  1195.1  816.41 1195.98  874.52 1200.96  893.99 1203.39
#Mann= 3 , 0 , 0
       0     .07       0  531.85    .051       0  553.97     .13       0
Bank Sta=531.85,553.97
Exp/Cntr=0.3,0.1

Type RM Length L Ch R = 1 ,4171.723,270.63,238.84,205.1
XS GIS Cut Line= 4
  1083335.211479   667405.692487   1083152.59097   667148.845561
  1083156.125541   667065.193573  1083039.484058   666995.679976
#Sta/Elev= 30
       0 1167.47   11.57 1166.22   49.08 1163.39   67.65 1162.84  103.81 1161.12
  122.42 1160.55  176.45 1160.34  213.27 1159.36  232.16 1159.53  287.07 1159.02
  306.44 1159.33     325 1158.97  340.44 1157.82  347.77 1154.51  351.95 1151.94
   352.9 1153.25  357.78 1156.31  393.94 1159.37  410.11 1159.67  422.07 1159.44
  443.99 1159.83  457.35 1161.15  463.04 1161.47  476.31 1166.09  483.45 1168.22
  497.28 1173.09  503.79 1176.62  509.97 1176.78  522.49 1179.19  534.66 1179.98
#Mann= 3 , 0 , 0
       0     .08       0  340.44     .05       0  357.78     .08       0
Bank Sta=340.44,357.78
Exp/Cntr=0.3,0.1

Type RM Length L Ch R = 1 ,3932.882,141.28,134.42,127.1
XS GIS Cut Line= 4
  1083845.664891   667336.182564  1083432.408986   667108.470102
  1083294.657042   667029.754721  1083019.153082   666951.039303
#Sta/Elev= 30
       0 1180.48   14.74 1178.93   61.78 1171.84  100.33 1170.13  199.03 1166.87
   307.6 1162.15  368.38 1160.87  412.57 1159.37  454.71  1157.3  527.99 1156.58
  568.11 1152.72   580.8 1152.87  588.01 1154.73  592.29 1150.41  593.74 1150.29
  595.86 1150.37  604.16 1154.96  611.57 1157.61   652.3  1158.2  678.24 1159.74
  701.21 1160.19   718.1 1166.08  725.75 1167.82  746.65 1176.19  753.27 1177.93
   788.5 1179.85  805.32 1179.59  820.83 1180.96  864.95 1181.36  917.02 1180.86
#Mann= 3 , 0 , 0
       0     .08       0  588.01     .05       0  604.16     .08       0
Bank Sta=588.01,604.16
Exp/Cntr=0.5,0.3

Type RM Length L Ch R = 1 ,3798.466,77.32,76.95,76.39
BEGIN DESCRIPTION:
Upstream xs of Bridge 37111-0389
END DESCRIPTION:
XS GIS Cut Line= 4
  1083842.853652   667150.639086    1083497.0681   666979.151947
  1083335.343524   666926.362394  1083002.285502    666892.00274
#Sta/Elev= 30
       0  1179.3    46.4  1173.3    99.9  1168.3   225.4  1161.9     386  1157.2
  453.071150.138     472  1148.5  478.25 1150.35     485  1154.4     493    1155
   493.4  1156.1   554.7  1157.3   576.1  1158.9   611.4  1158.9   639.7  1161.3
   649.9  1163.9   659.5  1168.9   665.4  1170.8   685.5  1174.5   703.1  1173.1
   719.4  1176.5   730.3  1175.2   737.1  1177.5     745  1178.2   763.1  1176.9
   773.2  1179.4   782.4    1180   799.5  1180.7   809.4  1179.8   890.9  1183.2
#Mann= 3 , 0 , 0
       0     .08       0  453.07     .05       0  478.25     .08       0
#XS Ineff= 2 , 0
       0   408.1  1159.6   525.9       0  1159.6
Permanent Ineff=
       F       F
Bank Sta=453.07,478.25
Exp/Cntr=0.5,0.3

Type RM Length L Ch R = 3 ,3756.555,,,
BEGIN DESCRIPTION:
Bridge : 37111-0389
END DESCRIPTION:
Bridge Culvert--1,0,-1,-1, 0
Deck Dist Width WeirC Skew NumUp NumDn MinLoCord MaxHiCord MaxSubmerge Is_Ogee
31.9,20,2.6,0, 173, 173, , , 0.95, 0, 0,0,,
   -10.5    -9.6    -4.6     5.1     8.2      11    24.7    27.7    29.3    32.1
    35.1    40.6    44.7    46.9    51.6      54    60.3    68.2    69.6      74
    76.5    85.1    90.1    91.5    92.4    96.6     107   112.6   118.5   120.2
   128.4   134.8   135.7   140.4   142.7   150.8     156   157.3     158   161.9
   174.5   177.8   184.3   184.6   199.5   201.4   204.2   210.3   221.1   221.6
   224.5   225.7   225.9   241.7   242.2   242.7   248.7   255.2   263.6   267.8
     268   268.2   268.5   284.5   286.3   288.7     295   304.2   308.9     311
   325.9   326.7   327.1   331.9   342.4   349.4   352.9   353.7   365.2     369
   372.4   375.7   379.8   386.4   391.7   393.9   397.4   410.8   415.2   419.6
   420.3   420.8   420.9     440     440     494     494   499.7   509.4   510.2
   516.8   517.7   527.2   534.9   536.7   540.8   544.1   551.1   557.7   560.8
   562.9   565.4   570.9   573.3   584.8   586.2   593.5   594.4   595.3   604.3
   612.7   613.6   618.9   620.7   622.5   631.9   640.5   641.3   644.2   645.5
   645.8   658.2   665.4   669.2   672.8   681.9   691.4   694.5   697.6     709
   717.5   721.5   722.9   725.1   728.9   737.2   741.8   748.1   750.2   760.9
   770.4   772.8   775.7   785.9     803   803.6   804.4   805.2   816.1   824.9
   827.6   831.4   839.4   845.8     851   857.3     865   876.3   880.7   883.7
   899.2   904.7   910.8
  1177.9  1177.9  1177.4  1176.8  1176.6  1176.3  1175.4  1175.2  1175.1  1174.8
  1174.6  1174.3    1174  1173.9  1173.6  1173.5    1173  1172.7  1172.5    1172
  1171.9  1171.6  1171.4  1171.3  1171.2  1170.8  1170.2  1169.9  1169.6  1169.4
    1169  1168.6  1168.6  1168.3  1168.2  1167.9  1167.6  1167.6  1167.5  1167.1
  1166.7  1166.6  1166.1  1166.1  1165.5  1165.2  1164.9  1164.8  1164.7  1164.6
  1164.4  1164.3  1164.3  1163.7  1163.6  1163.6  1163.3  1163.1  1162.9  1162.8
  1162.8  1162.8  1162.8  1162.4  1162.2  1162.1  1162.1  1161.9  1161.6  1161.5
  1161.4  1161.4  1161.4    1161    1161    1161  1160.7  1160.7  1160.7  1160.7
  1160.6  1160.3  1160.3  1160.3  1160.3  1160.2    1160    1160    1160  1159.9
  1159.9  1159.8  1159.7  1159.7  1159.7  1159.7  1159.7  1159.6  1159.5  1159.5
  1159.3  1159.3  1159.4  1159.6  1159.5  1159.3  1159.5  1159.7  1159.8    1160
    1160    1160  1160.2  1160.3  1160.5  1160.5  1160.5  1160.5  1160.6  1160.8
  1161.4  1161.4  1161.4  1161.5  1161.6  1161.2  1162.6  1162.6  1162.5  1162.4
  1162.5  1163.1  1163.8    1164  1164.1  1164.8  1165.6  1165.5  1165.4  1166.4
  1167.3  1167.5  1167.5  1167.8  1168.2  1168.9  1169.4  1169.7  1169.9  1170.7
  1171.5  1171.7    1172  1172.8  1174.7  1174.7  1174.8  1174.9  1175.7  1176.6
  1176.8  1177.2  1177.8  1178.6  1179.2  1179.8  1180.6  1181.9  1182.4  1182.7
  1183.8  1184.1  1185.1
                                                                                
                                                                                
                                                                                
                                                                                
                                                                                
                                                                                
                                                                                
                                                                                
                                                                                
                                  1157.8  1157.8
                                                                                
                                                                                
                                                                                
                                                                                
                                                                                
                                                                                
                                                                                
                        
     1.6     2.4     7.4    17.1    20.2      23    36.8    39.7    41.3    44.2
    47.1    52.6    56.8      59    63.7      66    72.4    80.3    81.7      86
    88.6    97.1   102.1   103.5   104.4   108.6   119.1   124.6   130.5   132.3
   140.4   146.8   147.8   152.5   154.7   162.8     168   169.4     170   173.9
   186.5   189.9   196.4   196.6   211.6   213.4   216.2   222.3   233.1   233.6
   236.5   237.7   237.9   253.7   254.2   254.7   260.7   267.2   275.7   279.8
     280   280.2   280.5   296.5   298.3   300.8   307.1   316.3     321     323
   337.9   338.7   339.2     344   354.4   361.4   364.9   365.7   377.2   381.1
   384.5   387.7   391.8   398.4   403.7     406   409.4   422.8   427.2   431.6
   432.4   432.8     433     455     455     509     509   511.7   521.4   522.2
   528.8   529.7   539.2   546.9   548.7   552.8   556.2   563.1   569.7   572.8
   574.9   577.5   582.9   585.3   596.9   598.2   605.5   606.4   607.4   616.3
   624.7   625.6     631   632.7   634.6   643.9   652.6   653.3   656.2   657.5
   657.9   670.2   677.4   681.3   684.8   693.9   703.4   706.5   709.6     721
   729.6   733.5     735   737.2   740.9   749.2   753.8   760.1   762.2   772.9
   782.4   784.9   787.7   797.9   815.1   815.6   816.5   817.3   828.1   836.9
   839.6   843.4   851.4   857.9     863   869.3     877   888.4   892.8   895.7
   911.3   916.8   922.8
  1177.9  1177.9  1177.4  1176.8  1176.6  1176.3  1175.4  1175.2  1175.1  1174.8
  1174.6  1174.3    1174  1173.9  1173.6  1173.5    1173  1172.7  1172.5    1172
  1171.9  1171.6  1171.4  1171.3  1171.2  1170.8  1170.2  1169.9  1169.6  1169.4
    1169  1168.6  1168.6  1168.3  1168.2  1167.9  1167.6  1167.6  1167.5  1167.1
  1166.7  1166.6  1166.1  1166.1  1165.5  1165.2  1164.9  1164.8  1164.7  1164.6
  1164.4  1164.3  1164.3  1163.7  1163.6  1163.6  1163.3  1163.1  1162.9  1162.8
  1162.8  1162.8  1162.8  1162.4  1162.2  1162.1  1162.1  1161.9  1161.6  1161.5
  1161.4  1161.4  1161.4    1161    1161    1161  1160.7  1160.7  1160.7  1160.7
  1160.6  1160.3  1160.3  1160.3  1160.3  1160.2    1160    1160    1160  1159.9
  1159.9  1159.8  1159.7  1159.7  1159.7  1159.7  1159.7  1159.6  1159.5  1159.5
  1159.3  1159.3  1159.4  1159.6  1159.5  1159.3  1159.5  1159.7  1159.8    1160
    1160    1160  1160.2  1160.3  1160.5  1160.5  1160.5  1160.5  1160.6  1160.8
  1161.4  1161.4  1161.4  1161.5  1161.6  1161.2  1162.6  1162.6  1162.5  1162.4
  1162.5  1163.1  1163.8    1164  1164.1  1164.8  1165.6  1165.5  1165.4  1166.4
  1167.3  1167.5  1167.5  1167.8  1168.2  1168.9  1169.4  1169.7  1169.9  1170.7
  1171.5  1171.7    1172  1172.8  1174.7  1174.7  1174.8  1174.9  1175.7  1176.6
  1176.8  1177.2  1177.8  1178.6  1179.2  1179.8  1180.6  1181.9  1182.4  1182.7
  1183.8  1184.1  1185.1
                                                                                
                                                                                
                                                                                
                                                                                
                                                                                
                                                                                
                                                                                
                                                                                
                                                                                
                                  1157.8  1157.8
                                                                                
                                                                                
                                                                                
                                                                                
                                                                                
                                                                                
                                                                                
                        
Pier Skew, UpSta & Num, DnSta & Num=  ,458, 2 ,473, 2 , 0 , 0 , 0 ,,
       1       1
  1148.5  1158.3
       1       1
  1148.5  1158.3
Pier Skew, UpSta & Num, DnSta & Num=  ,476, 2 ,491, 2 , 0 , 0 , 0 ,,
       1       1
    1148  1158.3
       1       1
    1148  1158.3
BR Coef=-1 , 1 , 0 ,, 0 ,,,0.8,0,2,0,
WSPro=,,,, 1 ,,,, 0 ,,,, 0 ,,,,-1 ,-1 ,-1 , 0 , 0 , 0 , 0 , 0
BC Design=,, 0 ,, 0 ,,,,,,

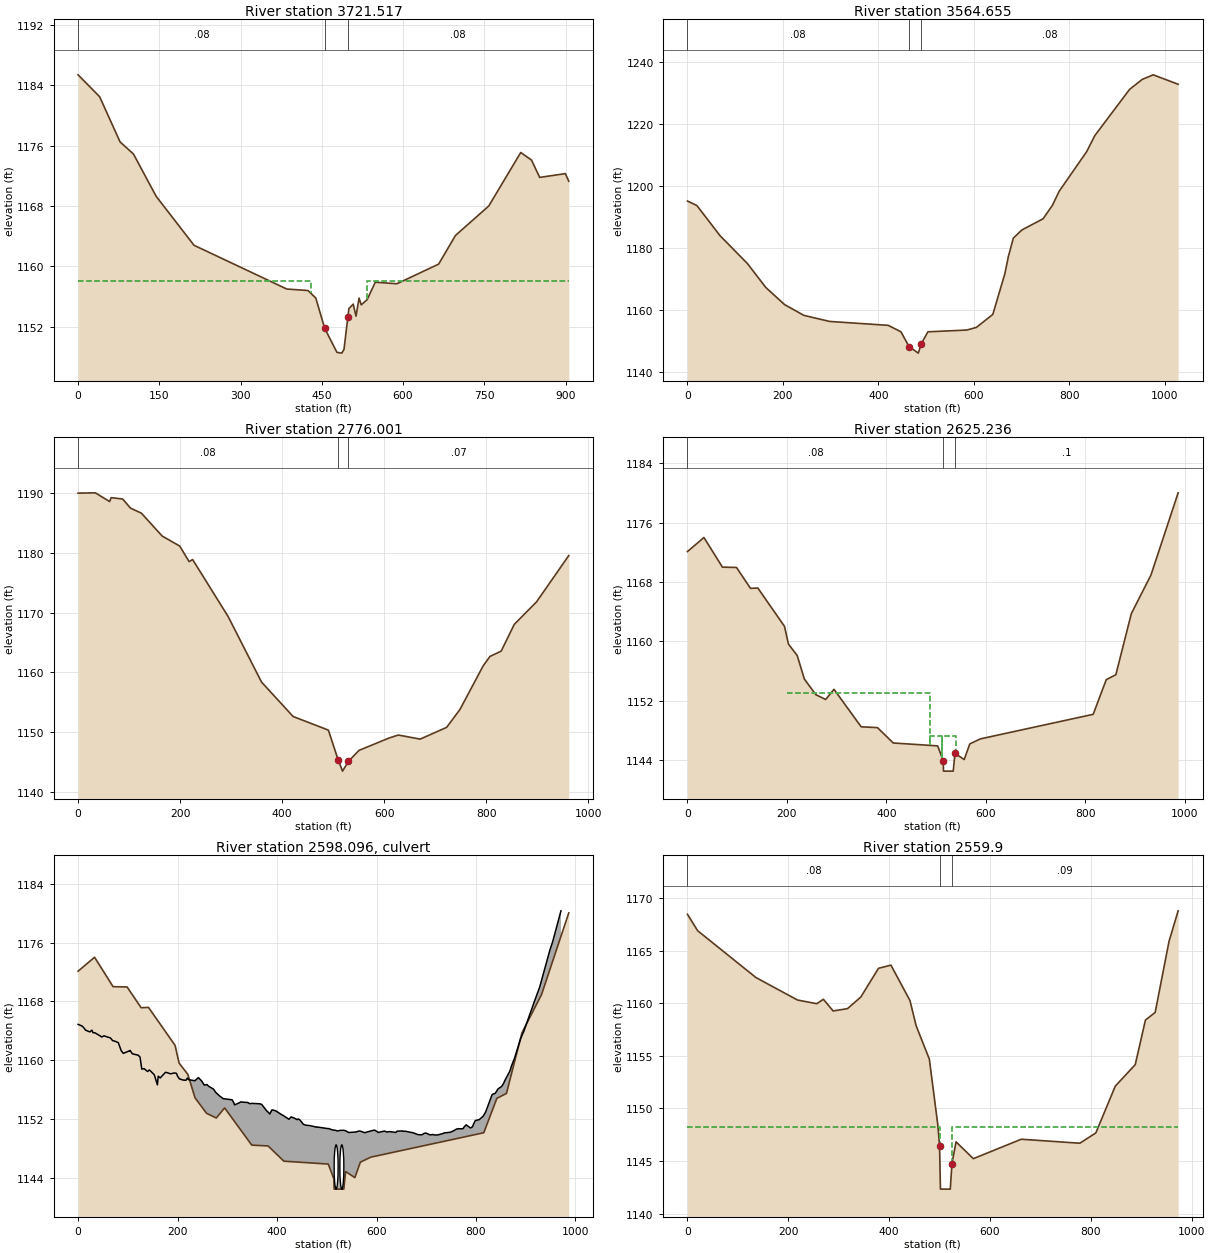
Type RM Length L Ch R = 1 ,3721.517,148,156.86,166.73
BEGIN DESCRIPTION:
Down stream xs of Bridge 37111-0389
END DESCRIPTION:
XS GIS Cut Line= 4
  1083901.471279   667064.991219  1083533.972273    666909.51088
  1083349.553557   666857.643087  1083055.699515   666743.005695
#Sta/Elev= 30
       0  1185.4    39.8  1182.5    77.6  1176.5   102.3  1174.9   144.1  1169.3
   214.1  1162.8   385.3    1157   424.6  1156.8   438.9  1155.8  455.421151.778
     478  1148.6     487  1148.5     491    1149  498.081153.248     500  1154.4
     508    1155   513.2  1153.4   518.8  1155.8   522.8  1154.9   533.8  1155.6
   548.7  1157.9   588.8  1157.7   665.7  1160.3   696.8  1164.1   758.2    1168
   817.3  1175.1   837.2  1174.1   852.3  1171.8   899.7  1172.3     906  1171.3
#Mann= 3 , 0 , 0
       0     .08       0  455.42     .05       0  498.08     .08       0
#XS Ineff= 2 , 0
       0     430    1158     534       0    1158
Permanent Ineff=
       F       F
Bank Sta=455.42,498.08
Exp/Cntr=0.5,0.3

Type RM Length L Ch R = 1 ,3564.655,776.67,788.65,804.47
XS GIS Cut Line= 3
  1083932.814098   666998.830802  1083529.524983    666760.66569
  1083072.423235   666437.115002
#Sta/Elev= 30
       0 1195.18   19.74 1193.73   68.55 1183.94  125.46 1175.02  164.25 1167.24
  203.68  1161.7     244 1158.23  298.11 1156.27  420.77 1155.01  447.46 1152.92
  464.31 1148.15  483.82 1146.03  490.11 1149.09  503.97 1152.92  585.54 1153.49
  605.58 1154.35  640.01 1158.55  665.36 1171.78  672.56 1177.23  683.02 1183.22
  701.01 1185.84  745.32 1189.45  764.97 1193.81  778.97 1198.33  836.91  1211.2
  853.66 1216.31  926.59 1231.26  953.39 1234.52  976.16 1235.97 1028.39 1232.92
#Mann= 3 , 0 , 0
       0     .08       0  464.31     .05       0  490.11     .08       0
Bank Sta=464.31,490.11
Exp/Cntr=0.3,0.1

Type RM Length L Ch R = 1 ,2776.001,127.49,150.76,134.96
XS GIS Cut Line= 3
  1084436.704506   666777.152694  1084131.491976   666354.969325
  1083948.551584    665953.52906
#Sta/Elev= 30
       0 1189.96   33.86 1190.01   61.89 1188.55   64.93  1189.2   87.42 1188.98
  102.94 1187.44  124.21 1186.61  164.84 1182.79  199.23 1181.12  217.68 1178.52
  224.63 1178.86  294.38 1169.32  359.72 1158.39  421.61 1152.64  490.81 1150.36
  510.28  1145.3  518.59 1143.51  530.12 1145.15  550.91 1146.98  609.75 1149.04
  627.89 1149.54  670.75 1148.86  722.63 1150.82  748.82 1153.82   794.4 1161.12
   807.6 1162.67  829.64 1163.57  855.24 1168.03  898.93 1171.79  962.11 1179.53
#Mann= 3 , 0 , 0
       0     .08       0  510.28    .049       0  530.12     .07       0
Bank Sta=510.28,530.12
Exp/Cntr=0.5,0.3

Type RM Length L Ch R = 1 ,2625.236,92.02,65.34,85.66
XS GIS Cut Line= 6
  1084533.474902   666731.993169  1084339.934111   666473.938745
  1084261.590048   666338.011302  1084262.573364   666287.862547
  1084221.659171   666261.043882  1084021.666999   665908.369535
#Sta/Elev= 30
       0 1172.11   33.16    1174   70.36 1170.01   98.56 1169.97  126.81 1167.15
  141.52  1167.2  195.09 1162.04  203.03 1159.65  220.66 1158.11  235.05 1154.94
  258.22 1152.83  277.85 1152.19  294.64 1153.56  349.22 1148.51  381.96  1148.4
  413.75 1146.33  502.99 1145.94  514.16 1143.96  514.78 1142.54  534.28 1142.54
  537.83 1144.93  556.46  1144.1  567.57  1146.2  588.74 1146.88  815.68 1150.19
     842 1154.86  861.26 1155.52  892.38 1163.75   931.8 1168.94  986.51 1180.02
#Mann= 3 , 0 , 0
       0     .08       0  514.16    .049       0  537.83      .1       0
#XS Ineff= 3 ,-1
     200     488    1153     488     512  1147.3     512     539  1147.3
Permanent Ineff=
       F       F       F
Bank Sta=514.16,537.83
Exp/Cntr=0.5,0.3

Type RM Length L Ch R = 2 ,2598.096,,,
BEGIN DESCRIPTION:
Culvert 37111-0390
END DESCRIPTION:
Bridge Culvert--1,0,-1,-1, 0
Deck Dist Width WeirC Skew NumUp NumDn MinLoCord MaxHiCord MaxSubmerge Is_Ogee
20,24,2.6,0, 200, 200, 1149.88, , 0.95, 0, 0,0,,
       0     1.1    7.96   11.58   15.05   23.52   28.07   29.84   33.61    45.1
   47.18      48   52.32   57.61   64.94   69.65   72.86   76.27   80.84   86.72
   90.96  102.84  104.03  104.51   109.1  115.14  120.89  124.55  128.06  132.81
  139.65  143.32  153.09   159.5  161.16  165.21   175.8  178.01  179.29  185.91
  193.25  197.72  199.98   203.7  210.12  210.55  216.79  219.87   222.2  234.67
  234.78  234.83   241.9  248.62  253.83  256.69  259.04  262.08  272.29  277.22
   277.9  284.15  290.81  291.44  293.52  309.72  313.34  314.64  322.96  326.05
  327.32  328.13  332.61     341  345.32  346.69   351.4  365.52  369.19  379.68
  381.96  385.37  389.58  391.36  397.45  409.73  411.07  422.23  423.88  428.21
  434.72  440.48  442.64  446.14  449.48  452.92  458.31  465.97  466.37  478.27
  479.25  480.25  501.72  504.54  508.82  513.02  518.11  520.95  525.75  533.22
     538   543.1  544.46  545.61  558.35  560.56     564  567.37  576.88  580.23
  584.51  589.39   595.7  597.06   600.6  603.42  604.36  616.47   619.4  622.06
   625.9   634.5  638.38  641.31  652.22  653.32  656.48  659.37   659.6  661.45
  672.19  674.15   678.5   682.9  691.07  695.74  699.21  707.55   713.2  717.87
  719.36  723.29  733.39  737.16  739.93  748.27  752.99  760.67  761.31  761.63
  765.65  773.78  776.22  780.22  788.87  792.99  795.03  798.53  806.42  811.61
  814.44  819.35  830.83  832.82  838.56  844.42  851.41  855.46  857.83  867.46
  869.56  870.79  877.38  883.49   889.8  894.24  896.17   897.8  908.71  914.68
  915.25  921.74  928.02   930.4  935.84  937.67  948.51  953.07  955.04   970.8
 1164.89 1164.87 1164.67 1164.43 1164.11 1163.87 1164.11 1163.76 1163.76  1163.3
 1163.19  1163.2 1163.34 1163.21 1163.06 1162.68 1162.64 1162.54 1162.42 1161.32
 1160.96 1161.29 1161.24 1161.37  1160.9 1160.81 1160.71 1160.46 1158.83 1158.88
  1158.5 1158.71 1158.07 1156.69 1157.86 1157.63 1158.39 1158.35 1158.34 1158.18
  1158.3 1158.26 1157.87  1157.5 1157.36 1157.35  1157.3 1157.61 1157.39 1157.25
 1157.23 1157.25 1157.67  1157.2 1156.65  1156.7 1156.73 1156.52 1156.11 1155.62
  1155.6  1155.2 1154.87 1154.81  1154.8 1154.66 1154.22 1153.97 1154.22 1154.34
 1154.38 1154.37 1154.33  1154.3 1154.12 1154.16 1154.17 1154.12 1154.03 1153.12
    1153 1152.73 1153.28 1153.28 1153.16 1152.62 1152.59 1152.09 1152.02 1152.34
 1152.18 1151.97 1152.07 1151.91 1151.64 1151.33 1151.21 1151.17 1151.16 1150.97
 1150.93 1150.97 1150.76 1150.75 1150.63 1150.56 1150.51 1150.43  1150.5 1150.53
 1150.46 1150.25  1150.2 1150.23 1150.29 1150.33 1150.42 1150.41 1150.19 1150.29
 1150.35 1150.45 1150.55 1150.52 1150.37 1150.22 1150.25 1150.42 1150.31  1150.3
 1150.34 1150.28 1150.22  1150.4 1150.44 1150.38  1150.4 1150.38 1150.38 1150.34
 1150.21 1150.17 1150.06 1149.94 1149.91  1150.1 1150.16  1149.9 1149.95 1149.88
 1149.89  1149.9 1150.08  1150.2 1150.19 1150.26 1150.39 1150.68  1150.7 1150.71
 1150.73 1150.73 1150.99 1151.26 1150.84    1151 1151.36 1151.84 1151.97 1152.27
 1152.44    1153 1155.09  1155.4 1155.53 1156.15 1156.47 1156.88 1157.26 1158.47
 1158.85 1159.16 1160.28 1161.62 1162.95 1163.67 1163.94 1164.28 1166.32 1167.48
 1167.61 1168.81 1169.95 1170.53  1171.8 1172.27 1174.97 1175.89 1176.34  1180.3
                                                                                
                                                                                
                                                                                
                                                                                
                                                                                
                                                                                
                                                                                
                                                                                
                                                                                
                                                                                
                                                                                
                                                                                
                                                                                
                                                                                
                                                                                
                                                                                
                                                                                
                                                                                
                                                                                
                                                                                
       0     1.1    7.96   11.58   15.05   23.52   28.07   29.84   33.61    45.1
   47.18      48   52.32   57.61   64.94   69.65   72.86   76.27   80.84   86.72
   90.96  102.84  104.03  104.51   109.1  115.14  120.89  124.55  128.06  132.81
  139.65  143.32  153.09   159.5  161.16  165.21   175.8  178.01  179.29  185.91
  193.25  197.72  199.98   203.7  210.12  210.55  216.79  219.87   222.2  234.67
  234.78  234.83   241.9  248.62  253.83  256.69  259.04  262.08  272.29  277.22
   277.9  284.15  290.81  291.44  293.52  309.72  313.34  314.64  322.96  326.05
  327.32  328.13  332.61     341  345.32  346.69   351.4  365.52  369.19  379.68
  381.96  385.37  389.58  391.36  397.45  409.73  411.07  422.23  423.88  428.21
  434.72  440.48  442.64  446.14  449.48  452.92  458.31  465.97  466.37  478.27
  479.25  480.25  501.72  504.54  508.82  513.02  518.11  520.95  525.75  533.22
     538   543.1  544.46  545.61  558.35  560.56     564  567.37  576.88  580.23
  584.51  589.39   595.7  597.06   600.6  603.42  604.36  616.47   619.4  622.06
   625.9   634.5  638.38  641.31  652.22  653.32  656.48  659.37   659.6  661.45
  672.19  674.15   678.5   682.9  691.07  695.74  699.21  707.55   713.2  717.87
  719.36  723.29  733.39  737.16  739.93  748.27  752.99  760.67  761.31  761.63
  765.65  773.78  776.22  780.22  788.87  792.99  795.03  798.53  806.42  811.61
  814.44  819.35  830.83  832.82  838.56  844.42  851.41  855.46  857.83  867.46
  869.56  870.79  877.38  883.49   889.8  894.24  896.17   897.8  908.71  914.68
  915.25  921.74  928.02   930.4  935.84  937.67  948.51  953.07  955.04   970.8
 1164.89 1164.87 1164.67 1164.43 1164.11 1163.87 1164.11 1163.76 1163.76  1163.3
 1163.19  1163.2 1163.34 1163.21 1163.06 1162.68 1162.64 1162.54 1162.42 1161.32
 1160.96 1161.29 1161.24 1161.37  1160.9 1160.81 1160.71 1160.46 1158.83 1158.88
  1158.5 1158.71 1158.07 1156.69 1157.86 1157.63 1158.39 1158.35 1158.34 1158.18
  1158.3 1158.26 1157.87  1157.5 1157.36 1157.35  1157.3 1157.61 1157.39 1157.25
 1157.23 1157.25 1157.67  1157.2 1156.65  1156.7 1156.73 1156.52 1156.11 1155.62
  1155.6  1155.2 1154.87 1154.81  1154.8 1154.66 1154.22 1153.97 1154.22 1154.34
 1154.38 1154.37 1154.33  1154.3 1154.12 1154.16 1154.17 1154.12 1154.03 1153.12
    1153 1152.73 1153.28 1153.28 1153.16 1152.62 1152.59 1152.09 1152.02 1152.34
 1152.18 1151.97 1152.07 1151.91 1151.64 1151.33 1151.21 1151.17 1151.16 1150.97
 1150.93 1150.97 1150.76 1150.75 1150.63 1150.56 1150.51 1150.43  1150.5 1150.53
 1150.46 1150.25  1150.2 1150.23 1150.29 1150.33 1150.42 1150.41 1150.19 1150.29
 1150.35 1150.45 1150.55 1150.52 1150.37 1150.22 1150.25 1150.42 1150.31  1150.3
 1150.34 1150.28 1150.22  1150.4 1150.44 1150.38  1150.4 1150.38 1150.38 1150.34
 1150.21 1150.17 1150.06 1149.94 1149.91  1150.1 1150.16  1149.9 1149.95 1149.88
 1149.89  1149.9 1150.08  1150.2 1150.19 1150.26 1150.39 1150.68  1150.7 1150.71
 1150.73 1150.73 1150.99 1151.26 1150.84    1151 1151.36 1151.84 1151.97 1152.27
 1152.44    1153 1155.09  1155.4 1155.53 1156.15 1156.47 1156.88 1157.26 1158.47
 1158.85 1159.16 1160.28 1161.62 1162.95 1163.67 1163.94 1164.28 1166.32 1167.48
 1167.61 1168.81 1169.95 1170.53  1171.8 1172.27 1174.97 1175.89 1176.34  1180.3
                                                                                
                                                                                
                                                                                
                                                                                
                                                                                
                                                                                
                                                                                
                                                                                
                                                                                
                                                                                
                                                                                
                                                                                
                                                                                
                                                                                
                                                                                
                                                                                
                                                                                
                                                                                
                                                                                
                                                                                
BR Coef=-1 , 0 , 0 ,, 0 ,,,0.8,-1,,0,
WSPro=,,,, 1 ,,,, 0 ,,,, 0 ,,,,-1 ,-1 ,-1 , 0 , 0 , 0 , 0 , 0
Multiple Barrel Culv=5,6,8,50,0.024,0.5,1,41,1,1142.54,1142.32, 2,Culvert #1  , 0 ,7.5
  518.78  505.79  530.28  517.29
Culvert Bottom n=0.024
BC Design=,, 0 ,, 0 ,,,,,,

Type RM Length L Ch R = 1 ,2559.9  ,313.56,318.84,306.01
XS GIS Cut Line= 6
  1084638.847115   666650.275936  1084443.155851   666424.478347
  1084352.836801   666288.999772  1084322.063513   666266.721433
  1084251.765497   666054.600364  1084144.242847   665828.802775
#Sta/Elev= 30
       0 1168.48   20.19 1166.92  135.81 1162.46   218.3 1160.32  256.49 1159.97
  269.63 1160.39  288.95 1159.28  317.47  1159.5  343.94 1160.61  378.93 1163.34
   403.6 1163.64  441.33 1160.27  453.54 1157.88  479.75  1154.7  496.47 1148.48
  500.05 1146.45  501.79 1142.32  521.29 1142.32   524.6 1144.74  532.75 1146.82
  567.05 1145.22  662.07 1147.07  778.26 1146.69     810 1147.67  848.53 1152.12
  888.17 1154.17  908.36 1158.41  927.69 1159.14  955.19 1165.91  973.26 1168.81
#Mann= 3 , 0 , 0
       0     .08       0  500.05    .049       0   524.6     .09       0
#XS Ineff= 2 , 0
          499.94 1148.28  524.63         1148.27
Permanent Ineff=
       F       F
Bank Sta=500.05,524.6
Exp/Cntr=0.5,0.3

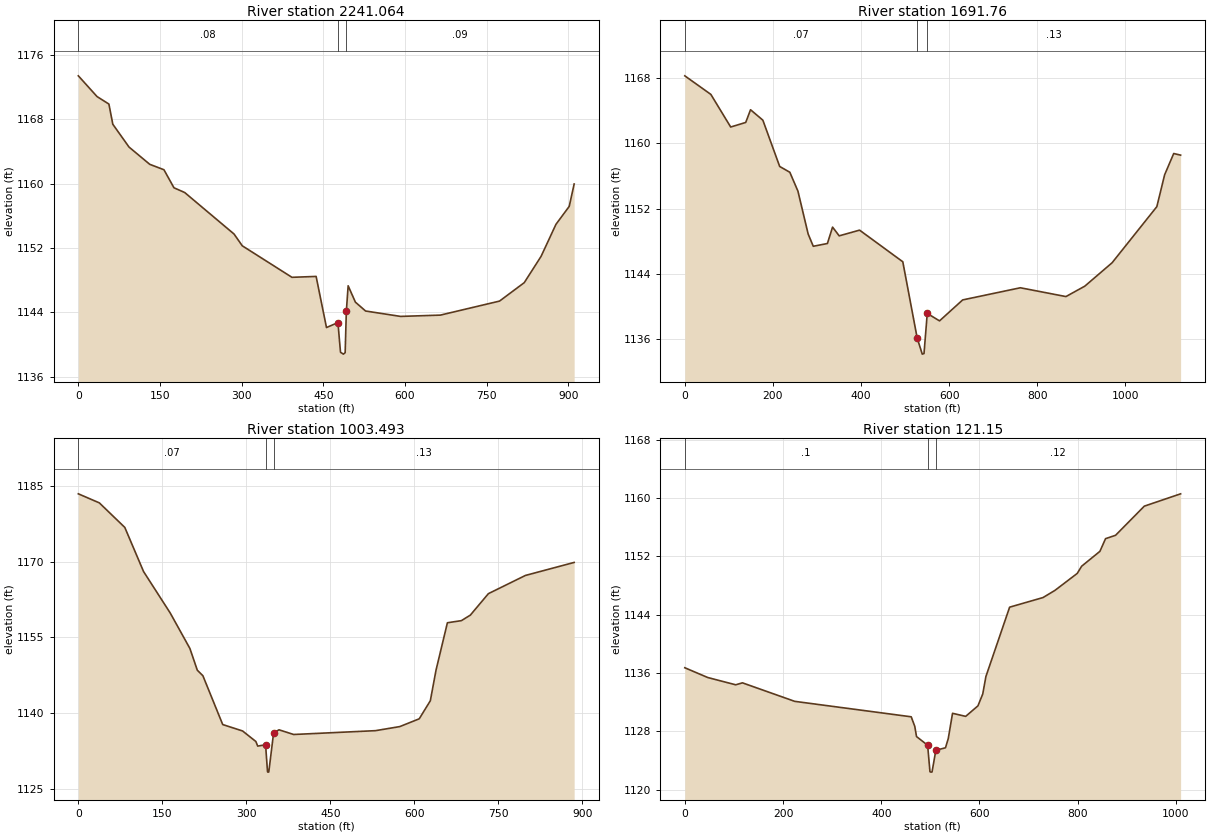
Type RM Length L Ch R = 1 ,2241.064,556.5,549.3,536.24
XS GIS Cut Line= 3
  1084822.726304   666438.858353  1084558.220535   666111.989459
  1084274.360693   665712.005114
#Sta/Elev= 30
       0 1173.36   34.49 1170.78   56.14 1169.86   63.38 1167.35   93.16 1164.52
  131.22 1162.38  157.28 1161.71   175.7 1159.47  195.45 1158.88  286.08 1153.73
  301.24 1152.27  392.46 1148.36  436.88 1148.47  455.92 1142.13  476.96 1142.74
  481.69 1139.06  487.05 1138.83  490.24 1139.01   492.4 1144.14  495.73 1147.31
  509.03 1145.28  527.74 1144.18  591.96 1143.51  665.13 1143.67  773.85 1145.41
  819.31  1147.7  850.18 1150.96  877.58 1154.94   901.9 1157.16  910.96 1159.94
#Mann= 3 , 0 , 0
       0     .08       0  476.96    .049       0   492.4     .09       0
Bank Sta=476.96,492.4
Exp/Cntr=0.3,0.1

Type RM Length L Ch R = 1 ,1691.76 ,685,688.267,690
XS GIS Cut Line= 3
  1085309.502548   666035.629714  1084893.028642   665693.838406
  1084390.296242   665391.787975
#Sta/Elev= 30
       0 1168.28   59.16    1166  104.14    1162  138.27 1162.56  149.21 1164.12
  177.14 1162.84  215.36 1157.16  238.38 1156.45  256.79 1154.13  279.94 1148.88
  291.56 1147.37  323.64 1147.71  335.36 1149.72  350.42 1148.65  396.62 1149.35
  494.75 1145.47  527.38 1136.12  538.89 1134.14  542.89 1134.21  550.25 1139.13
  578.13 1138.22  630.63 1140.79  761.56 1142.28  864.98  1141.2  907.86 1142.48
  969.78 1145.35 1071.27 1152.23 1088.97 1156.14 1109.59 1158.75 1125.26 1158.55
#Mann= 3 , 0 , 0
       0     .07       0  527.38    .048       0  550.25     .13       0
Bank Sta=527.38,550.25
Exp/Cntr=0.3,0.1

Type RM Length L Ch R = 1 ,1003.493,866.06,882.34,886.25
XS GIS Cut Line= 4
  1085353.804571    665156.39477  1085096.893675   665060.977533
  1084944.639873   665055.727382  1084550.880135   664819.471525
#Sta/Elev= 30
       0 1183.43    37.5 1181.64   83.01 1176.77  116.52 1168.02  164.21 1159.79
   199.3 1152.77  212.53 1148.46  222.48 1147.37   257.9 1137.69  293.34 1136.42
  317.12 1134.33  320.38 1133.42  334.44 1133.68  337.92 1128.33  338.61 1128.26
  340.17 1128.28  348.79 1136.06  358.46 1136.65   384.6 1135.72  530.88 1136.48
  574.25 1137.29  608.89 1138.83  628.71 1142.41  638.95 1148.51  659.21 1157.87
   684.2 1158.29  700.13 1159.38  732.43 1163.64  798.57 1167.25   885.6 1169.83
#Mann= 3 , 0 , 0
       0     .07       0  334.44    .048       0  348.79     .13       0
Bank Sta=334.44,348.79
Exp/Cntr=0.3,0.1

Type RM Length L Ch R = 1 ,121.15  ,130.15,121.15,110.94
XS GIS Cut Line= 4
  1085561.732751   664501.576092  1085285.529628   664365.026206
  1085015.533282   664253.303609  1084608.987122   664206.752493
#Sta/Elev= 30
       0 1136.71    46.7 1135.37  103.69 1134.37  117.35 1134.64  223.82  1132.1
  460.99 1129.98  468.25 1128.67   471.8 1127.27  494.41 1126.08  499.17 1122.45
  501.19 1122.39  503.39 1122.41  511.15 1125.39  530.78 1125.73  536.42 1126.99
  545.13 1130.46  571.89 1130.04  596.84 1131.48  606.65 1133.11  613.08 1135.51
  661.37 1145.02  729.38 1146.34  753.57 1147.32  798.99 1149.65  808.03 1150.64
   845.2 1152.68  856.68 1154.42  877.04 1154.88  935.62 1158.88 1009.52 1160.57
#Mann= 3 , 0 , 0
       0      .1       0  494.41    .048       0  511.15     .12       0
Bank Sta=494.41,511.15
Exp/Cntr=0.3,0.1

Chan Stop Cuts=-1
Use User Specified Reach Order=0
User Specified Reach Order=HarrisCr        ,Main