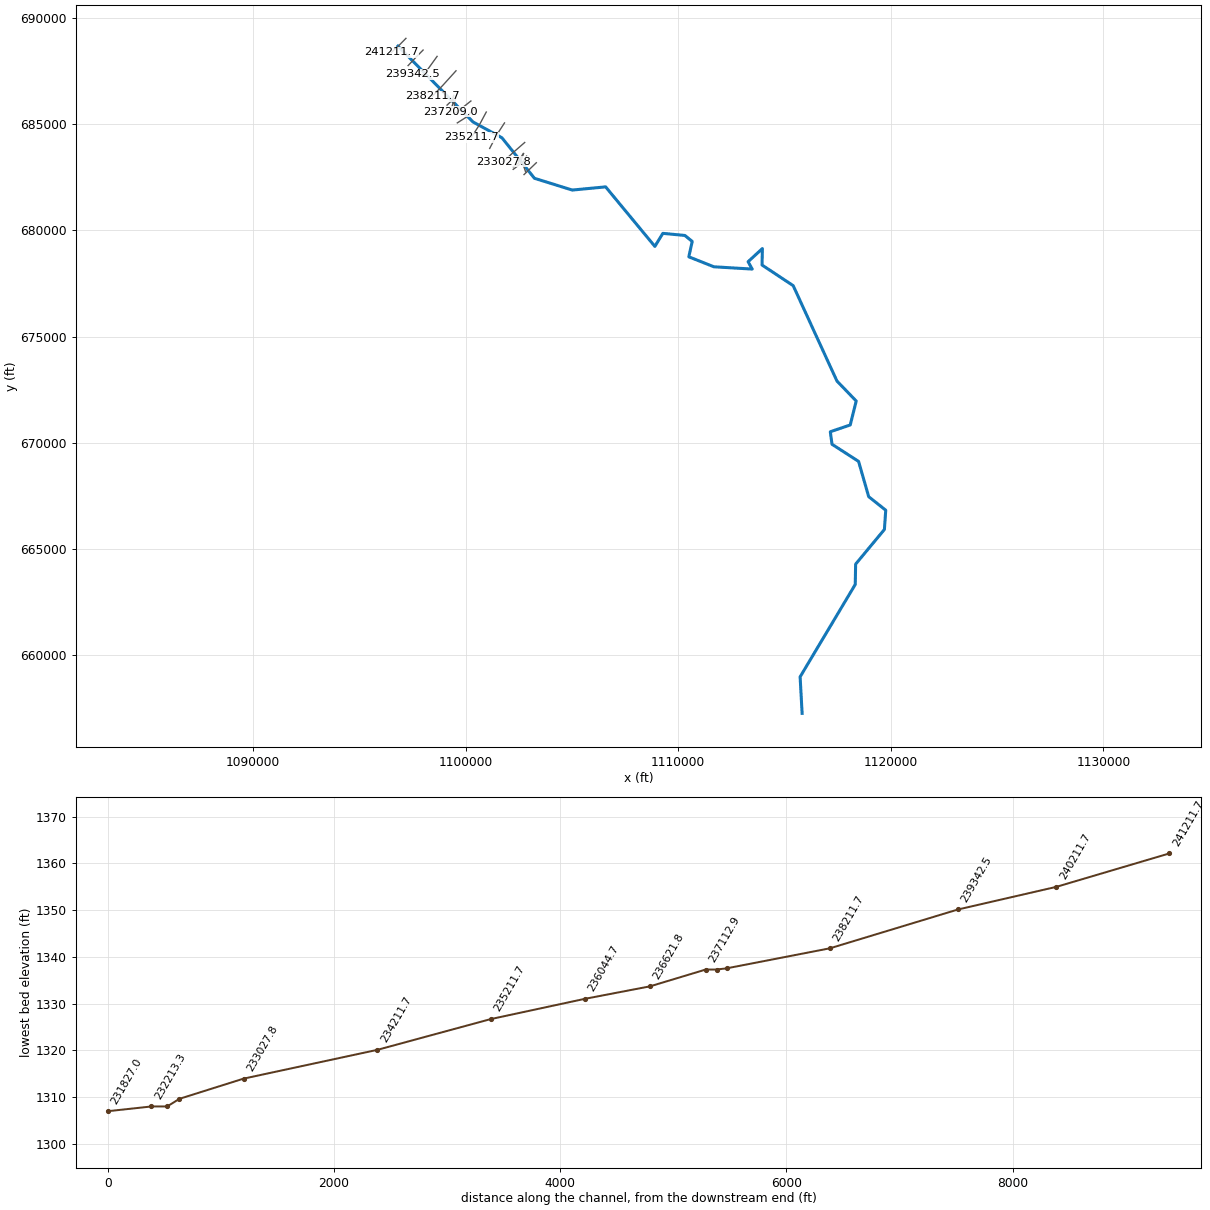
--- 2ndBroadRv.prj (project) ---

Proj Title=2ndBroadRv
Current Plan=p01
Default Exp/Contr=0.3,0.1
English Units
Geom File=g01
Flow File=f01
Plan File=p01
Y Axis Title=Elevation
X Axis Title(PF)=Main Channel Distance
X Axis Title(XS)=Station
BEGIN DESCRIPTION:
END DESCRIPTION:
DSS Export Rating Curves= 0
DSS Export Rating Curve Sorted= 0
DSS Export Volume Flow Curves= 0
DXF OffsetX= 0
DXF OffsetY= 0
DXF ScaleX= 1
DXF ScaleY= 10

--- 2ndBroadRv.p01 (plan) ---

Plan Title=LD Study - 100 YR
Program Version=3.12
Short Identifier=lds
Geom File=g01
Flow File=f01
Subcritical Flow
K Sum by GR= 0
Std Step Tol= 0.01
Critical Tol= 0.01
Num of Std Step Trials= 20
Max Error Tol= 0.3
Flow Tol Ratio= 0.001
Split Flow NTrial= 30
Split Flow Tol= 0.02
Split Flow Ratio= 0.02
Log Output Level= 0
Friction Slope Method= 1
Unsteady Friction Slope Method= 2
Unsteady Bridges Friction Slope Method= 1
Calc Critical at every XS
Parabolic Critical Depth
Global Vel Dist= 0 , 0 , 0
Global Log Level= 0
CheckData=True
Encroach Param=-1 ,10,10, 2
Encroach River=2ndBroadRv
Encroach Reach=Main
Encroach Node=241211.7
       1  500.97     545
Encroach Node=240211.7
       1  456.21  525.72
Encroach Node=239342.5
       1     875  981.45
Encroach Node=238211.7
       1  834.83     950
Encroach Node=237299.1
       1  207.04  259.23
Encroach Node=237209.0
       1  168.09  217.08
Encroach Node=237112.9
       1  190.82  239.81
Encroach Node=236621.8
       1  356.73  533.98
Encroach Node=236044.7
       1  331.09  504.73
Encroach Node=235211.7
       1  659.27  710.15
Encroach Node=234211.7
       1  682.34   738.8
Encroach Node=233027.8
       1  740.02  829.74
Encroach Node=232462.0
       1  417.25  460.81
Encroach Node=232353.0
       1  417.25  487.01
Encroach Node=232213.3
       1  477.33  547.09
Encroach Node=231827.0
       1  421.84  576.82
Encroach Node=231211.7
       1  624.63  775.64
Encroach Node=230211.7
       1  606.19  703.16
Encroach Node=229729.2
       1  367.45  515.21
Encroach Node=229416.7
       1  333.13  425.83
Encroach Node=229347.1
       1   352.8  445.51
Encroach Node=228874.8
       1   781.7  886.66
Encroach Node=228454.6
       1  885.55 1035.67
Encroach Node=227553.7
       1  369.05     547
Encroach Node=227418.4
       1  144.99  382.02
Encroach Node=227337.8
       1  147.11  384.13
Encroach Node=226917.6
       1   558.3  701.62
Encroach Node=225677.0
       1  782.37   837.9
Encroach Node=224964.2
       1  375.96  688.08
Encroach Node=224772.5
       1  616.23  860.62
Encroach Node=224606.8
       1  281.62  412.44
Encroach Node=223974.5
       1  241.84  335.85
Encroach Node=223682.1
       1  746.69    1035
Encroach Node=223159.2
       1   86.92  163.35
Encroach Node=222727.8
       1    1111    1146
Encroach Node=222497.9
       1  456.48  525.34
Encroach Node=222391.5
       1  418.35  487.21
Encroach Node=221965.6
       1  571.67 1130.42
Encroach Node=220678.9
       1  937.06 1130.94
Encroach Node=220186.1
       1  770.29  841.21
Encroach Node=218965.2
       1   919.9  981.55
Encroach Node=217791.7
       1  325.49   446.1
Encroach Node=217686.7
       1   382.2   435.7
Encroach Node=217600.6
       1     225     280
Encroach Node=217473.4
       1     320  394.51
Encroach Node=217400.1
       1  332.13  450.76
Encroach Node=217260.7
       1   316.4   370.5
Encroach Node=216927.3
       1    78.4  128.64
Encroach Node=216521.8
       1    54.8     112
Encroach Node=216121.1
       1   55.85    94.7
Encroach Node=215827.1
       1      72     151
Encroach Node=215654.2
       1      51    95.4
Encroach Node=215376.6
       1   34.22  120.62
Encroach Node=215037.2
       1     110  187.48
Encroach Node=214740.5
       1     200     348
Encroach Node=214517.8
       1 1234.12    1292
Encroach Node=214079.0
       1     500   571.7
Encroach Node=213566.3
       1   363.9     468
Encroach Node=213365.4
       1  108.14  202.07
Encroach Node=213235.3
       1     150  241.37
Encroach Node=213153.9
       1  619.08  684.06
Encroach Node=212461.4
       1   375.7  449.09
Encroach Node=211897.6
       1     830  884.66
Encroach Node=211122.6
       1     274     330
Encroach Node=210211.7
       1  960.87 1035.37
Encroach Node=209331.1
       1     235     420
Encroach Node=208845.5
       1  849.81 1134.17
Encroach Node=208483.1
       1 1114.18 1180.54
Encroach Node=207883.3
       1   133.7     178
Encroach Node=207664.1
       1   401.4   447.4
Encroach Node=207574.0
       1  118.95  207.54
Encroach Node=207406.6
       1  156.13  244.72
Encroach Node=207086.1
       1  460.13  611.64
Encroach Node=206307.5
       1  378.45  424.48
Encroach Node=206252.2
       1  150.57  271.96
Encroach Node=206189.5
       1  151.26     260
Encroach Node=206082.3
       1  474.35  574.09
Encroach Node=205899.4
       1  550.72  685.22
Encroach Node=205545.2
       1     365  474.92
Encroach Node=204964.6
       1  212.23  276.06
Encroach Node=204556.1
       1  261.33  330.13
Encroach Node=204484.8
       1  108.09   169.1
Encroach Node=204369.3
       1    48.6   138.5
Encroach Node=204187.8
       1     440     530
Encroach Node=203618.5
       1     679     950
Encroach Node=203250.0
       1  827.12  930.83
Encroach Node=202036.8
       1  555.47   793.4
Encroach Node=201455.3
       1  597.57   763.1
Encroach Node=200576.0
       1   708.7   889.2
Encroach Node=199211.7
       1  693.51 1025.85
Encroach Node=198005.1
       1 1037.15 1339.44
Encroach Node=197211.7
       1  518.23  825.53
Encroach Node=196211.7
       1  455.86   832.5
Encroach Node=195239.8
       1  346.83  842.91
Encroach Node=193888.7
       1  443.07  535.99
Encroach Node=193211.7
       1  646.23  719.25
Encroach Node=192437.0
       1  431.77  509.32
Encroach Node=192244.8
       1     215  446.77
Encroach Node=192096.6
       1     240     517
Encroach Node=191849.6
       1  446.77  523.32
Encroach Node=190944.2
       1  572.38  804.67
Encroach Node=190221.7
       1  588.64  945.91
Encroach Node=188988.4
       1  540.47  809.64
Encroach Node=187481.
       1  675.25   756.6
Computation Interval=1HOUR
Output Interval=1HOUR
Run HTab= 0
Run UNet= 0
Run PostProcess= 0
UNET Theta= 1
UNET Theta Warmup= 1
UNET ZTol= 0.02
UNET ZSATol= 0.05
UNET MxIter= 20
UNET MaxInSteps= 0
UNET DtIC= 0
UNET DtMin= 0
UNET MaxCRTS= 20
UNET WFStab= 2
UNET SFStab= 1
UNET WFX= 1
UNET SFX= 1
UNET DSS MLevel= 4
UNET DZMax Abort= 100
UNET Convert EG Bridges=-1
UNET Use Existing IB Tables=-1
UNET Froude Reduction=False
UNET Froude Limit= 1
UNET Froude Power= 10
Instantaneous Interval=1HOUR
Write IC File= 0
Echo Input=False
Echo Output=False
Write Detailed= 0
Detailed Automatic Start=False, 10

--- 2ndBroadRv.f01 (steady flow) ---

Flow Title=2ndBroadRv
Program Version=3.12
Number of Profiles= 2
Profile Names=P100yr,Encroachments
River Rch & RM=2ndBroadRv,Main            ,241211.7
    1560    1560
River Rch & RM=2ndBroadRv,Main            ,238211.7
    1760    1760
River Rch & RM=2ndBroadRv,Main            ,236621.8
    1900    1900
River Rch & RM=2ndBroadRv,Main            ,235211.7
    2090    2090
River Rch & RM=2ndBroadRv,Main            ,228874.8
    2400    2400
River Rch & RM=2ndBroadRv,Main            ,225677.0
    3300    3330
River Rch & RM=2ndBroadRv,Main            ,220186.1
    3980    3980
River Rch & RM=2ndBroadRv,Main            ,214517.8
    4200    4200
River Rch & RM=2ndBroadRv,Main            ,208845.5
    4630    4630
River Rch & RM=2ndBroadRv,Main            ,205899.4
    5080    5080
River Rch & RM=2ndBroadRv,Main            ,198005.1
    6040    6040
Boundary for River Rch & Prof#=2ndBroadRv,Main            , 1
Up Type= 0
Dn Type= 3
Dn Slope=0.005
DSS Import GetInterval= 0
DSS Import GetPeak= 0
DSS Import FillOption= 0

--- 2ndBroadRv.g01 (geometry) ---

Geom Title=2ndBroadRv
Program Version=3.12

River Reach=2ndBroadRv      ,Main
Reach XY= 30
  1096817.378174   688665.878274  1100347.999093    685097.05806
  1101705.749341   684354.559736  1103237.002081   682448.309997
  1105014.748042   681894.502138  1106584.879987   682044.497668
  1108900.877158   679243.128566  1109275.878245   679857.692405
  1110314.128239   679758.749435  1110657.880935   679477.501696
  1110498.132851   678753.558247  1111678.628727    678284.81203
  1113480.749962   678177.189616  1113286.378368    678524.37887
  1113959.883641   679142.440706  1113942.631281   678368.128739
  1115407.881067   677397.630719  1117466.878853   672909.811464
  1118373.131158   671970.561791  1118091.875201   670843.809509
  1117154.382723   670524.378868  1117234.250612   669935.808228
  1118484.251526   669130.309352  1118959.879034   667470.561007
  1119761.998702   666833.440482  1119699.497877   665927.192309
   1118345.38072   664296.939247  1118328.001395   663340.379862
  1115734.250351   658994.880233  1115827.999612   657276.129015

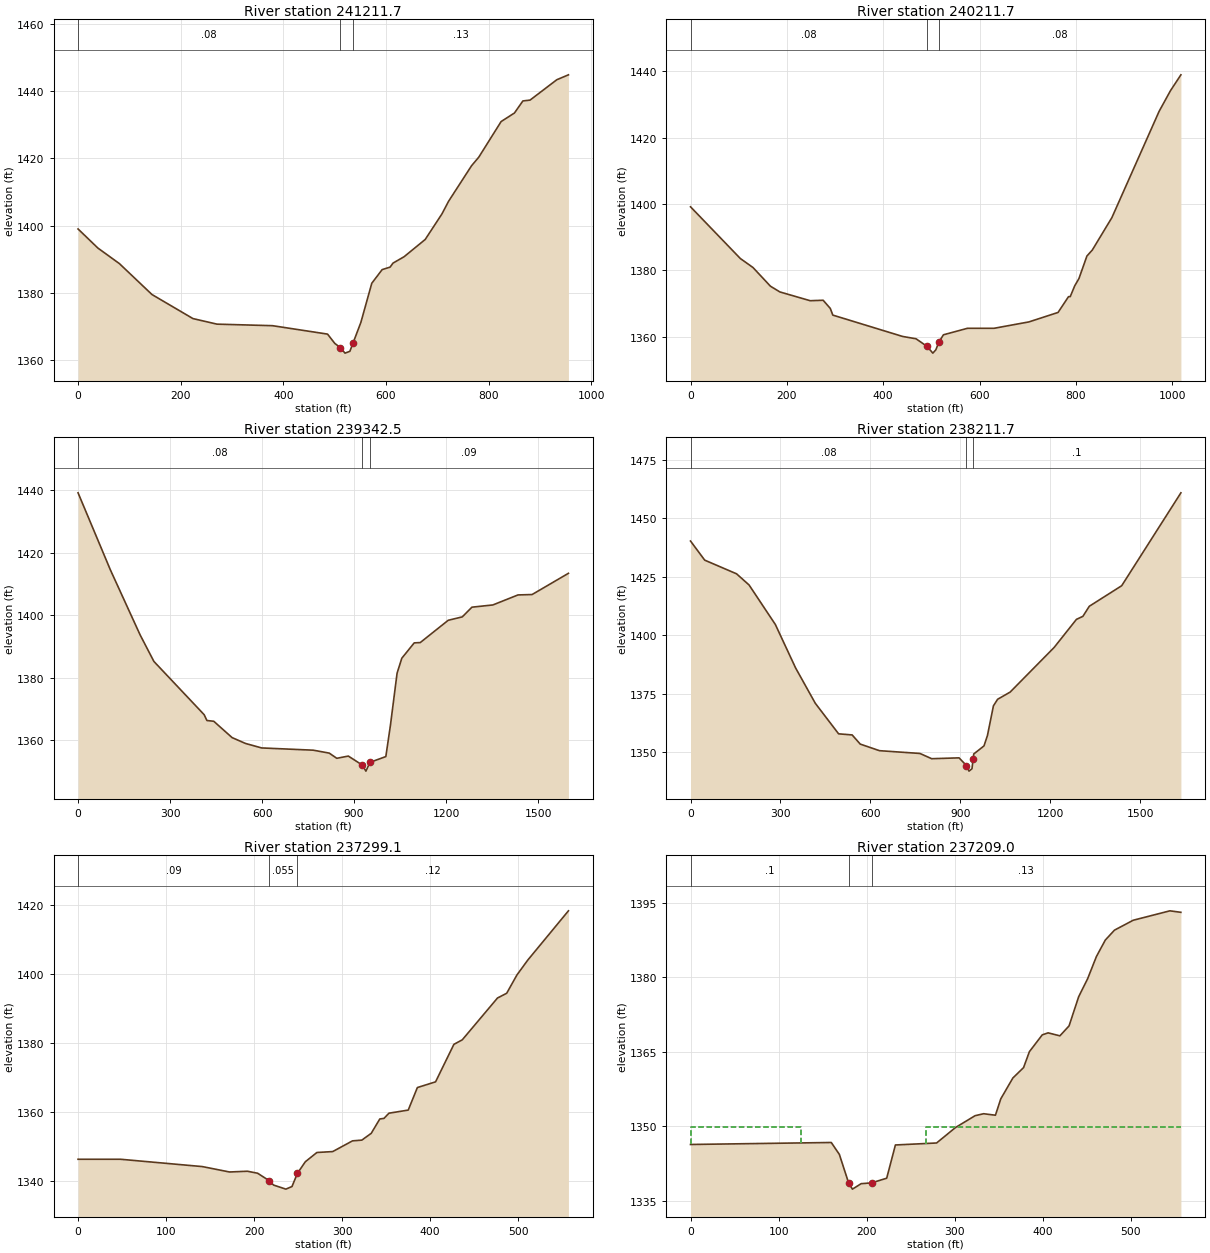
Type RM Length L Ch R = 1 ,241211.7,999.84,1000,1002.03
BEGIN DESCRIPTION:
53943.71
END DESCRIPTION:
XS GIS Cut Line= 3
  1097190.777062   689031.962781  1096824.033036   688658.414183
  1096505.167113   688366.717455
#Sta/Elev= 30
       0 1399.03   38.58 1393.37   80.66 1388.73  144.02 1379.56  223.92 1372.41
  270.73 1370.76  379.05  1370.3  486.19  1367.8  500.32 1365.04  510.97  1363.8
  520.28 1362.15  529.74 1362.69  535.98 1365.19  551.15 1371.27   572.4  1382.9
  592.61 1386.96  608.16  1387.7  613.78 1388.89  635.25 1390.77  676.52 1395.91
  709.15  1403.5  722.04 1407.25  766.93 1417.83  780.84 1420.34  824.49 1430.94
  850.36 1433.47  866.89 1437.06  880.84 1437.31  932.99 1443.36  955.65 1444.82
#Mann= 3 , 0 , 0
       0     .08       0  510.97    .055       0  535.98     .13       0
Bank Sta=510.97,535.98
Exp/Cntr=0.3,0.1

Type RM Length L Ch R = 1 ,240211.7,864.16,869.21,872.85
BEGIN DESCRIPTION:
52943.71
END DESCRIPTION:
XS GIS Cut Line= 3
  1097998.574929    688482.11715  1097645.543419   688123.828094
  1097292.600312   687748.989688
#Sta/Elev= 30
       0 1399.13  103.48 1383.52  129.54 1380.83  165.88 1375.18  185.45 1373.45
  248.39  1370.8  275.28 1370.94  290.15 1368.47  295.35 1366.46  440.23 1360.02
  468.09 1359.32  490.74 1357.05  502.99 1354.99  509.27    1356  515.72 1358.39
  524.99 1360.52  574.82 1362.48  630.06 1362.48   702.5 1364.41  762.88 1367.26
  784.54 1372.01  788.15 1372.04  797.53  1375.3   806.2 1377.48  822.79 1384.28
  834.03  1386.1  874.66 1395.88  972.76 1427.96  996.18 1434.15 1017.85 1438.94
#Mann= 3 , 0 , 0
       0     .08       0  490.74    .055       0  515.72     .08       0
Bank Sta=490.74,515.72
Exp/Cntr=0.3,0.1

Type RM Length L Ch R = 1 ,239342.5,1132.98,1130.79,1125.09
BEGIN DESCRIPTION:
52074.5
END DESCRIPTION:
XS GIS Cut Line= 3
  1098657.032032   688183.435578  1098033.520959   687319.634708
  1097500.460082   687342.562069
#Sta/Elev= 30
       0 1439.08  105.25 1414.49  202.12 1393.73  247.23 1385.21  411.26 1368.17
  420.13 1366.32  442.38 1366.09  502.14 1360.87  545.97 1358.99  598.65 1357.56
  767.01 1356.84  818.91 1355.91   843.6 1354.25  881.17 1354.96  925.86 1352.15
  938.59 1350.15  951.66 1352.95 1003.51  1354.8 1018.29 1364.65 1040.22 1381.46
 1055.63 1386.23 1096.08 1391.13 1115.71 1391.23  1206.9 1398.35 1252.75 1399.44
 1284.28 1402.54 1352.46 1403.25 1434.37 1406.45 1480.43 1406.58 1598.88 1413.36
#Mann= 3 , 0 , 0
       0     .08       0  925.86    .055       0  951.66     .09       0
Bank Sta=925.86,951.66
Exp/Cntr=0.3,0.1

Type RM Length L Ch R = 1 ,238211.7,909.83,912.66,908.19
BEGIN DESCRIPTION:
50943.71
END DESCRIPTION:
XS GIS Cut Line= 3
  1099546.288525   687504.613852  1098922.199451   686817.021389
  1098431.038128   686308.936266
#Sta/Elev= 30
       0 1440.19   47.33 1432.02  153.46 1426.18  195.21 1421.42  282.93 1404.51
  350.17 1386.01  415.98 1370.87  493.82 1357.79  538.97 1357.32  566.04  1353.4
  630.16 1350.59  765.04  1349.4  804.18 1347.16   895.5 1347.52  920.03 1344.25
  928.59 1341.85  938.58 1342.87  942.24 1346.82  944.57 1349.19  978.68 1352.63
  990.14 1357.06 1010.14 1369.75 1023.91 1372.54 1065.86 1375.63  1212.6 1394.71
 1286.91 1406.71 1308.43    1408 1329.88 1412.31 1437.94  1421.1 1635.26 1460.79
#Mann= 3 , 0 , 0
       0     .08       0  920.03    .055       0  942.24      .1       0
Bank Sta=920.03,942.24
Exp/Cntr=0.3,0.1

Type RM Length L Ch R = 1 ,237299.1,47.2,90.11,123.49
BEGIN DESCRIPTION:
50031.05
END DESCRIPTION:
XS GIS Cut Line= 4
  1099430.111187   686331.757009  1099393.692453   686157.467456
  1099305.247028   686063.819304  1099125.754748   685889.529706
#Sta/Elev= 30
       0 1346.24   48.26 1346.24  141.19 1344.11  172.08 1342.54  192.33 1342.76
  203.97 1342.18  217.04 1340.03  222.08 1338.74  236.08 1337.56     243 1338.31
  249.23 1342.17  258.15 1345.51  271.33 1348.21  289.26 1348.47   311.8 1351.59
  322.36  1351.8  333.05 1353.78  342.77 1357.95  347.54 1358.12  353.18 1359.63
  375.07 1360.53  385.46 1367.08  406.12 1368.74  426.92 1379.63   436.5 1380.96
  476.46  1393.1  486.92 1394.49   498.5 1399.78  510.85 1404.12  557.05 1418.44
#Mann= 3 , 0 , 0
       0     .09       0  217.04    .055       0  249.23     .12       0
Bank Sta=217.04,249.23
Exp/Cntr=0.5,0.3

Type RM Length L Ch R = 1 ,237209.0,115.53,96.02,84.96
BEGIN DESCRIPTION:
49940.94  Upstream xs of Bridge 37111-0362
END DESCRIPTION:
XS GIS Cut Line= 4
   1099437.91521   686352.567739  1099403.673035    686124.21345
  1099403.673035   685990.773799  1099296.188868   685581.566165
#Sta/Elev= 30
       0  1346.3 159.806  1346.7 168.999  1344.3 179.605  1338.5 183.848  1337.3
 193.747  1338.4  205.571338.559 222.739  1339.5 232.638  1346.2 279.378  1346.6
 300.733  1349.7 323.077  1352.1 332.764  1352.5 346.199  1352.2 352.281  1355.5
 365.998  1359.7 378.161  1361.8 384.737    1365 399.374  1368.4 406.021  1368.8
 419.385  1368.2 429.779  1370.2  440.74  1376.1 450.851  1379.7 460.892  1384.2
 470.933  1387.5 481.328  1389.5 502.611  1391.5 544.331  1393.4 556.776  1393.1
#Mann= 3 , 0 , 0
       0      .1       0 179.605    .055       0  205.57     .13       0
#XS Ineff= 2 , 0
       0 125.511  1349.9 266.933       0  1349.9
Permanent Ineff=
       F       F
Bank Sta=179.605,205.57
Skew Angle= 45
Exp/Cntr=0.5,0.3

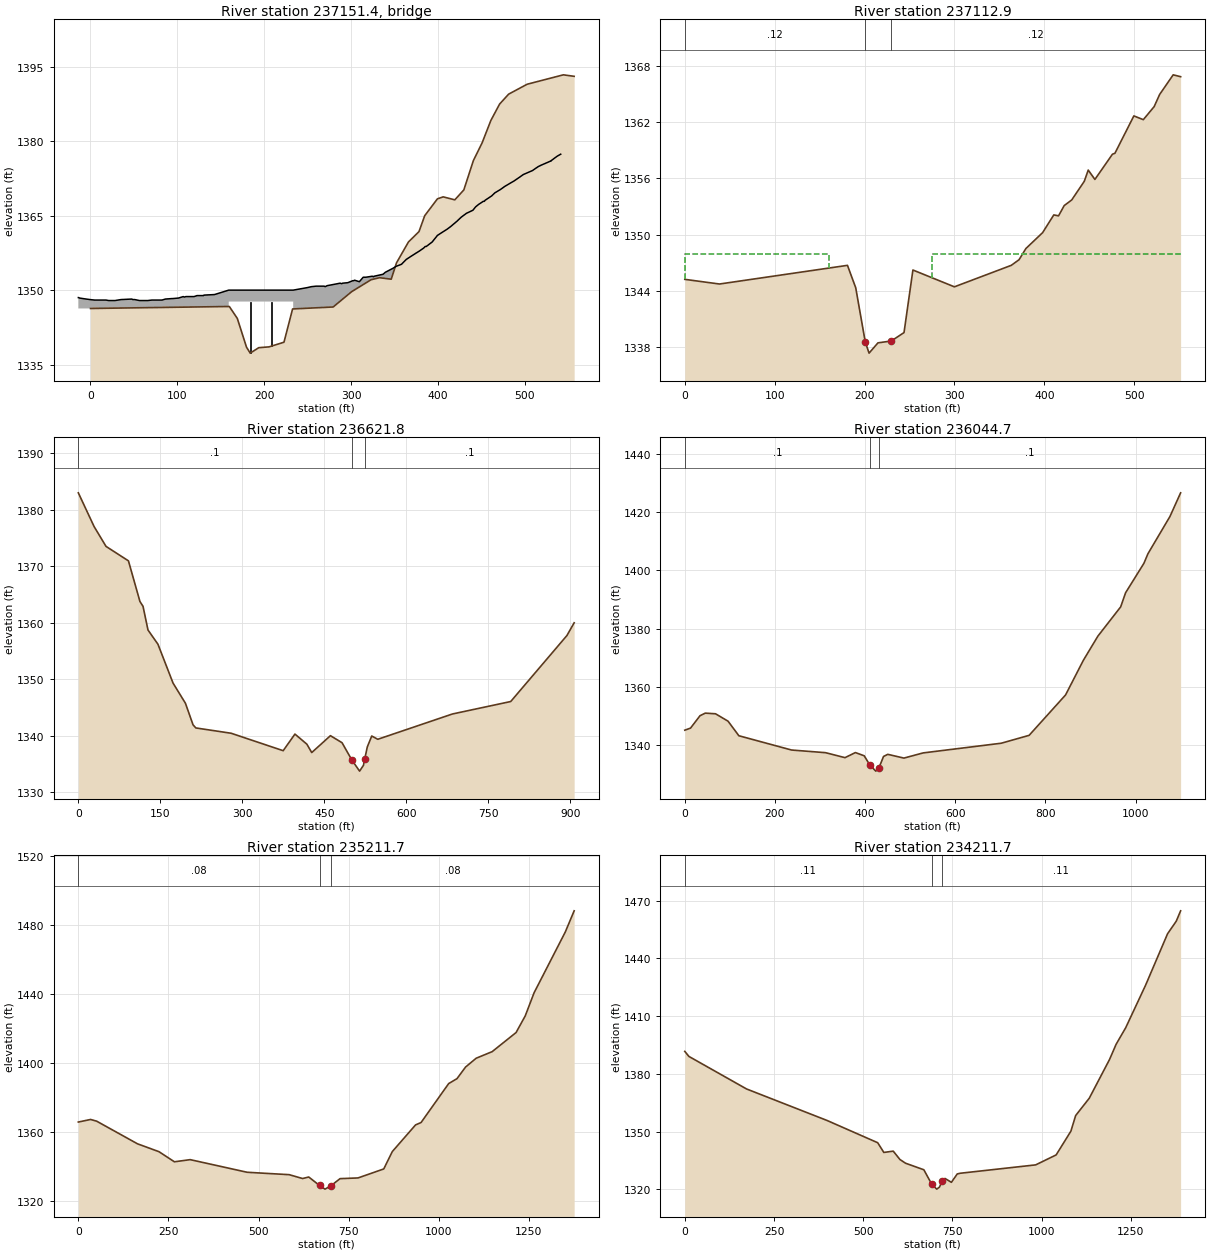
Type RM Length L Ch R = 3 ,237151.4,,,
BEGIN DESCRIPTION:
49883.41  Bridge : 37111-0362
END DESCRIPTION:
Bridge Culvert--1,0,-1,-1, 0
Deck Dist Width WeirC Skew NumUp NumDn MinLoCord MaxHiCord MaxSubmerge Is_Ogee
47.5,20,2.6,45, 112, 113, , , 0.95, 0, 0,0,,
 -14.001 -13.647 -12.516  -4.879   -.707   4.667  10.677  13.647  17.748  21.001
  23.335  28.214  35.214  35.709  47.588  48.578  50.912  56.427  58.831  65.832
  70.781  76.297  82.378  86.196  93.762  94.399  94.752 101.187 106.773 107.975
 109.814 115.329 119.218 122.683 130.037 130.673 130.956 142.058 142.341 142.623
 159.099 159.099 233.345 233.345 249.326 254.346 259.862 266.791 268.913 270.185
 272.448 281.428 287.368 289.207 290.267 296.207 301.935 302.854 304.056 309.501
 313.955 316.996 324.279 325.906 326.542 336.795 339.411 348.179 351.856 357.937
 363.594 368.827  375.12 378.797 383.676 385.373 386.575 393.293 398.808 399.162
 402.627 410.688 414.506 421.931 426.739 432.891 432.961 432.961 440.174 443.427
 446.962 452.195 453.397 454.175 461.882 465.418 472.064 476.802  483.59  487.55
 494.197 498.227 506.147 508.763  515.41 518.946 522.905 529.482 530.047  530.33
  537.26  541.29
  1348.5  1348.5  1348.4  1348.2  1348.1    1348    1348    1348    1348  1347.9
  1347.9  1347.9  1348.1  1348.1  1348.2  1348.1  1348.1  1347.9  1347.9  1347.9
    1348    1348    1348  1348.2  1348.3  1348.3  1348.3  1348.4  1348.7  1348.6
  1348.7  1348.7  1348.7  1348.9  1348.9    1349    1349  1349.1  1349.1  1349.1
    1350    1350    1350    1350  1350.5  1350.7  1350.8  1350.8  1350.8  1350.7
  1350.9  1351.2  1351.4  1351.3  1351.4  1351.5  1351.9  1351.9    1352  1351.7
  1352.6  1352.6  1352.8  1352.7  1352.8  1353.2  1353.6  1354.4  1354.8  1355.2
  1356.2  1356.8  1357.5  1357.9  1358.5  1358.8  1358.8  1359.7  1360.9    1361
  1361.4  1362.3  1362.8  1363.9  1364.7  1365.5  1365.5  1365.5  1366.1  1366.8
  1367.3  1367.9  1367.9  1368.1    1369  1369.6  1370.3  1370.9  1371.6    1372
  1372.8  1373.3  1373.9  1374.1  1374.9  1375.2  1375.5    1376    1376  1376.1
    1377  1377.4
                                                                                
                                                                                
                                                                                
                                                                                
          1347.7  1347.7
                                                                                
                                                                                
                                                                                
                                                                                
                                                                                
                                                                                
                
       0   5.445   5.798    6.93  14.637  18.738  24.112  30.123  33.093  37.194
  40.447   42.78  47.659  54.659  55.154  67.034  68.024  70.357  75.873  78.277
  85.277  90.227  95.742 101.823 105.642 113.208 113.844 114.198 120.632 126.219
 127.421 129.259 134.775 138.664 142.128 149.482 150.119 150.402 161.503 161.786
 162.069 180.312 180.312 254.558 254.558 268.771 273.792 279.307 286.237 288.358
 289.631 291.894 300.874 306.814 308.652 309.713 315.652  321.38 322.299 323.501
 328.946 333.401 336.441 343.725 345.351 345.987  356.24 358.857 367.625 371.302
 377.383  383.04 388.272 394.566 398.243 403.122 404.819 406.021 412.738 418.254
 418.607 422.072 430.133 433.951 441.376 446.184 452.336 452.407 452.407 459.619
 462.872 466.408  471.64 472.842  473.62 481.328 484.863  491.51 496.248 503.036
 506.996 513.642 517.673 525.592 528.209 534.856 538.391 542.351 548.927 549.493
 549.776 556.705 560.736
  1348.5  1348.5  1348.5  1348.4  1348.2  1348.1    1348    1348    1348    1348
  1347.9  1347.9  1347.9  1348.1  1348.1  1348.2  1348.1  1348.1  1347.9  1347.9
  1347.9    1348    1348    1348  1348.2  1348.3  1348.3  1348.3  1348.4  1348.7
  1348.6  1348.7  1348.7  1348.7  1348.9  1348.9    1349    1349  1349.1  1349.1
  1349.1    1350    1350    1350    1350  1350.5  1350.7  1350.8  1350.8  1350.8
  1350.7  1350.9  1351.2  1351.4  1351.3  1351.4  1351.5  1351.9  1351.9    1352
  1351.7  1352.6  1352.6  1352.8  1352.7  1352.8  1353.2  1353.6  1354.4  1354.8
  1355.2  1356.2  1356.8  1357.5  1357.9  1358.5  1358.8  1358.8  1359.7  1360.9
    1361  1361.4  1362.3  1362.8  1363.9  1364.7  1365.5  1365.5  1365.5  1366.1
  1366.8  1367.3  1367.9  1367.9  1368.1    1369  1369.6  1370.3  1370.9  1371.6
    1372  1372.8  1373.3  1373.9  1374.1  1374.9  1375.2  1375.5    1376    1376
  1376.1    1377  1377.4
                                                                                
                                                                                
                                                                                
                                                                                
                  1347.7  1347.7
                                                                                
                                                                                
                                                                                
                                                                                
                                                                                
                                                                                
                        
Pier Skew= 45
Pier Skew, UpSta & Num, DnSta & Num=  ,183.848, 2 ,205.061, 2 , 0 , 0 , 0 ,,
       1       1
  1336.3  1348.2
       1       1
  1336.3  1348.2
Pier Skew, UpSta & Num, DnSta & Num=  ,208.596, 2 ,229.81, 2 , 0 , 0 , 0 ,,
       1       1
  1337.6  1348.2
       1       1
  1337.6  1348.2
BR Coef=-1 , 1 , 0 ,, 0 ,,,0.8,0,1.2,0,
WSPro=,,,, 1 ,,,, 0 ,,,, 0 ,,,,-1 ,-1 ,-1 , 0 , 0 , 0 , 0 , 0
BC Design=,, 0 ,, 0 ,,,,,,

Type RM Length L Ch R = 1 ,237112.9,518.02,491.1,462.75
BEGIN DESCRIPTION:
49844.93  Down stream xs of Bridge 37111-0362
END DESCRIPTION:
XS GIS Cut Line= 5
  1099554.975389   686323.953029  1099503.682272    686110.60231
  1099482.609174   686065.011335  1099481.669471   685949.426303
  1099440.772479   685556.542077
#Sta/Elev= 30
       0  1345.2  38.608  1344.7 181.019  1346.7 190.212  1344.3 200.818  1338.5
 205.061  1337.3  214.96  1338.4  229.81  1338.6 243.952  1339.5 253.851  1346.2
 300.025  1344.4 363.311  1346.7 371.938  1347.3 379.575  1348.5 398.172  1350.2
 410.617  1352.1  415.92    1352 422.213  1353.1 430.557  1353.7 444.558  1355.7
 448.942  1356.9 456.367  1355.9 475.883  1358.6 478.641  1358.7 499.712  1362.7
 510.248  1362.3  522.34  1363.7 528.421    1365 543.482  1367.1 551.755  1366.9
#Mann= 3 , 0 , 0
       0     .12       0 200.818    .054       0  229.81     .12       0
#XS Ineff= 2 , 0
       0  160.16  1347.9 274.711       0  1347.9
Permanent Ineff=
       F       F
Bank Sta=200.818,229.81
Skew Angle= 45
Exp/Cntr=0.5,0.3

Type RM Length L Ch R = 1 ,236621.8,575,577.12,580
BEGIN DESCRIPTION:
49353.83
END DESCRIPTION:
XS GIS Cut Line= 2
  1100246.931052   686084.629989  1099536.766045   685520.139825
#Sta/Elev= 30
       0 1383.01   28.82 1377.04   50.68 1373.52   91.67 1370.96  112.72 1363.76
   118.4  1362.9  127.45 1358.71  145.67 1356.19  173.32  1349.3  195.98 1345.73
   209.9 1341.91     215 1341.36   279.6 1340.42   374.8 1337.33  396.32 1340.27
  418.09 1338.49  427.03    1337  461.26 1339.99  482.53 1338.74  500.45 1335.68
  514.59 1333.71  521.65 1334.73  523.98 1335.84   528.7 1337.99  536.84 1339.93
  547.87 1339.35   684.4 1343.83  791.11 1346.04  893.93 1357.73  907.18 1359.99
#Mann= 3 , 0 , 0
       0      .1       0  500.45    .054       0  523.98      .1       0
Bank Sta=500.45,523.98
Exp/Cntr=0.3,0.1

Type RM Length L Ch R = 1 ,236044.7,826.44,833,816.06
BEGIN DESCRIPTION:
48776.71
END DESCRIPTION:
XS GIS Cut Line= 4
  1100439.071359   685743.424704  1100172.011118   685485.417337
  1100140.325994   685394.888423  1099607.382484   685054.067361
#Sta/Elev= 30
       0  1345.1   12.77 1345.82   33.84 1350.09   45.48 1350.96   68.11 1350.74
   95.94  1348.2  119.94 1343.19  236.95 1338.28  312.22 1337.37  355.33 1335.66
  378.43 1337.41     398  1336.3  410.58  1333.1  423.76 1331.03  430.44 1332.07
  440.86 1336.08  450.22  1336.8  486.09 1335.51   528.7 1337.29  701.96 1340.62
  763.81 1343.33  844.62 1357.21  884.11 1369.12  916.35 1377.43  966.85 1387.48
   977.8 1392.34 1018.37 1402.44  1027.4 1405.75 1076.15 1418.54 1099.85 1426.68
#Mann= 3 , 0 , 0
       0      .1       0  410.58    .054       0  430.44      .1       0
Bank Sta=410.58,430.44
Exp/Cntr=0.3,0.1

Type RM Length L Ch R = 1 ,235211.7,999.54,1000,1001.38
BEGIN DESCRIPTION:
47943.71
END DESCRIPTION:
XS GIS Cut Line= 3
  1100969.740577   685565.373763  1100647.099584   684961.755175
  1100272.995908   684380.362579
#Sta/Elev= 30
       0 1365.65   34.05 1367.14   50.79 1366.16   164.1 1353.01   223.7 1348.44
   266.6 1342.56  310.36 1343.81  468.43 1336.48  585.08 1335.08  622.43 1332.84
  639.29 1333.73  669.27 1328.82  684.44 1326.69  700.15 1328.52  726.18 1332.77
  776.09 1333.19  847.45 1338.41  871.21  1348.5  935.72 1363.98  950.98 1365.36
 1027.66 1387.99 1050.72 1390.85 1074.46 1397.57 1103.95 1402.71 1148.25 1406.52
 1214.62 1417.62 1240.03 1427.27 1264.68 1440.74 1351.19 1476.01 1375.79  1488.3
#Mann= 3 , 0 , 0
       0     .08       0  669.27    .054       0  700.15     .08       0
Bank Sta=669.27,700.15
Exp/Cntr=0.3,0.1

Type RM Length L Ch R = 1 ,234211.7,1190.86,1183.95,1172.4
BEGIN DESCRIPTION:
46943.71
END DESCRIPTION:
XS GIS Cut Line= 3
  1101827.454636   685053.127481  1101443.765397   684460.457919
  1101130.805168   683852.960664
#Sta/Elev= 30
       0 1391.68    11.6 1389.06  173.05 1372.16  398.26 1355.82  540.55 1344.23
  557.78 1339.18  584.11 1339.86  602.87 1335.51  618.63 1333.58  669.84 1330.18
  692.34 1322.56  706.03 1320.12  713.53 1321.15  721.04 1324.17  729.07 1325.67
   747.1 1323.66  763.39    1328  771.51 1328.36  983.13 1332.71 1040.58 1337.89
 1081.94 1350.24 1095.24 1358.34 1133.36 1367.34 1190.17 1387.46  1208.7 1395.39
 1235.57    1404 1291.17 1426.04 1352.85 1452.81 1377.07 1459.29  1389.4 1464.71
#Mann= 3 , 0 , 0
       0     .11       0  692.34    .054       0  721.04     .11       0
Bank Sta=692.34,721.04
Exp/Cntr=0.3,0.1

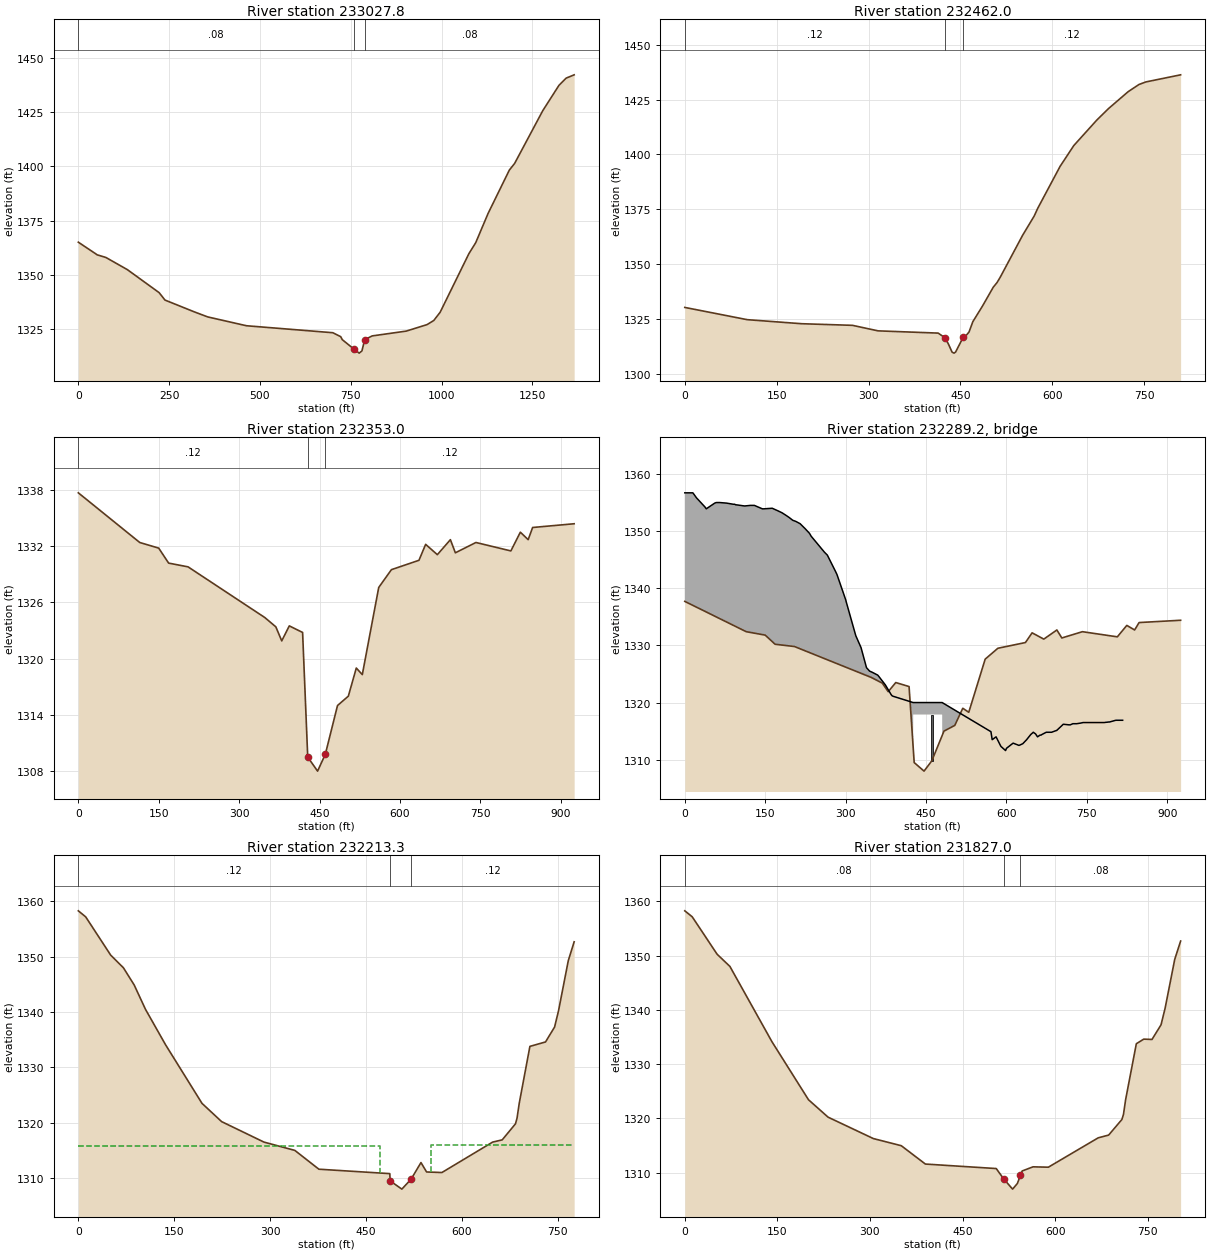
Type RM Length L Ch R = 1 ,233027.8,540.27,565.74,588.99
BEGIN DESCRIPTION:
45759.76
END DESCRIPTION:
XS GIS Cut Line= 3
  1102778.303437   684132.867728   1102262.84094    683685.22504
  1101757.695181   683226.326533
#Sta/Elev= 30
       0 1365.07   52.12 1359.23   75.92 1358.03  135.12 1352.41  222.53 1341.81
  238.56  1338.4   320.3  1332.9  356.22 1330.64  462.77 1326.57  700.81 1323.35
  722.45 1321.53  726.73 1320.16  757.96 1315.93   773.2 1313.95  780.81 1314.96
  788.45 1320.15  809.06 1321.88  902.85  1324.1  960.13 1327.09  978.77 1329.01
  996.17 1332.78 1075.43  1359.8 1094.13 1364.84 1128.35 1378.37  1186.7 1398.29
 1201.23 1401.35 1278.88 1425.71  1323.4 1437.36 1343.06 1440.66 1365.17 1442.19
#Mann= 3 , 0 , 0
       0     .08       0  757.96    .054       0  788.45     .08       0
Bank Sta=757.96,788.45
Exp/Cntr=0.3,0.1

Type RM Length L Ch R = 1 ,232462.0,95.43,109.05,123.41
BEGIN DESCRIPTION:
45194.02
END DESCRIPTION:
XS GIS Cut Line= 4
  1102705.795909   683604.583195  1102500.012921   683279.831925
  1102493.582179   683160.863643  1102239.568804   682990.449558
#Sta/Elev= 30
       0 1330.43  101.92 1324.86  190.63 1323.02   273.8 1322.28  315.51 1319.77
  413.64 1318.75  424.28 1316.73  430.03 1313.98  436.41 1310.07  439.64 1309.64
  442.12 1310.15  454.32 1316.76  456.77 1316.83  464.03 1319.25  470.29 1323.96
  486.08 1331.08   503.6 1339.63  509.66  1341.7  515.07 1344.22  551.45 1363.21
  570.45 1372.02  576.34 1375.59  612.74 1394.61   635.1 1404.07  672.66 1415.66
  692.08 1420.97  723.79 1428.56  741.55 1431.85  752.78 1433.01  809.48 1436.24
#Mann= 3 , 0 , 0
       0     .12       0  424.28    .054       0  454.32     .12       0
Bank Sta=424.28,454.32
Exp/Cntr=0.5,0.3

Type RM Length L Ch R = 1 ,232353.0,127.72,139.65,153.05
BEGIN DESCRIPTION:
45084.97
END DESCRIPTION:
XS GIS Cut Line= 6
  1102725.886969   683613.870806  1102658.208649   683424.371511
  1102588.993523   683234.551164  1102608.122757    683147.34446
  1102270.273312   682894.051156 1102236.1087508  682868.4372184
#Sta/Elev= 30
       0  1337.7 114.559  1332.4 149.912  1331.8 168.457  1330.2  204.68  1329.8
 347.637  1324.4 368.404  1323.4 379.416  1321.9 393.518  1323.5 418.342  1322.8
 427.905  1309.5 446.258    1308 460.747  1309.8 483.446    1315 503.634    1316
 518.509    1319 529.714  1318.3 560.334  1327.6 583.999  1329.5 635.386  1330.5
 647.846  1332.2 669.676  1331.1 694.018  1332.7 703.291  1331.3 741.638  1332.4
 806.838  1331.5 824.514  1333.5   839.1  1332.7 847.407    1334 924.874  1334.4
#Mann= 3 , 0 , 0
       0     .12       0 427.905    .054       0 460.747     .12       0
#XS Ineff= 2 , 0
           404.6 1316.89  521.48         1317.12
Permanent Ineff=
       F       F
Bank Sta=427.905,460.747
Skew Angle= 15
Exp/Cntr=0.5,0.3

Type RM Length L Ch R = 3 ,232289.2,,,
BEGIN DESCRIPTION:
45021.22  Bridge: 37111-0363
END DESCRIPTION:
Bridge Culvert--1,0,-1,-1, 0
Deck Dist Width WeirC Skew NumUp NumDn MinLoCord MaxHiCord MaxSubmerge Is_Ogee
60,20,2.6,15, 97, 97, , , 0.95, 0, 0,0,,
       0  15.068  22.023  37.864  39.989  55.831  58.632    65.2   77.95  90.604
  93.115  95.047  96.303 111.468  122.19  129.82 144.696 146.434 147.304 163.048
 174.929 181.497 188.162 194.441 201.299 207.094 215.112 224.771 232.692 235.783
 260.607 265.919 281.374 283.886 297.892 300.403 300.886 318.949 328.801 338.943
 344.739 349.569 359.904 362.512 374.007 384.825 386.467 388.592 425.973 425.973
 480.065 480.065 571.055 573.374 580.618 589.215 589.987 591.147 598.294  600.13
 612.397 623.312  625.92  630.46 637.608 645.238 650.068 654.415 657.892 662.625
 664.364 665.909 674.216 683.875 684.069 684.165 692.762 693.535 705.995 716.524
 719.132 723.961 731.399 737.967  742.99 748.496 752.456 757.865 760.763 762.598
 771.485  778.44  782.11 791.093 792.349  803.94 816.787
  1356.7  1356.7  1355.8  1354.2  1353.9  1354.9    1355    1355  1354.9  1354.7
  1354.7  1354.6  1354.6  1354.4  1354.5  1354.5  1353.9  1353.9  1353.9    1354
  1353.5  1353.2  1352.8  1352.4  1351.9  1351.7  1351.3  1350.4  1349.6  1349.1
  1346.3  1345.8  1342.9  1342.4  1338.6  1337.9  1337.7  1331.7  1329.6  1326.1
  1325.5  1325.3  1324.8  1324.5  1323.1  1321.4  1321.2  1321.1    1320    1320
    1320    1320  1314.9  1313.5    1314  1312.4  1312.3  1312.2  1311.6    1312
  1312.9  1312.5  1312.6  1312.8  1313.5  1314.4  1314.8  1314.5    1314  1314.3
  1314.3  1314.4  1314.8  1314.8  1314.8  1314.8  1315.1  1315.1  1316.2  1316.1
  1316.1  1316.3  1316.3  1316.4  1316.5  1316.5  1316.5  1316.5  1316.5  1316.5
  1316.5  1316.5  1316.5  1316.6  1316.6  1316.9  1316.9
                                                                                
                                                                                
                                                                                
                                                                                
                                                                          1317.9
  1317.9
                                                                                
                                                                                
                                                                                
                                                        
       0  75.052  82.104  97.945  99.973 115.911 118.712 125.281 138.031 150.684
 153.196 155.031 156.383 171.548 182.174 189.804  204.68 206.418 207.288 223.129
 234.913 241.481 248.243 254.521  261.38 267.078 275.096 284.755 292.772 295.767
 320.687 325.903 341.358  343.87 357.972 360.387  360.87 379.029 388.882 398.927
 404.723 409.553 419.888 422.496 434.087 444.905 446.451 448.576 486.054 486.054
 540.146 540.146 631.039 633.454 640.699 649.199 649.971 651.131 658.375  660.21
 672.478 683.296 686.001  690.54 697.592 705.319 710.052 714.399 717.876 722.609
 724.444 725.893   734.2 743.956 744.053 744.246 752.746 753.615 766.076 776.604
 779.212 784.042 791.383 798.048 802.974 808.576  812.44 817.946 820.747 822.582
 831.566  838.52 842.191 851.174 852.333 863.924 876.867
  1356.7  1356.7  1355.8  1354.2  1353.9  1354.9    1355    1355  1354.9  1354.7
  1354.7  1354.6  1354.6  1354.4  1354.5  1354.5  1353.9  1353.9  1353.9    1354
  1353.5  1353.2  1352.8  1352.4  1351.9  1351.7  1351.3  1350.4  1349.6  1349.1
  1346.3  1345.8  1342.9  1342.4  1338.6  1337.9  1337.7  1331.7  1329.6  1326.1
  1325.5  1325.3  1324.8  1324.5  1323.1  1321.4  1321.2  1321.1    1320    1320
    1320    1320  1314.9  1313.5    1314  1312.4  1312.3  1312.2  1311.6    1312
  1312.9  1312.5  1312.6  1312.8  1313.5  1314.4  1314.8  1314.5    1314  1314.3
  1314.3  1314.4  1314.8  1314.8  1314.8  1314.8  1315.1  1315.1  1316.2  1316.1
  1316.1  1316.3  1316.3  1316.4  1316.5  1316.5  1316.5  1316.5  1316.5  1316.5
  1316.5  1316.5  1316.5  1316.6  1316.6  1316.9  1316.9
                                                                                
                                                                                
                                                                                
                                                                                
                                                                          1317.9
  1317.9
                                                                                
                                                                                
                                                                                
                                                        
Pier Skew= 15
Pier Skew, UpSta & Num, DnSta & Num=  ,460.747, 2 ,520.827, 2 , 0 , 0 , 0 ,,
       3       3
    1308  1317.9
       3       3
    1308  1317.9
BR Coef=-1 , 1 , 0 ,, 0 ,,,0.8,0,2,0,
WSPro=,,,, 1 ,,,, 0 ,,,, 0 ,,,,-1 ,-1 ,-1 , 0 , 0 , 0 , 0 , 0
BC Design=,, 0 ,, 0 ,,,,,,

Type RM Length L Ch R = 1 ,232213.3,434.08,386.36,335.83
BEGIN DESCRIPTION:
44945.32
END DESCRIPTION:
XS GIS Cut Line= 4
   1102863.34851   683492.045655  1102686.371432    683194.35434
   1102717.13991   683058.093849  1102817.345927  682756.9463017
#Sta/Elev= 30
       0  1358.3  11.591  1357.2  50.615  1350.3  70.609    1348  87.416  1344.9
 105.093  1340.5 136.485  1334.1 193.572  1323.5 224.288  1320.2  290.55  1316.5
 338.847    1315 376.518  1311.6 487.503  1310.8 487.986  1309.5 506.338    1308
 520.827  1309.8 536.282  1312.8 545.072  1311.1 569.027    1311 648.426  1316.5
 663.398  1316.9 684.165  1319.8  686.58  1320.8 690.057  1323.5 706.768  1333.8
 731.206  1334.6 745.405  1337.3 751.683  1340.3 766.849  1349.3 776.025  1352.7
#Mann= 3 , 0 , 0
       0     .12       0 487.986    .053       0 520.827     .12       0
#XS Ineff= 2 , 0
          472.33 1315.87  552.25         1315.97
Permanent Ineff=
       F       F
Bank Sta=487.986,520.827
Skew Angle= 15
Exp/Cntr=0.5,0.3

Type RM Length L Ch R = 1 ,231827.0,604.47,615.25,620.62
BEGIN DESCRIPTION:
44558.96
END DESCRIPTION:
XS GIS Cut Line= 2
  1103324.593186   683180.190075  1102746.114411   682622.670717
#Sta/Elev= 30
       0 1358.26   12.01 1357.16   52.39 1350.26   73.07 1348.02  141.29 1334.13
  200.44 1323.45  232.17 1320.24  305.44  1316.3  350.79 1314.98  389.83  1311.6
  504.65 1310.77  516.45 1308.91  531.16 1306.98  538.87 1308.02  543.89 1309.52
  546.59 1310.32  564.28 1311.09   589.1 1311.02  669.83 1316.43  686.81 1316.94
  708.26 1319.81  710.81 1320.75  714.38 1323.52  731.65 1333.77  743.69 1334.62
  757.03 1334.56  771.68 1337.26  778.22 1340.28  793.87 1349.32  803.41 1352.69
#Mann= 3 , 0 , 0
       0     .08       0  516.45    .053       0  543.89     .08       0
Bank Sta=516.45,543.89
Exp/Cntr=0.3,0.1