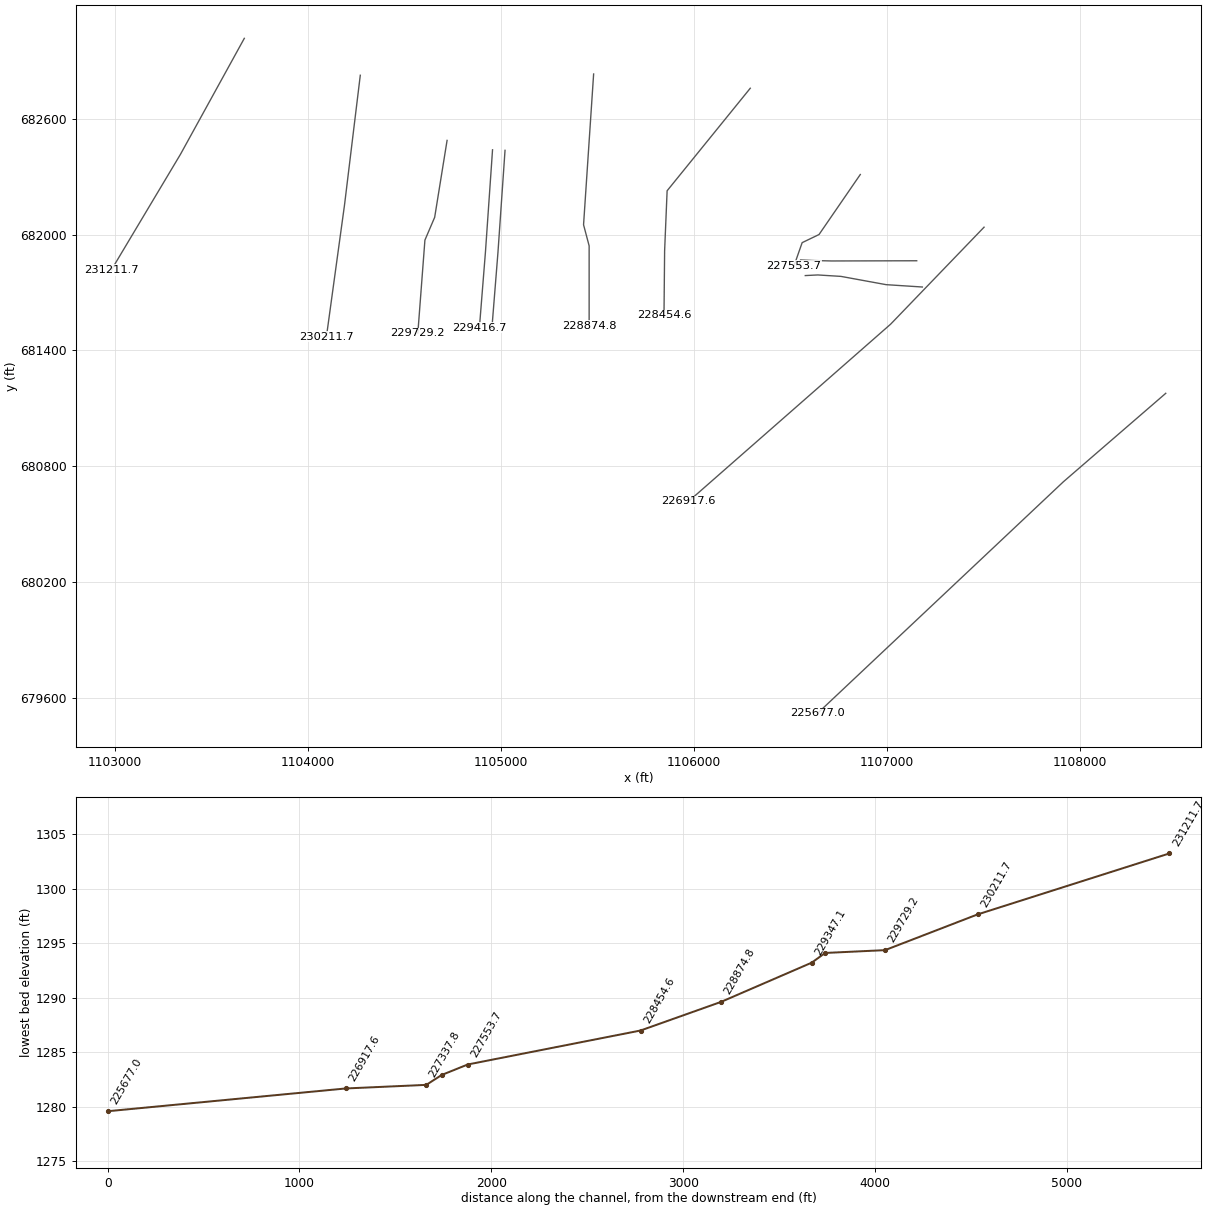
HEC-RAS study 2ndBroadRv.prj: 2ndBroadRv

--- 2ndBroadRv.g01 (geometry) --- (continued)

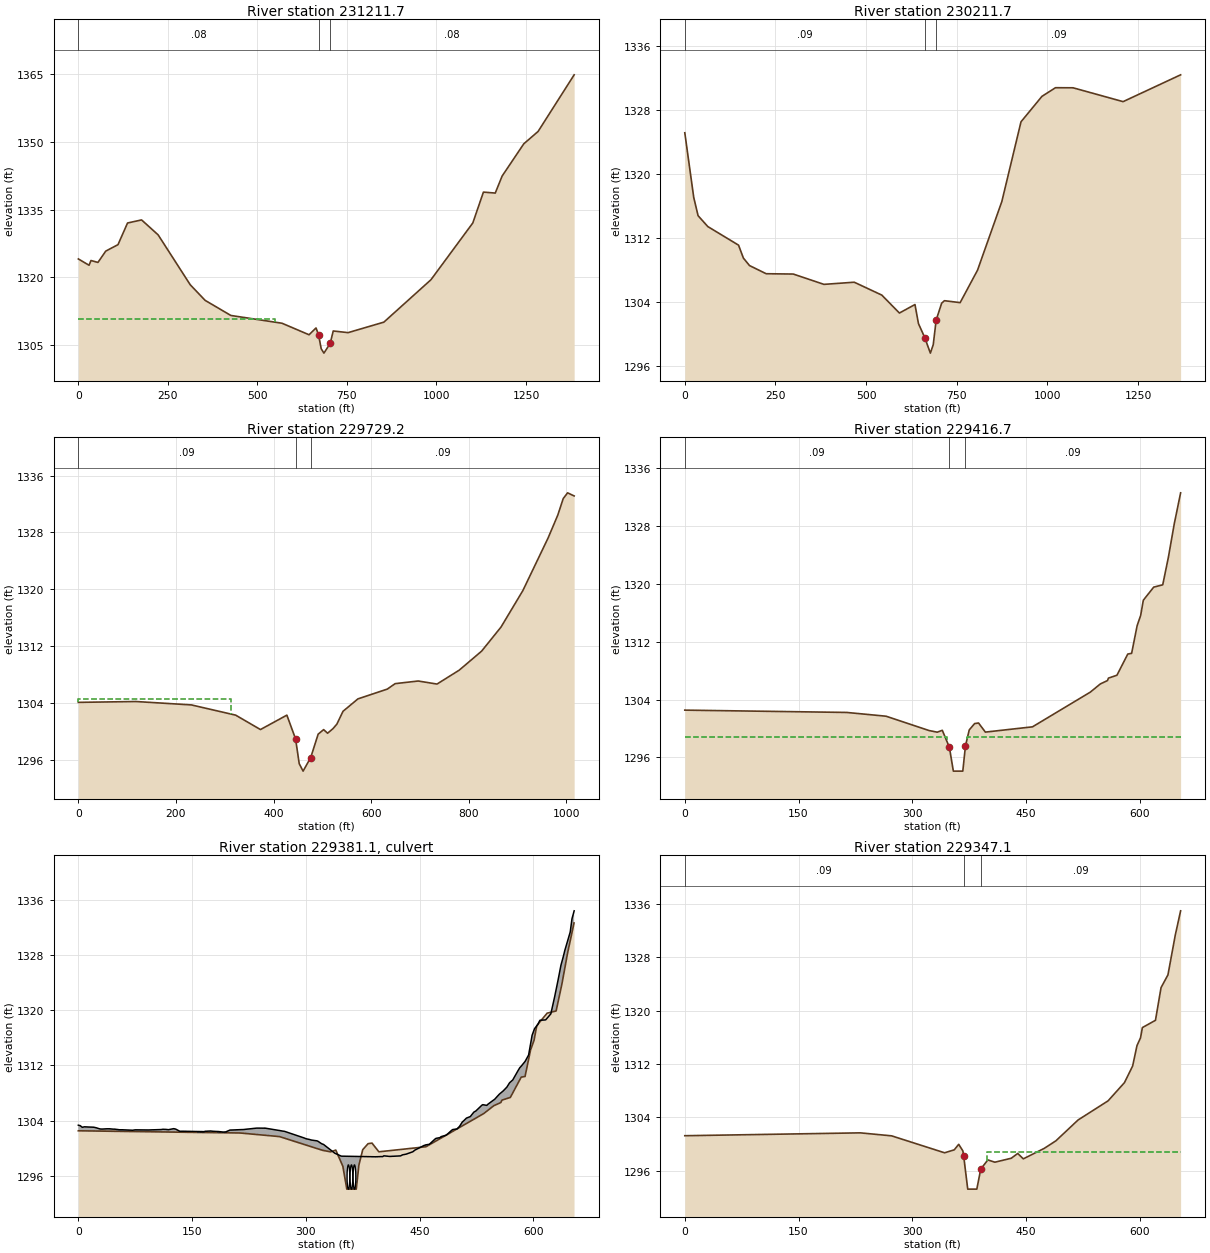
Type RM Length L Ch R = 1 ,231211.7,978.98,1000,1006.45
BEGIN DESCRIPTION:
43943.71
END DESCRIPTION:
XS GIS Cut Line= 3
  1103670.840605   683017.846204  1103340.092128   682417.061605
  1102981.714446   681817.225639
#Sta/Elev= 30
       0 1324.08   29.95 1322.69   35.32 1323.73    54.8 1323.31   76.51 1325.81
  110.77 1327.24   137.4 1332.03  176.64 1332.71  222.81 1329.41  312.48 1318.37
  354.04 1314.92  425.92 1311.58  568.77 1309.86  644.28 1307.31  663.74 1308.82
  670.88 1307.26  678.22 1304.21  685.81 1303.25  703.28 1305.39  711.77 1308.15
  753.22 1307.78  853.12  1310.1  984.66 1319.48 1101.57 1332.04 1131.18 1338.86
 1164.23 1338.65 1183.41 1342.41 1243.88 1349.54 1283.88 1352.28 1384.55  1364.8
#Mann= 3 , 0 , 0
       0     .08       0  670.88    .053       0  703.28     .08       0
#XS Ineff= 2 , 0
          549.37 1310.87
Permanent Ineff=
       F       F
Bank Sta=670.88,703.28
Exp/Cntr=0.3,0.1

Type RM Length L Ch R = 1 ,230211.7,490.67,482.48,473.14
BEGIN DESCRIPTION:
42943.71
END DESCRIPTION:
XS GIS Cut Line= 3
  1104271.956918   682826.500644   1104190.24583   682154.250218
  1104096.329401   681470.587332
#Sta/Elev= 30
       0 1325.18   24.66  1317.1   36.65 1314.82   63.53 1313.46  148.23 1311.14
  161.64 1309.52   178.5 1308.59   224.4 1307.57  299.08 1307.53  383.78 1306.24
  467.23 1306.51  543.31  1304.9   591.8 1302.66  634.73 1303.72  644.33 1301.34
  661.71 1299.59   677.2 1297.65  685.13 1298.71  693.13 1301.77  708.31 1303.89
  715.94  1304.2   759.3 1303.96  807.21 1308.01  874.26 1316.59   927.1 1326.55
  984.88 1329.73 1022.22 1330.81 1070.69  1330.8 1208.64 1329.07 1367.28 1332.42
#Mann= 3 , 0 , 0
       0     .09       0  661.71    .053       0  693.13     .09       0
Bank Sta=661.71,693.13
Exp/Cntr=0.3,0.1

Type RM Length L Ch R = 1 ,229729.2,302.02,312.55,322.98
BEGIN DESCRIPTION:
42461.23
END DESCRIPTION:
XS GIS Cut Line= 4
   1104721.82623   682488.853506  1104657.519033    682090.14897
  1104606.949628   681972.048824  1104570.270748   681489.983199
#Sta/Elev= 30
       0 1304.06  117.97 1304.18   231.7  1303.7  322.28 1302.26  373.12 1300.23
  427.24 1302.26  445.08 1298.91  452.54 1295.42  460.46 1294.37  476.11 1296.29
  491.34 1299.58  502.57 1300.22  510.66 1299.71  521.73 1300.36  529.74    1301
  542.23  1302.8  572.81 1304.55  632.98 1305.93  649.08  1306.7  696.33 1307.07
  734.82 1306.64  780.37  1308.6  826.22 1311.28  866.03 1314.68  910.68 1319.81
   962.5 1327.24  982.26 1330.45   993.4 1332.78 1002.35 1333.59 1015.79 1333.15
#Mann= 3 , 0 , 0
       0     .09       0  445.08    .053       0  476.11     .09       0
#XS Ineff= 2 , 0
           312.5 1304.57
Permanent Ineff=
       F       F
Bank Sta=445.08,476.11
Exp/Cntr=0.5,0.3

Type RM Length L Ch R = 1 ,229416.7,69.91,69.62,68.53
BEGIN DESCRIPTION:
42148.68
END DESCRIPTION:
XS GIS Cut Line= 3
  1104957.425243   682440.135032  1104920.753737   681911.016881
  1104889.323163    681518.13461
#Sta/Elev= 30
       0 1302.55 213.497 1302.23 265.306 1301.71 321.932 1299.73 332.835  1299.5
 339.524 1299.76 348.851 1297.41  354.09 1294.11  366.54 1294.11 370.057  1297.6
 375.042 1299.81 382.121 1300.69 387.289 1300.77 396.333 1299.51 458.474 1300.24
 534.643 1305.04 547.951 1306.18 557.299 1306.64 558.529 1306.98 569.773 1307.38
 584.063 1310.31  589.14 1310.41 596.402 1314.24 601.055 1315.66 604.562 1317.76
 618.238 1319.57 630.138 1319.89 637.641 1323.72 645.327 1328.32 653.734 1332.62
#Mann= 3 , 0 , 0
       0     .09       0 348.851    .053       0 370.057     .09       0
#XS Ineff= 2 , 0
       0 346.136 1298.79  372.27       0 1298.79
Permanent Ineff=
       F       F
Bank Sta=348.851,370.057
Skew Angle= 45
Exp/Cntr=0.5,0.3

Type RM Length L Ch R = 2 ,229381.1,,,
BEGIN DESCRIPTION:
42113.1  Culvert: 37111-0365
END DESCRIPTION:
Bridge Culvert--1,0,-1,-1, 0
Deck Dist Width WeirC Skew NumUp NumDn MinLoCord MaxHiCord MaxSubmerge Is_Ogee
25,18,2.6,45, 125, 125, 1298.79, , 0.95, 0, 0,0,,
       0   2.376   5.339    6.47   8.174  13.039  20.237  23.511  28.489  31.198
  37.717  41.295  45.884   47.85  54.207  58.004  71.496  75.074  92.631  94.936
 109.213 111.398 115.704 118.766 125.709 128.276 133.834 137.391 150.833 165.774
 167.386 174.606 177.625 182.971 185.113 190.968 194.327 200.033 201.349 203.866
 216.254 217.407 220.681 235.318 235.375 246.024 246.087 265.915 268.863 271.967
 297.657 300.322 304.622 307.528 314.627 316.218 320.864 323.466 338.188 346.235
 347.069 391.971 400.251 401.516 402.952 410.532 424.964 427.595 432.269 441.213
 443.603 456.084 457.053 457.668   462.9 470.558 471.619 477.007 478.471  484.92
 487.197 492.295 493.744 499.422 502.626 506.501 508.155 511.846  516.93 521.569
 524.263  532.14 532.925 533.031  533.47 538.674 539.989 546.707 548.955 553.353
 555.411 560.212 565.205 568.655 572.905 579.983 582.119 583.893 589.197 593.814
 598.439 601.684 605.743 608.699 615.423 616.456 623.117 628.165 632.627  636.46
   639.5 641.537 648.679 651.005  653.89
 1303.36  1303.3 1303.05 1303.09 1303.13  1303.1 1303.07 1302.99 1302.82  1302.8
 1302.84 1302.84 1302.79 1302.79  1302.7  1302.7 1302.63 1302.69 1302.67 1302.68
 1302.73 1302.77 1302.75 1302.71 1302.86  1302.8 1302.48 1302.49 1302.46 1302.43
 1302.48 1302.52 1302.48 1302.45 1302.44 1302.37 1302.39 1302.66 1302.66 1302.67
 1302.73 1302.73 1302.77 1302.94 1302.94 1302.93 1302.94 1302.58 1302.52 1302.47
 1301.52  1301.4  1301.3 1301.21  1301.1 1301.02 1300.68 1300.57 1299.31 1298.91
 1298.88 1298.79 1298.82 1298.82 1298.93 1298.84 1298.92 1299.07 1299.17 1299.52
 1299.74 1300.44 1300.43  1300.5  1300.6 1301.37 1301.45 1301.57 1301.71 1301.91
 1302.11 1302.62 1302.73 1302.82 1303.18 1303.84 1303.99 1304.39 1304.61 1305.25
 1305.42 1306.25  1306.3 1306.31 1306.33 1306.23 1306.38 1306.93  1307.1 1307.63
 1307.87 1308.31 1308.88 1309.49 1309.91 1311.28 1311.67 1311.88 1312.59 1313.52
 1316.38 1317.34 1317.89 1318.54 1318.59 1318.62 1319.47 1321.95 1324.34 1326.51
 1327.73 1328.64 1331.31 1333.22 1334.38
                                                                                
                                                                                
                                                                                
                                                                                
                                                                                
                                                                                
                                                                                
                                                                                
                                                                                
                                                                                
                                                                                
                                                                                
                                        
       0   2.376   5.339    6.47   8.174  13.039  20.237  23.511  28.489  31.198
  37.717  41.295  45.884   47.85  54.207  58.004  71.496  75.074  92.631  94.936
 109.213 111.398 115.704 118.766 125.709 128.276 133.834 137.391 150.833 165.774
 167.386 174.606 177.625 182.971 185.113 190.968 194.327 200.033 201.349 203.866
 216.254 217.407 220.681 235.318 235.375 246.024 246.087 265.915 268.863 271.967
 297.657 300.322 304.622 307.528 314.627 316.218 320.864 323.466 338.188 346.235
 347.069 391.971 400.251 401.516 402.952 410.532 424.964 427.595 432.269 441.213
 443.603 456.084 457.053 457.668   462.9 470.558 471.619 477.007 478.471  484.92
 487.197 492.295 493.744 499.422 502.626 506.501 508.155 511.846  516.93 521.569
 524.263  532.14 532.925 533.031  533.47 538.674 539.989 546.707 548.955 553.353
 555.411 560.212 565.205 568.655 572.905 579.983 582.119 583.893 589.197 593.814
 598.439 601.684 605.743 608.699 615.423 616.456 623.117 628.165 632.627  636.46
   639.5 641.537 648.679 651.005  653.89
 1303.36  1303.3 1303.05 1303.09 1303.13  1303.1 1303.07 1302.99 1302.82  1302.8
 1302.84 1302.84 1302.79 1302.79  1302.7  1302.7 1302.63 1302.69 1302.67 1302.68
 1302.73 1302.77 1302.75 1302.71 1302.86  1302.8 1302.48 1302.49 1302.46 1302.43
 1302.48 1302.52 1302.48 1302.45 1302.44 1302.37 1302.39 1302.66 1302.66 1302.67
 1302.73 1302.73 1302.77 1302.94 1302.94 1302.93 1302.94 1302.58 1302.52 1302.47
 1301.52  1301.4  1301.3 1301.21  1301.1 1301.02 1300.68 1300.57 1299.31 1298.91
 1298.88 1298.79 1298.82 1298.82 1298.93 1298.84 1298.92 1299.07 1299.17 1299.52
 1299.74 1300.44 1300.43  1300.5  1300.6 1301.37 1301.45 1301.57 1301.71 1301.91
 1302.11 1302.62 1302.73 1302.82 1303.18 1303.84 1303.99 1304.39 1304.61 1305.25
 1305.42 1306.25  1306.3 1306.31 1306.33 1306.23 1306.38 1306.93  1307.1 1307.63
 1307.87 1308.31 1308.88 1309.49 1309.91 1311.28 1311.67 1311.88 1312.59 1313.52
 1316.38 1317.34 1317.89 1318.54 1318.59 1318.62 1319.47 1321.95 1324.34 1326.51
 1327.73 1328.64 1331.31 1333.22 1334.38
                                                                                
                                                                                
                                                                                
                                                                                
                                                                                
                                                                                
                                                                                
                                                                                
                                                                                
                                                                                
                                                                                
                                                                                
                                        
Pier Skew= 45
BR Coef=-1 , 1 , 0 ,, 0 ,,,0.8,0,1.2,0,
WSPro=,,,, 1 ,,,, 0 ,,,, 0 ,,,,-1 ,-1 ,-1 , 0 , 0 , 0 , 0 , 0
Multiple Barrel Culv=1,3.5,,34,0.024,0.9,1,2,3,1294.11,1293.22, 3,Culvert #1  , 0 ,18
  356.17  375.03  360.17  379.03  364.17  383.03
Culvert Bottom n=0.024
BC Design=,, 0 ,, 0 ,,,,,,

Type RM Length L Ch R = 1 ,229347.1,462.32,472.32,482.4
BEGIN DESCRIPTION:
42079.06
END DESCRIPTION:
XS GIS Cut Line= 3
   1105022.20578   682437.369366  1104985.519525   681908.039045
   1104954.07198   681514.944783
#Sta/Elev= 30
       0 1301.23 231.535 1301.66 272.865 1301.21 342.678 1298.67  355.42 1299.11
 361.317 1299.94 366.861 1298.94 367.879 1298.17  373.23 1293.22  385.21 1293.22
 390.387 1296.23 399.777  1297.6 409.012 1297.26 430.621 1297.85 439.184 1298.57
 446.517 1297.76 474.264 1299.34 489.558 1300.47 518.776 1303.59 558.353 1306.46
  579.99  1309.2 590.724 1311.68 596.466 1314.74 601.154 1315.92 603.608 1317.45
 620.847 1318.54 628.236 1323.45 637.315 1325.35 647.038 1331.35 654.038 1334.96
#Mann= 3 , 0 , 0
       0     .09       0 367.879    .052       0 390.387     .09       0
#XS Ineff= 2 , 0
       0 362.385 1298.79 399.119       0 1298.79
Permanent Ineff=
       F       F
Bank Sta=367.879,390.387
Skew Angle= 45
Exp/Cntr=0.5,0.3

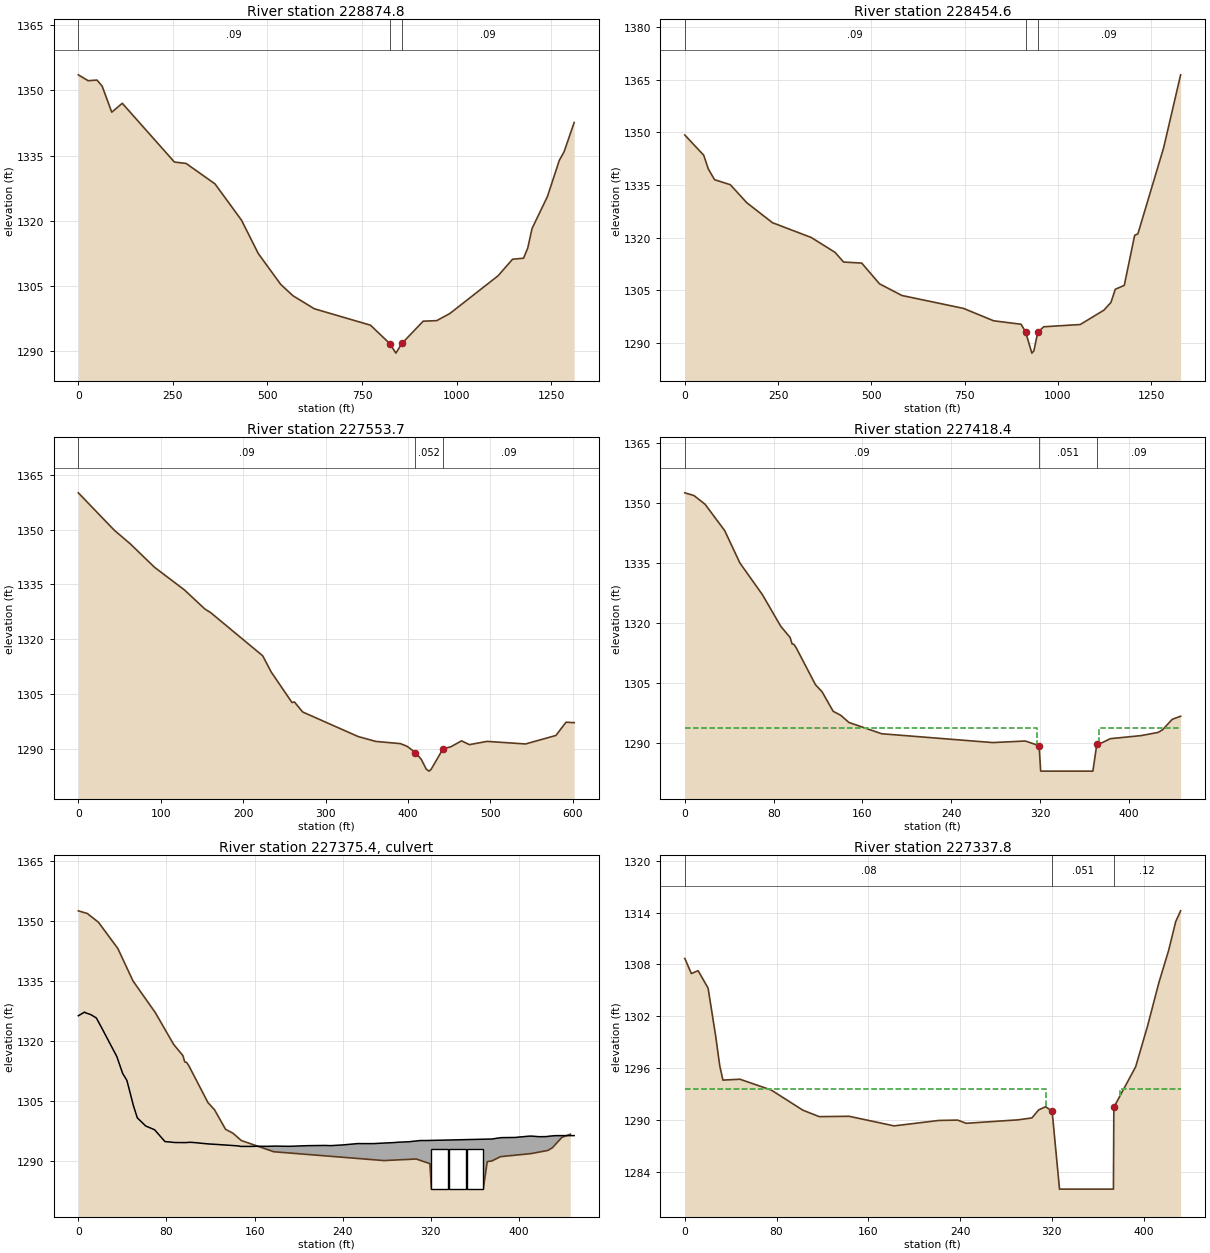
Type RM Length L Ch R = 1 ,228874.8,428.99,420.16,410.68
BEGIN DESCRIPTION:
41606.74
END DESCRIPTION:
XS GIS Cut Line= 4
  1105481.408148   682832.931342  1105429.205314   682051.564652
   1105458.14352   681942.242438   1105458.14352   681527.461047
#Sta/Elev= 30
       0 1353.59   25.95 1352.24    49.3 1352.39   62.95 1351.01   88.33    1345
  116.19 1347.05  253.98 1333.55  285.01 1333.22  361.38 1328.52  431.46 1320.18
  475.62 1312.54   535.2 1305.41  567.57 1302.81  623.88 1299.82  772.54 1296.04
  823.52 1291.81   839.6 1289.62  855.73 1291.86  911.79 1296.96  947.58 1297.09
   982.4 1298.73 1109.97 1307.41    1148  1311.2 1177.18 1311.44  1188.2 1313.76
 1199.69 1318.27 1240.42 1325.64 1271.69 1333.92  1284.5 1335.93 1310.98 1342.64
#Mann= 3 , 0 , 0
       0     .09       0  823.52    .052       0  855.73     .09       0
Bank Sta=823.52,855.73
Exp/Cntr=0.3,0.1

Type RM Length L Ch R = 1 ,228454.6,930.76,900.86,864.48
BEGIN DESCRIPTION:
41186.59
END DESCRIPTION:
XS GIS Cut Line= 4
  1106293.293164   682759.181671  1105862.332787   682227.771904
  1105849.371571    681916.70272  1105846.131278   681582.951441
#Sta/Elev= 30
       0 1349.29   50.73 1343.51   63.05 1339.58   79.81 1336.52  122.03 1335.09
  166.14 1329.95  235.02 1324.24  339.12 1320.01  402.56 1315.79   425.8    1313
  474.29 1312.71  522.08 1306.78   582.1 1303.45  747.09 1299.77  827.89 1296.23
  901.41 1295.24  913.42 1293.15  930.42 1286.99  935.88 1287.64  946.34 1292.94
  962.28 1294.52  1060.2 1295.16  1123.6 1299.26 1142.46 1301.47 1154.17 1305.23
 1178.22 1306.34 1206.07 1320.64 1214.75 1321.06 1283.76 1345.65  1329.3 1366.47
#Mann= 3 , 0 , 0
       0     .09       0  913.42    .052       0  946.34     .09       0
Bank Sta=913.42,946.34
Exp/Cntr=0.3,0.1

Type RM Length L Ch R = 1 ,227553.7,149.81,135.31,120.11
BEGIN DESCRIPTION:
40285.73
END DESCRIPTION:
XS GIS Cut Line= 4
  1106863.586579   682312.019786  1106649.726582   682000.950646
  1106562.238363    681958.82666  1106520.114422   681838.935468
#Sta/Elev= 30
       0 1360.05   43.61 1349.82   62.97  1346.1   92.47 1339.67  128.67 1333.49
  153.45 1328.27  160.69 1327.24  223.79 1315.43     234 1311.02  259.31 1302.64
  262.17 1302.81  272.23 1300.06  339.62 1293.33  361.06    1292  390.85  1291.4
   398.9 1290.67  409.12 1288.96  416.29 1287.05  422.14 1284.42  425.62 1283.87
  427.92  1284.3  442.67 1290.02  451.88 1290.52  465.02 1292.16  474.56 1291.12
   495.9 1292.01  542.71 1291.31  579.53 1293.63  591.82 1297.27  601.67 1297.13
#Mann= 3 , 0 , 0
       0     .09       0  409.12    .052       0  442.67     .09       0
Bank Sta=409.12,442.67
Exp/Cntr=0.5,0.3

Type RM Length L Ch R = 1 ,227418.4,100.12,80.64,79.35
BEGIN DESCRIPTION:
40150.41
END DESCRIPTION:
XS GIS Cut Line= 5
  1107156.087473   681864.988551   1106716.03464   681863.929925
  1106628.860721   681865.911151  1106553.475045   681869.194846
  1106545.864177   681841.469596
#Sta/Elev= 30
       0  1352.6   8.195 1351.93  18.314 1349.72  35.886 1343.16  49.625 1335.04
  69.862 1327.11  86.479 1319.16   94.88 1316.36  96.626 1314.75  98.168 1314.67
  100.36 1313.78 117.648 1304.57 123.631 1302.78 133.594  1297.9 140.453 1296.89
 147.856 1295.09 177.335 1292.27 277.384 1290.06 306.665 1290.45 319.082 1289.28
  320.49 1282.91  367.49 1282.91 371.125 1289.79 375.438 1289.98 383.224 1291.04
 410.801  1291.8  426.18  1292.6 430.282 1293.27 438.929 1295.88  446.51 1296.66
#Mann= 3 , 0 , 0
       0     .09       0 319.082    .051       0 371.125     .09       0
#XS Ineff= 2 , 0
       0  317.18 1293.63  373.13       0 1293.63
Permanent Ineff=
       F       F
Bank Sta=319.082,371.125
Skew Angle= 45
Exp/Cntr=0.5,0.3

Type RM Length L Ch R = 2 ,227375.4,,,
BEGIN DESCRIPTION:
40107.4  Culvert: 37111-0366
END DESCRIPTION:
Bridge Culvert--1,0,-1,-1, 0
Deck Dist Width WeirC Skew NumUp NumDn MinLoCord MaxHiCord MaxSubmerge Is_Ogee
17,47,2.6,45, 62, 61, , , 0.95, 0, 0,0,,
       0   5.713   6.442  11.278  16.313  19.926  34.945  40.192  44.088  49.936
  53.493  61.136  69.183  78.616  83.778  87.646  97.439 101.533 107.077  110.21
 114.049  118.37 125.695 144.914 147.128 154.934 163.943 170.144 177.081 177.901
 191.089 208.589  208.66  208.71 219.069 224.216 229.096 239.603 253.689 257.281
 267.965 268.241 268.559 283.253 285.402 291.703 299.834 310.342 315.794 375.467
 380.869 384.136 396.786 397.868   401.7 409.082  411.19 418.487 424.971 427.694
 433.379     450
 1326.32 1327.25 1327.07 1326.62 1325.77 1323.96  1316.1  1311.9 1310.13 1303.87
 1300.77 1298.72 1297.78 1294.82 1294.69 1294.58 1294.56 1294.64 1294.53 1294.43
 1294.33 1294.22  1294.1 1293.74 1293.61  1293.6 1293.65 1293.63 1293.67 1293.69
 1293.63  1293.8  1293.8  1293.8 1293.83 1293.85  1293.8 1293.97 1294.32 1294.31
 1294.31 1294.32 1294.32 1294.53 1294.55 1294.68 1294.77 1295.08 1295.08 1295.46
  1295.7 1295.81 1295.85  1295.9 1295.99 1296.18 1296.19 1296.04 1296.07 1296.18
 1296.31 1296.31
                                                                                
                                                                                
                                                                                
                                                                                
                                                                                
                                                                                
                
       0   5.713   6.442  11.278  16.313  19.926  34.945  40.192  44.088  49.936
  53.493  61.136  69.183  78.616  83.778  87.646  97.439 101.533 107.077  110.21
 114.049  118.37 125.695 144.914 147.128 154.934 163.943 170.144 177.081 177.901
 191.089 208.589  208.66  208.71 219.069 224.216 229.096 239.603 253.689 257.281
 267.965 268.241 268.559 283.253 285.402 291.703 299.834 310.342 315.794 375.467
 380.869 384.136 396.786 397.868   401.7 409.082  411.19 418.487 424.971 427.694
 433.379
 1326.32 1327.25 1327.07 1326.62 1325.77 1323.96  1316.1  1311.9 1310.13 1303.87
 1300.77 1298.72 1297.78 1294.82 1294.69 1294.58 1294.56 1294.64 1294.53 1294.43
 1294.33 1294.22  1294.1 1293.74 1293.61  1293.6 1293.65 1293.63 1293.67 1293.69
 1293.63  1293.8  1293.8  1293.8 1293.83 1293.85  1293.8 1293.97 1294.32 1294.31
 1294.31 1294.32 1294.32 1294.53 1294.55 1294.68 1294.77 1295.08 1295.08 1295.46
  1295.7 1295.81 1295.85  1295.9 1295.99 1296.18 1296.19 1296.04 1296.07 1296.18
 1296.31
                                                                                
                                                                                
                                                                                
                                                                                
                                                                                
                                                                                
        
Pier Skew= 45
BR Coef=-1 , 1 , 0 ,, 0 ,,,0.8,0,1.2,0,
WSPro=,,,, 1 ,,,, 0 ,,,, 0 ,,,,-1 ,-1 ,-1 , 0 , 0 , 0 , 0 , 0
Multiple Barrel Culv=2,10,15,50,0.013,0.2,1,8,1,1282.91,1282, 3,Culvert #1  , 0 ,15
  327.99  334.26  343.99  350.26  359.99  366.26
Culvert Bottom n=0.013
BC Design=,, 0 ,, 0 ,,,,,,

Type RM Length L Ch R = 1 ,227337.8,374.39,420.18,446.12
BEGIN DESCRIPTION:
40069.77
END DESCRIPTION:
XS GIS Cut Line= 5
  1107185.317411   681728.918195  1106997.368651   681741.093949
  1106763.286365   681783.969234  1106643.146797   681791.430748
  1106578.482163   681788.193565
#Sta/Elev= 30
       0  1308.7   5.728 1306.95  11.625 1307.28  20.301 1305.27  26.757 1299.87
   30.49 1296.27  33.255 1294.62   48.09 1294.72  75.378 1293.47 103.047 1291.13
 117.267 1290.39 143.295 1290.43 182.483 1289.32 221.614 1289.95 237.814 1289.99
 245.387 1289.62 290.614 1290.02 302.677 1290.24 308.581 1291.17 314.648 1291.54
 320.305 1291.01  326.76    1282  373.76    1282  374.13 1291.47 393.173 1296.17
 403.454 1300.85 413.438 1305.92 421.924 1309.64 428.089 1312.97 432.353 1314.21
#Mann= 3 , 0 , 0
       0     .08       0 320.305    .051       0  374.13     .12       0
#XS Ineff= 2 , 0
       0  314.69 1293.63  379.62       0 1293.63
Permanent Ineff=
       F       F
Bank Sta=320.305,374.13
Skew Angle= 45
Exp/Cntr=0.5,0.3

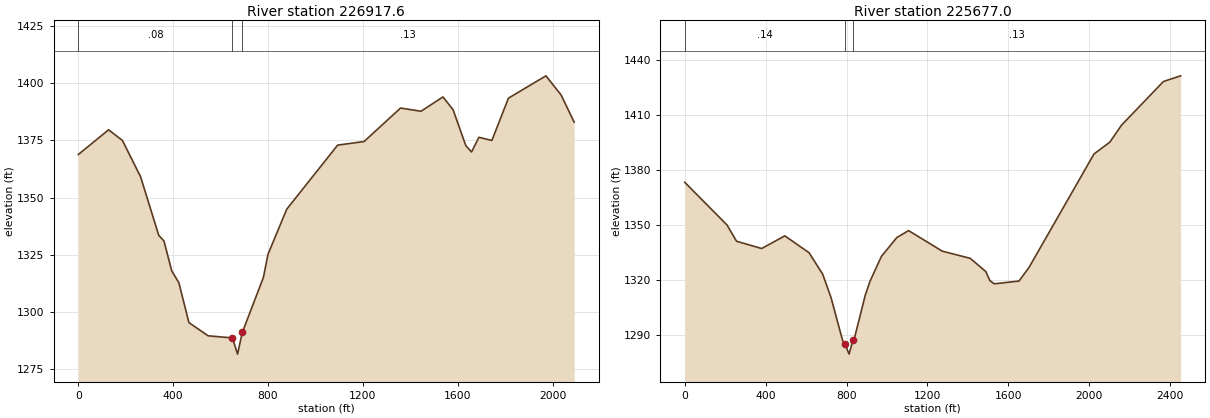
Type RM Length L Ch R = 1 ,226917.6,1240.46,1240.61,1238.44
BEGIN DESCRIPTION:
39649.59
END DESCRIPTION:
XS GIS Cut Line= 3
  1107505.105622   682039.038969  1107021.018346   681536.470918
  1105973.313174   680617.644775
#Sta/Elev= 30
       0 1368.79  127.67 1379.58  186.11  1374.9  262.51  1359.1  339.24 1333.51
  361.27 1331.04  393.85 1318.04  424.06 1312.82  466.41 1295.44  547.31 1289.67
  650.01 1288.75  671.51 1281.67  691.62 1291.11  780.53 1315.13  800.05 1325.27
     879 1344.92 1093.78 1372.88 1205.25 1374.46 1359.21 1389.07 1445.34 1387.67
 1538.06 1393.92 1580.56 1388.36 1634.39 1372.65 1658.58 1369.89 1689.54 1376.29
 1744.27 1374.93 1814.21 1393.38 1972.23 1403.13 2036.21  1394.8 2091.32 1382.92
#Mann= 3 , 0 , 0
       0     .08       0  650.01    .051       0  691.62     .13       0
Bank Sta=650.01,691.62
Exp/Cntr=0.3,0.1

Type RM Length L Ch R = 1 ,225677.0,718.37,712.8,704.89
BEGIN DESCRIPTION:
38408.98
END DESCRIPTION:
XS GIS Cut Line= 3
   1108446.80244   681177.914784  1107916.268227   680719.428488
  1106641.625805   679518.979311
#Sta/Elev= 30
       0 1373.31  209.03 1350.03  255.94 1341.18  380.22 1337.21  494.72 1344.12
  614.57 1334.91  682.08 1323.19  723.37 1310.36  780.38  1287.1  792.37 1284.99
  812.41 1279.58  832.27 1287.41  840.75 1289.04  892.09 1311.57  915.41 1319.21
  972.38 1332.89 1048.59 1343.19 1106.64 1346.99 1273.76 1335.75 1411.47 1331.86
 1488.41 1324.65  1509.1 1319.67 1530.07 1317.95 1652.95 1319.45 1702.69 1326.93
  2023.8 1388.81 2102.11 1395.25 2159.83 1404.52 2367.23 1428.35 2452.14 1431.44
#Mann= 3 , 0 , 0
       0     .14       0  792.37    .051       0  832.27     .13       0
Bank Sta=792.37,832.27
Exp/Cntr=0.3,0.1