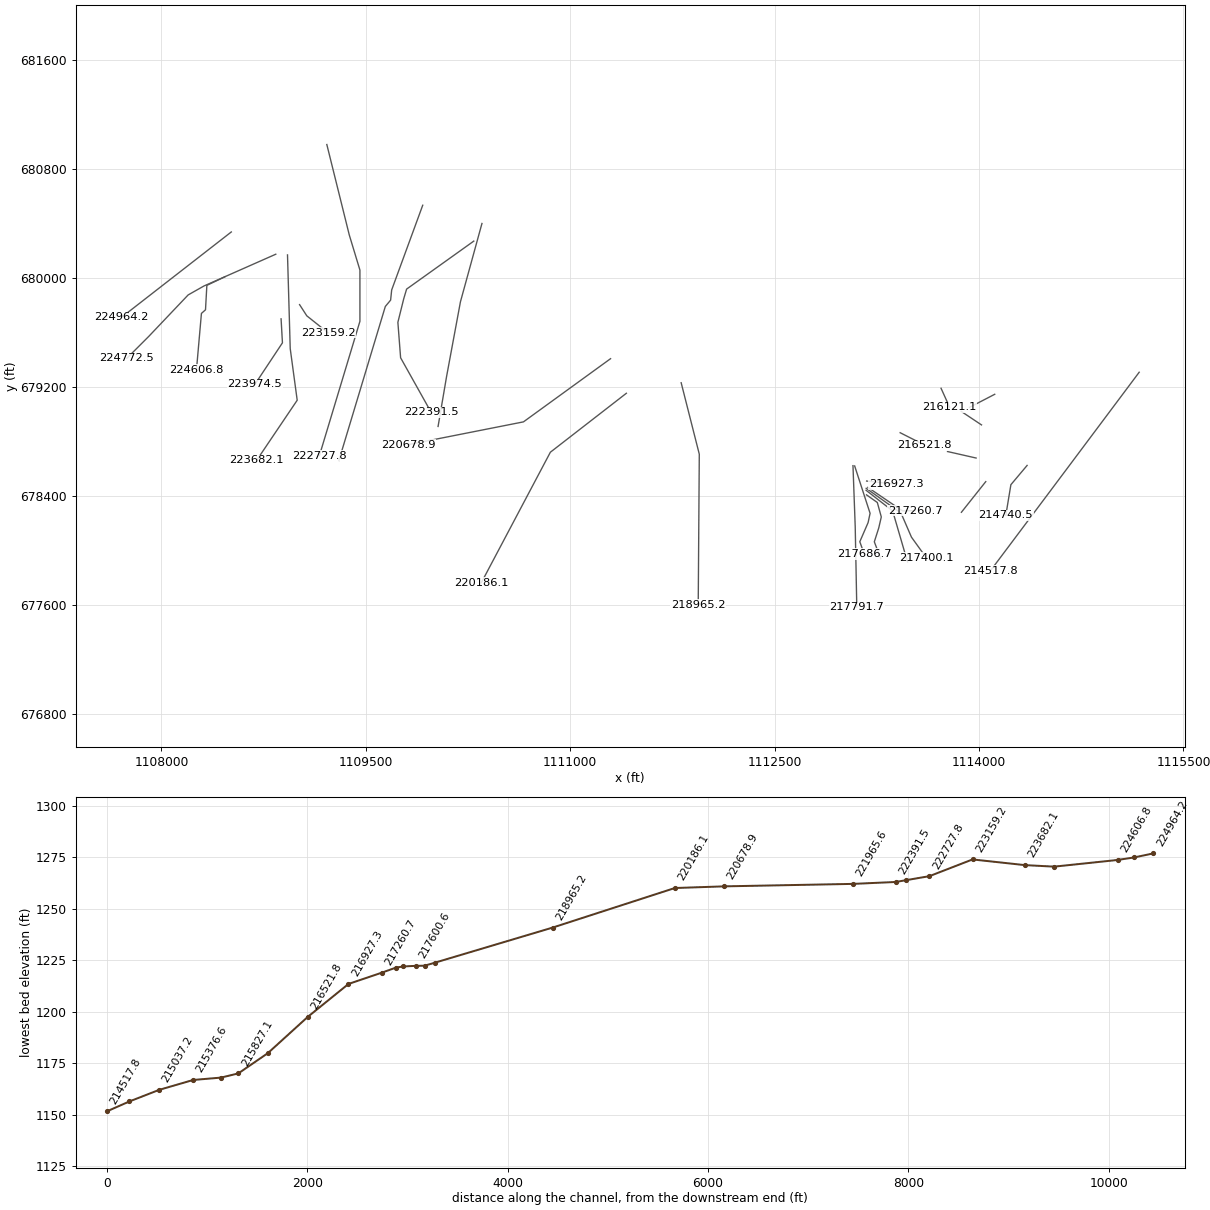
HEC-RAS study 2ndBroadRv.prj: 2ndBroadRv

--- 2ndBroadRv.g01 (geometry) --- (continued)

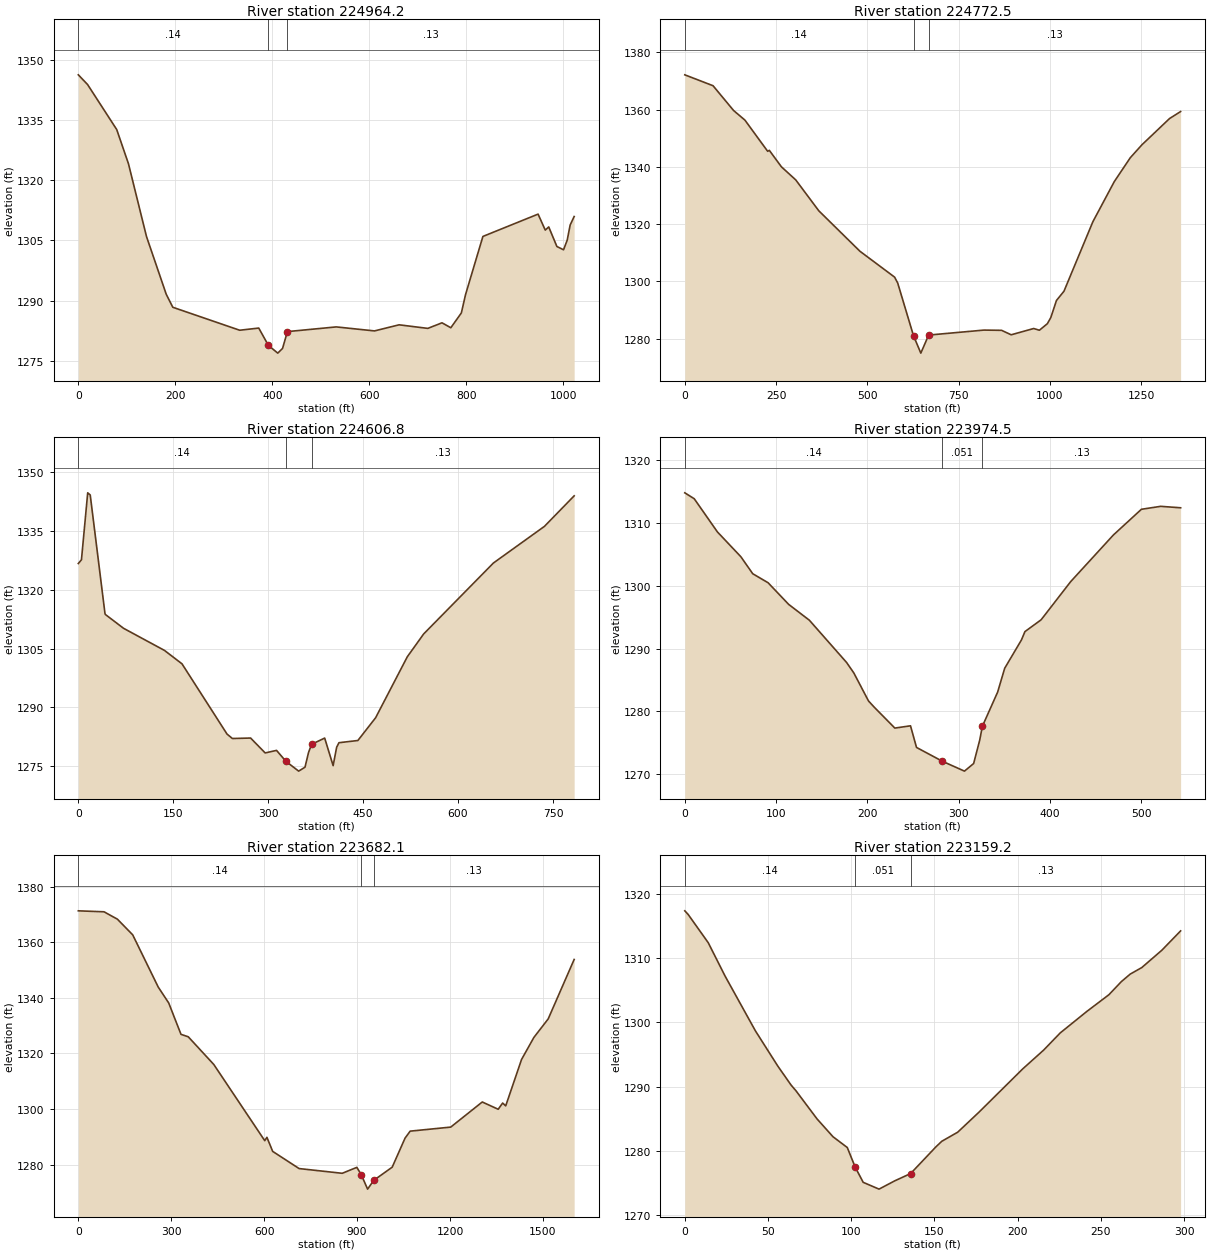
Type RM Length L Ch R = 1 ,224964.2,180.68,191.66,203.8
XS GIS Cut Line= 2
  1108512.572923   680335.537652   1107705.49135   679707.807535
#Sta/Elev= 30
       0 1346.24   19.09 1343.82   79.17 1332.61   103.4 1324.09  140.51 1305.99
  181.21 1291.61  194.82 1288.35  332.74 1282.63  372.05 1283.17  391.91 1278.86
  411.28 1276.93  421.12  1278.1  431.14 1282.29  531.91 1283.46  610.72 1282.46
  661.46 1283.98   720.7 1283.09  749.92 1284.48  768.15 1283.25  789.86 1286.94
   798.5 1291.51  834.29 1305.99  948.08 1311.55  962.86 1307.57  970.04 1308.36
  986.88 1303.48 1000.57 1302.67 1008.16 1305.07 1014.19 1308.83 1022.46 1310.95
#Mann= 3 , 0 , 0
       0     .14       0  391.91    .051       0  431.14     .13       0
Bank Sta=391.91,431.14
Exp/Cntr=0.3,0.1

Type RM Length L Ch R = 1 ,224772.5,125.98,165.69,199.29
BEGIN DESCRIPTION:
37504.52
END DESCRIPTION:
XS GIS Cut Line= 5
  1108838.956689   680172.102992  1108312.407361   679939.206207
  1108195.958946   679873.387524  1107907.369416   679569.609043
  1107745.354238   679407.593865
#Sta/Elev= 30
       0 1372.11   77.32 1368.31  133.66 1359.65  164.66  1356.3  226.91 1345.42
  231.52 1345.74  264.56    1340  303.77 1335.44  366.93 1324.65  479.58 1310.53
  574.46  1301.5  583.03 1299.42  626.23 1281.05  646.29 1274.97  667.69 1281.27
  819.03 1283.01  867.39 1282.93  893.73 1281.37  955.29 1283.56  970.95 1282.96
  992.87 1285.26 1002.25 1287.41 1017.66 1293.34 1038.26 1296.58 1117.41 1320.84
 1176.11 1334.86 1219.86 1343.18 1251.65 1347.68 1327.49 1356.87 1357.65 1359.29
#Mann= 3 , 0 , 0
       0     .14       0  626.23    .051       0  667.69     .13       0
Bank Sta=626.23,667.69
Exp/Cntr=0.3,0.1

Type RM Length L Ch R = 1 ,224606.8,630.72,632.32,631.71
XS GIS Cut Line= 5
  1108466.074364   680006.726598  1108333.221467   679943.621472
  1108323.257455   679764.270017  1108293.365553   679737.699437
  1108256.831007      679322.534
#Sta/Elev= 30
       0  1326.7    4.94 1327.65   14.81 1344.73    18.8 1344.18   42.07 1313.99
   42.71  1313.7   71.49 1310.17  136.14 1304.53   163.8 1301.11  234.97 1283.19
  243.45 1282.06  272.22 1282.18  295.23 1278.38  313.21 1279.03   328.1 1276.23
  348.15 1273.74  358.16 1274.74  363.78 1278.51   368.6 1280.58  389.27 1282.17
  402.62 1275.14  408.17 1279.83  411.81 1280.99  441.69 1281.55  469.74 1287.35
  519.84 1302.91  545.72 1308.74  655.92 1326.83  736.57 1336.18  783.47 1343.96
#Mann= 3 , 0 , 0
       0     .14       0   328.1    .051       0   368.6     .13       0
Bank Sta=328.1,368.6
Exp/Cntr=0.3,0.1

Type RM Length L Ch R = 1 ,223974.5,269.46,292.4,310.15
XS GIS Cut Line= 3
  1108877.918479   679697.843568  1108887.882446    679521.81339
  1108685.281733   679216.251638
#Sta/Elev= 30
       0 1314.78   10.33 1313.84   35.71 1308.56    61.4 1304.61   74.39 1301.91
   91.23 1300.47  113.74 1297.03  136.41 1294.51  177.21 1287.78   185.1 1286.12
  201.19 1281.66  207.53 1280.66     230 1277.35  247.16 1277.71  253.73 1274.27
  282.18 1272.06  306.24  1270.5  316.28 1271.71  322.91 1275.41  325.85 1277.63
  342.56 1283.07   350.3 1286.87  368.63 1291.37  372.47  1292.7  390.19 1294.58
  422.54 1300.65  469.38 1308.08  499.99 1312.16   521.1 1312.63  542.94  1312.4
#Mann= 3 , 0 , 0
       0     .14       0  282.18    .051       0  325.85     .13       0
Bank Sta=282.18,325.85
Exp/Cntr=0.3,0.1

Type RM Length L Ch R = 1 ,223682.1,524.83,522.92,517.4
BEGIN DESCRIPTION:
36414.11
END DESCRIPTION:
XS GIS Cut Line= 4
  1108925.027247   680167.040023   1108944.99694   679479.263911
  1108996.167268   679100.603301  1108699.379273   678660.538296
#Sta/Elev= 30
       0 1371.28   83.04 1370.93  126.14 1368.28  175.57 1362.65  257.95 1343.88
  291.83 1338.16  331.47 1326.88  354.95    1326  437.39 1316.05  601.92 1288.66
  608.95 1289.86  627.59  1284.8  712.89 1278.63  852.07 1276.93  899.29 1279.06
  913.32 1276.48  934.04 1271.24  953.71 1274.38 1013.44 1279.13 1054.95 1289.57
 1071.45 1292.08 1202.53 1293.54 1304.21 1302.56 1355.71 1299.95 1370.06 1302.18
 1379.95 1301.16 1431.13 1317.85 1470.95 1325.77  1517.2 1332.44 1600.96 1353.79
#Mann= 3 , 0 , 0
       0     .14       0  913.32    .051       0  953.71     .13       0
Bank Sta=913.32,953.71
Exp/Cntr=0.3,0.1

Type RM Length L Ch R = 1 ,223159.2,454.7,431.45,404.33
XS GIS Cut Line= 3
  1109013.605011   679802.187085  1109066.651013   679719.965786
  1109223.136725   679595.307667
#Sta/Elev= 30
       0 1317.41       2 1316.85   14.08 1312.44   24.21 1307.23   42.47 1298.67
   55.92 1293.18    63.9 1290.22   66.77 1289.35    79.5 1284.94   89.06 1282.17
   97.63 1280.49  102.32 1277.47  107.19 1275.06  116.71    1274  126.22  1275.3
   135.7 1276.43  150.84 1280.58   154.4 1281.46  163.98 1282.88  176.71 1285.99
  203.07 1292.76  215.63 1295.69  225.56 1298.36  241.54 1301.71  254.86 1304.33
  262.32 1306.37  267.63 1307.54  274.59 1308.56  286.63 1311.26  297.92 1314.28
#Mann= 3 , 0 , 0
       0     .14       0  102.32    .051       0   135.7     .13       0
Bank Sta=102.32,135.7
Exp/Cntr=0.3,0.1

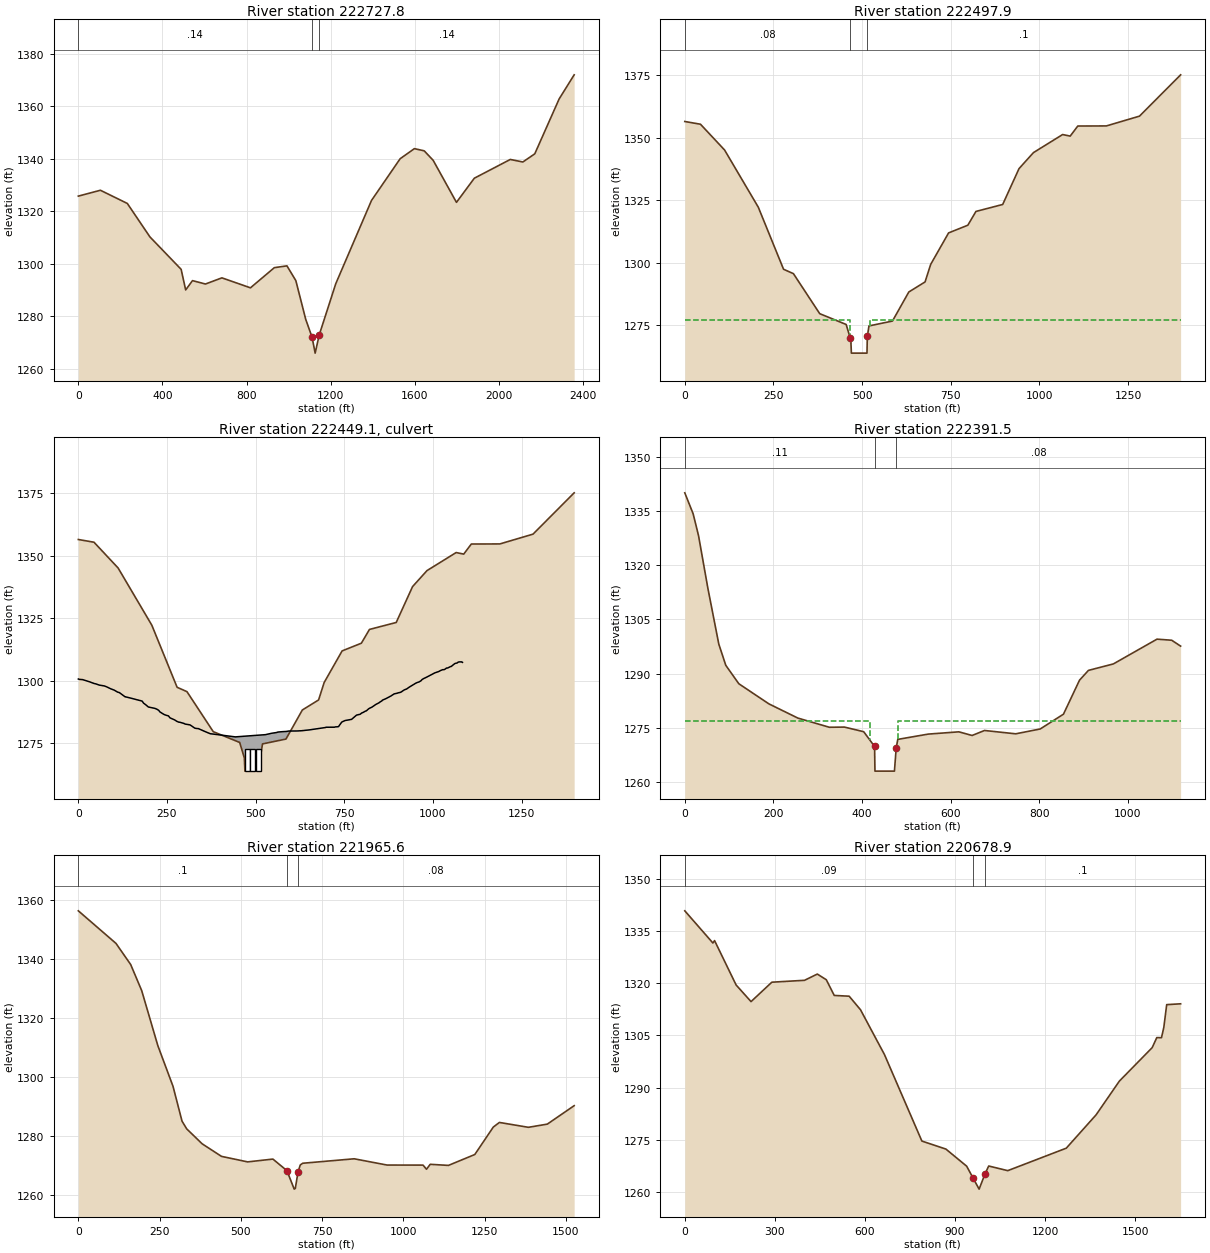
Type RM Length L Ch R = 1 ,222727.8,232.91,229.81,226.7
BEGIN DESCRIPTION:
35459.74
END DESCRIPTION:
XS GIS Cut Line= 5
  1109213.616821   680977.115957  1109378.253642   680313.746216
  1109456.496853   680055.543739  1109456.496853   679679.976467
  1109159.172748   678694.112333
#Sta/Elev= 30
       0 1325.69  104.98 1327.92  233.02  1322.9  340.57 1310.15  489.07 1297.79
  510.64 1289.95  543.05 1293.49  604.69  1292.2  682.94 1294.55  818.79 1290.75
  932.35 1298.43  992.36 1299.12 1034.69 1293.49 1081.88 1278.69 1111.94 1271.92
 1126.52 1265.87 1145.87 1272.79  1224.3 1292.26 1394.54 1324.03 1530.78 1339.93
 1598.62 1343.78 1645.32 1342.94 1688.16  1339.3  1798.7 1323.31 1883.72 1332.51
 2054.76 1339.66 2114.47 1338.69 2171.25  1341.8 2287.12  1362.7 2358.58  1371.9
#Mann= 3 , 0 , 0
       0     .14       0 1111.94     .05       0 1145.87     .14       0
Bank Sta=1111.94,1145.87
Exp/Cntr=0.5,0.3

Type RM Length L Ch R = 1 ,222497.9,114.28,106.46,98.71
BEGIN DESCRIPTION:
35229.93
END DESCRIPTION:
XS GIS Cut Line= 5
  1109917.370233   680531.574173  1109689.470892   679909.755836
  1109681.746698   679835.322434  1109642.885973   679788.679053
  1109302.371615   678658.972703
#Sta/Elev= 30
       0 1356.41  44.222 1355.32 112.225 1345.03 207.274 1322.21 278.586 1297.42
 306.361 1295.68 380.558  1279.7 455.122 1275.39 467.023 1269.79 468.296 1269.19
  469.85 1263.95  513.85 1263.95   514.8 1270.65 519.469 1274.81 585.711 1276.75
 631.779 1288.35 677.663 1292.37 693.403 1299.34 744.018 1311.94 798.324 1315.01
 821.149 1320.51 896.611 1323.29 942.679  1337.6 983.366 1343.991065.617  1351.2
1087.014 1350.581108.411  1354.61188.979 1354.641282.451 1358.551398.459 1375.04
#Mann= 3 , 0 , 0
       0     .08       0 467.023     .05       0   514.8      .1       0
#XS Ineff= 2 , 0
       0   464.6    1277  522.47       0    1277
Permanent Ineff=
       F       F
Bank Sta=467.023,514.8
Skew Angle= 45
Exp/Cntr=0.5,0.3

Type RM Length L Ch R = 2 ,222449.1,,,
BEGIN DESCRIPTION:
35181.1  Culvert: 37111-0367
END DESCRIPTION:
Bridge Culvert--1,0,-1,-1, 0
Deck Dist Width WeirC Skew NumUp NumDn MinLoCord MaxHiCord MaxSubmerge Is_Ogee
30,44,2.6,45, 153, 154, , , 0.95, 0, 0,0,,
       0   2.404   12.53  16.596  19.368  31.523  43.077  45.212  48.331  48.868
  59.107  69.982  73.751  79.832  87.328  91.287 101.017 110.952 115.386 131.996
 132.349 148.775 179.846 184.081 190.502 197.474 215.462 217.449 220.844 226.585
 227.971 229.788 238.019 242.905 248.675 254.134 258.356 268.446  269.04 271.564
 277.603 283.444 286.131 297.048 297.756 301.256 314.663 319.966  325.92 328.246
 332.701 339.234 340.472 353.631 354.048 356.643 371.698 371.783 371.938 390.839
 444.028 444.615 464.194 488.597 527.784 545.384  558.36 562.822 562.921 574.694
 575.076 586.835 592.951 616.604 630.322 652.575  697.49 698.409 722.444 724.502
 733.694 742.872 748.649 749.993 752.164 770.562 784.825 790.128  794.71 799.632
 803.521  809.22  812.43 818.844 821.297 828.446   830.2 838.148 839.152 847.779
  848.04 851.095 856.554 857.544 866.043 866.736 873.496 875.045 882.215 884.202
 890.877 899.369 902.113 908.003  911.15 916.828 920.455 925.567 929.555 933.925
  947.12 951.935 957.253 960.824 966.509 969.804 975.977 978.671 985.148 987.482
 994.482 996.3841003.7881004.4241005.4991013.3191016.4591022.8161027.5111032.326
1038.577 1041.831049.7921051.5531060.9361061.4241062.9161068.5731071.4291075.417
1081.5981082.2061083.401
 1300.73 1300.59 1300.46 1300.28 1300.16 1299.61 1298.99 1298.89 1298.81  1298.8
 1298.29 1298.03 1297.94  1297.6 1297.08 1296.82 1296.29 1295.48 1295.33  1293.6
 1293.63 1293.06 1291.91 1291.08  1290.4 1289.55 1289.01  1288.9 1288.72 1288.23
 1287.97 1287.63 1286.88 1286.49 1286.21    1286 1285.23  1284.6 1284.53  1284.4
 1283.84 1283.49 1283.47 1283.01 1282.99 1282.73 1282.42 1281.95 1281.35 1281.12
 1280.98  1280.9  1280.8 1279.95 1279.89 1279.79  1278.9 1278.89 1278.89 1278.55
  1277.6 1277.64 1277.84 1278.07 1278.51 1279.07 1279.34 1279.55 1279.55  1279.7
  1279.7 1279.79 1279.95 1279.98 1280.08 1280.43 1281.37 1281.47 1281.48  1281.6
 1281.69 1283.52 1283.88 1283.97 1284.14 1284.61 1286.32 1286.49 1286.64 1287.18
 1287.39 1287.87 1288.03 1288.83 1289.04 1289.52  1289.7 1290.44 1290.57 1291.21
 1291.23 1291.56 1292.04 1292.27 1292.78 1292.83 1293.29 1293.44 1293.98 1294.19
 1294.79 1295.05 1295.21 1295.37 1295.59 1296.16 1296.45 1296.71  1297.1 1297.53
 1298.67 1299.07  1299.4 1299.54 1300.03 1300.55 1301.04 1301.19 1301.66 1301.84
 1302.36 1302.49 1303.02 1303.09 1303.17 1303.58 1303.71 1304.18 1304.44 1304.48
  1305.1 1305.12 1305.69  1305.7 1306.79 1306.84 1306.94 1307.13 1307.48 1307.56
 1307.56 1307.46 1307.36
                                                                                
                                                                                
                                                                                
                                                                                
                                                                                
                                                                                
                                                                                
                                                                                
                                                                                
                                                                                
                                                                                
                                                                                
                                                                                
                                                                                
                                                                                
                        
       0   2.404   12.53  16.596  19.368  31.523  43.077  45.212  48.331  48.868
  59.107  69.982  73.751  79.832  87.328  91.287 101.017 110.952 115.386 131.996
 132.349 148.775 179.846 184.081 190.502 197.474 215.462 217.449 220.844 226.585
 227.971 229.788 238.019 242.905 248.675 254.134 258.356 268.446  269.04 271.564
 277.603 283.444 286.131 297.048 297.756 301.256 314.663 319.966  325.92 328.246
 332.701 339.234 340.472 353.631 354.048 356.643 371.698 371.783 371.938 390.839
 444.028 444.615 464.194 488.597 527.784 545.384  558.36 562.822 562.921 574.694
 575.076 586.835 592.951 616.604 630.322 652.575  697.49 698.409 722.444 724.502
 733.694 742.872 748.649 749.993 752.164 770.562 784.825 790.128  794.71 799.632
 803.521  809.22  812.43 818.844 821.297 828.446   830.2 838.148 839.152 847.779
  848.04 851.095 856.554 857.544 866.043 866.736 873.496 875.045 882.215 884.202
 890.877 899.369 902.113 908.003  911.15 916.828 920.455 925.567 929.555 933.925
  947.12 951.935 957.253 960.824 966.509 969.804 975.977 978.671 985.148 987.482
 994.482 996.3841003.7881004.4241005.4991013.3191016.4591022.8161027.5111032.326
1038.577 1041.831049.7921051.5531060.9361061.4241062.9161068.5731071.4291075.417
1081.5981082.2061083.401  1124.3
 1300.73 1300.59 1300.46 1300.28 1300.16 1299.61 1298.99 1298.89 1298.81  1298.8
 1298.29 1298.03 1297.94  1297.6 1297.08 1296.82 1296.29 1295.48 1295.33  1293.6
 1293.63 1293.06 1291.91 1291.08  1290.4 1289.55 1289.01  1288.9 1288.72 1288.23
 1287.97 1287.63 1286.88 1286.49 1286.21    1286 1285.23  1284.6 1284.53  1284.4
 1283.84 1283.49 1283.47 1283.01 1282.99 1282.73 1282.42 1281.95 1281.35 1281.12
 1280.98  1280.9  1280.8 1279.95 1279.89 1279.79  1278.9 1278.89 1278.89 1278.55
  1277.6 1277.64 1277.84 1278.07 1278.51 1279.07 1279.34 1279.55 1279.55  1279.7
  1279.7 1279.79 1279.95 1279.98 1280.08 1280.43 1281.37 1281.47 1281.48  1281.6
 1281.69 1283.52 1283.88 1283.97 1284.14 1284.61 1286.32 1286.49 1286.64 1287.18
 1287.39 1287.87 1288.03 1288.83 1289.04 1289.52  1289.7 1290.44 1290.57 1291.21
 1291.23 1291.56 1292.04 1292.27 1292.78 1292.83 1293.29 1293.44 1293.98 1294.19
 1294.79 1295.05 1295.21 1295.37 1295.59 1296.16 1296.45 1296.71  1297.1 1297.53
 1298.67 1299.07  1299.4 1299.54 1300.03 1300.55 1301.04 1301.19 1301.66 1301.84
 1302.36 1302.49 1303.02 1303.09 1303.17 1303.58 1303.71 1304.18 1304.44 1304.48
  1305.1 1305.12 1305.69  1305.7 1306.79 1306.84 1306.94 1307.13 1307.48 1307.56
 1307.56 1307.46 1307.36 1307.36
                                                                                
                                                                                
                                                                                
                                                                                
                                                                                
                                                                                
                                                                                
                                                                                
                                                                                
                                                                                
                                                                                
                                                                                
                                                                                
                                                                                
                                                                                
                                
Pier Skew= 45
BR Coef=-1 , 1 , 0 ,, 0 ,,,0.8,0,1.2,0,
WSPro=,,,, 1 ,,,, 0 ,,,, 0 ,,,,-1 ,-1 ,-1 , 0 , 0 , 0 , 0 , 0
Multiple Barrel Culv=2,9,14,60,0.013,0.2,1,8,1,1263.95,1263.05, 3,Culvert #1  , 0 ,23
  476.85   436.2  491.85   451.2  506.85   466.2
Culvert Bottom n=0.013
BC Design=,, 0 ,, 0 ,,,,,,

Type RM Length L Ch R = 1 ,222391.5,425,425.88,430
BEGIN DESCRIPTION:
35123.46
END DESCRIPTION:
XS GIS Cut Line= 6
  1110292.030366   680268.299531  1109799.014426   679916.075651
  1109777.948391   679845.153263  1109735.025127    679672.50358
  1109755.055371   679412.110285  1109979.394255   679011.505153
#Sta/Elev= 30
       0 1340.02  18.873 1334.21  31.056 1328.15  52.022 1313.67  76.742 1298.19
  92.539 1292.31 121.933 1287.22  189.83 1281.65 255.244 1277.72 326.323 1275.18
 360.419 1275.23 403.829 1273.95  428.35 1269.87   429.2 1263.05   473.2 1263.05
  477.21  1269.5 480.755 1271.83   549.5 1273.29 618.598 1273.92 648.459 1272.91
 676.524 1274.29 746.931 1273.37 802.114  1274.7 854.694  1278.8 890.969 1288.21
 911.079 1290.91 967.372  1292.71065.808 1299.551099.042 1299.251119.138 1297.62
#Mann= 3 , 0 , 0
       0     .11       0  428.35     .05       0  477.21     .08       0
#XS Ineff= 2 , 0
       0  417.27    1277  481.79       0    1277
Permanent Ineff=
       F       F
Bank Sta=428.35,477.21
Skew Angle= 45
Exp/Cntr=0.5,0.3

Type RM Length L Ch R = 1 ,221965.6,1320.93,1286.73,1248.33
BEGIN DESCRIPTION:
34697.58
END DESCRIPTION:
XS GIS Cut Line= 4
  1110351.986402   680397.692903  1110194.281337   679823.575551
  1110092.565194   679275.873249  1110029.970634   678908.130258
#Sta/Elev= 30
       0 1356.44  115.94 1345.39  161.07 1338.24  194.97  1329.4  244.58 1310.77
  291.39 1296.94  319.03 1285.16  333.39 1282.55  381.03 1277.47  440.51 1273.22
  520.87 1271.35  598.68  1272.3  641.79 1268.38  664.15 1262.12  667.54 1262.34
  676.02 1267.95  682.85 1270.32  690.35 1270.89  848.76  1272.4  949.77 1270.28
 1060.58 1270.26 1071.15 1268.86 1082.68 1270.53 1138.72 1270.16 1219.81 1273.85
  1276.7 1283.15  1295.5 1284.72 1384.73 1283.07 1442.87 1284.15 1525.48  1290.4
#Mann= 3 , 0 , 0
       0      .1       0  641.79     .05       0  676.02     .08       0
Bank Sta=641.79,676.02
Exp/Cntr=0.3,0.1

Type RM Length L Ch R = 1 ,220678.9,464.44,492.75,519.3
BEGIN DESCRIPTION:
33410.85
END DESCRIPTION:
XS GIS Cut Line= 3
  1111295.766532   679405.462709  1110656.564516   678941.800207
  1109811.047801    678774.72206
#Sta/Elev= 30
       0 1340.75   93.59 1331.52   99.18 1332.21  170.95 1319.48  220.62 1314.71
  290.02 1320.28  398.83 1320.82  441.45 1322.61  471.35 1320.98  497.78 1316.48
  547.45 1316.26  585.25 1312.38  665.05 1299.52  789.66 1274.71  869.66 1272.41
  938.75 1267.51  959.55 1264.21  980.32 1260.92 1000.16 1265.31  1012.3 1267.55
 1075.75 1266.22 1270.72 1272.67 1370.07 1282.24 1447.55 1291.91 1556.84 1301.51
 1572.22 1304.39 1587.84 1304.36  1595.6 1307.34 1605.16 1313.84 1651.53 1314.08
#Mann= 3 , 0 , 0
       0     .09       0  959.55     .05       0 1000.16      .1       0
Bank Sta=959.55,1000.16
Exp/Cntr=0.3,0.1

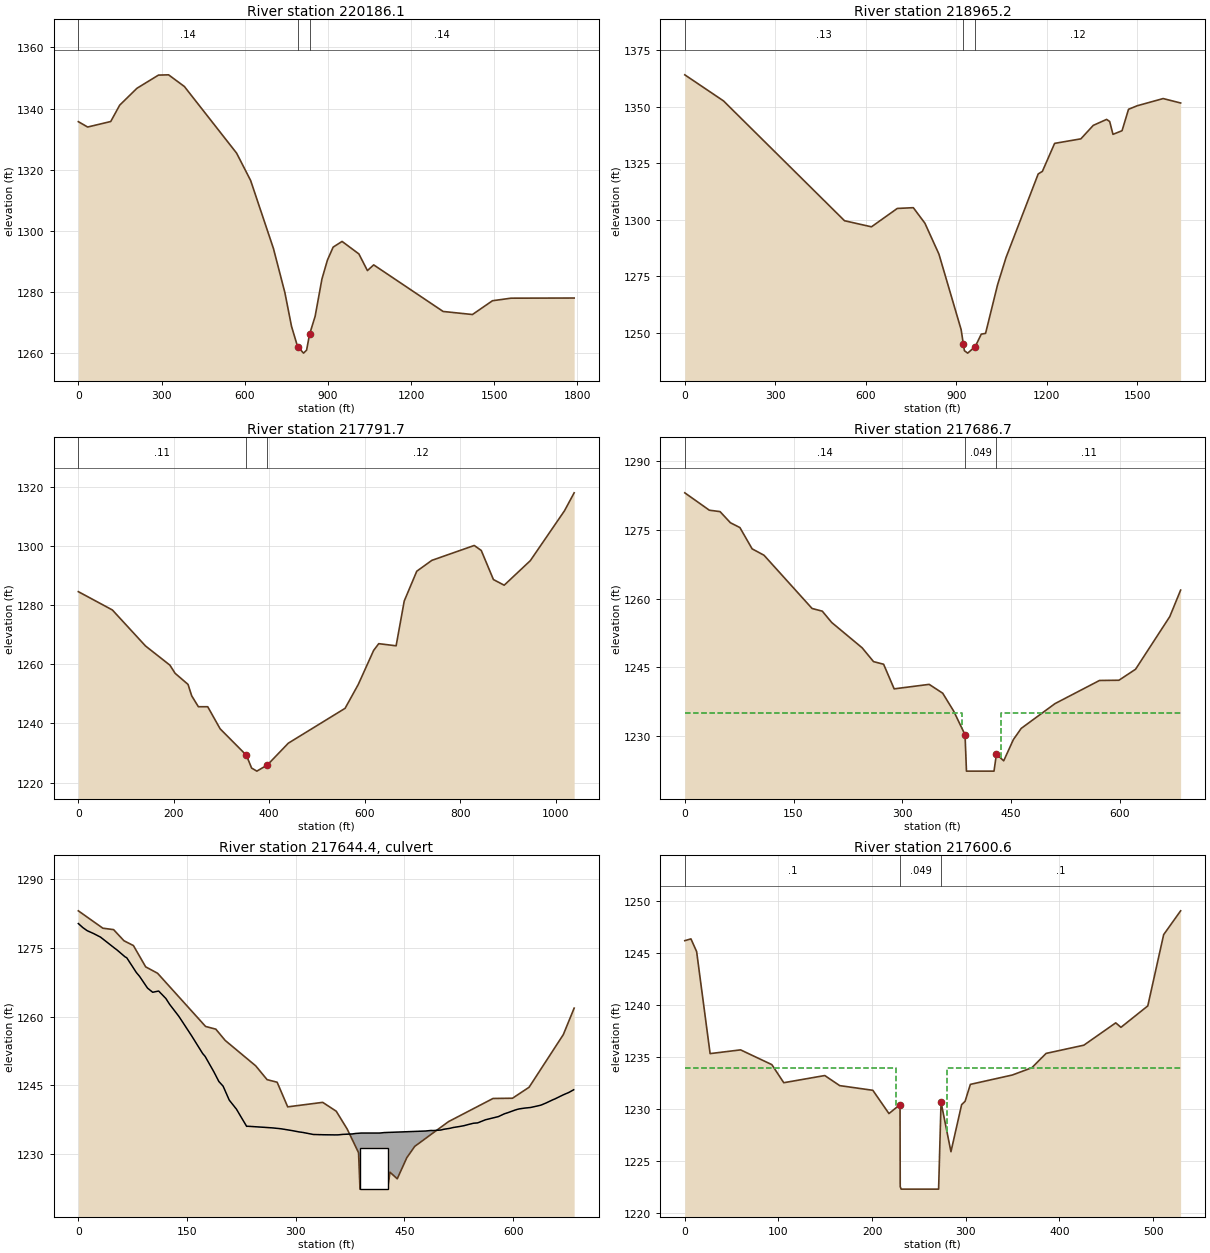
Type RM Length L Ch R = 1 ,220186.1,1206.1,1220.95,1235.14
BEGIN DESCRIPTION:
32918.1
END DESCRIPTION:
XS GIS Cut Line= 3
  1111411.736721   679151.663014   1110854.02052   678719.029359
  1110347.723066   677762.127198
#Sta/Elev= 30
       0 1335.72   33.61 1333.97  116.91 1335.77   149.1  1341.1  211.34 1346.62
  289.05 1350.93  325.51 1351.02  382.48 1347.21   570.9 1325.44  621.48 1316.51
   703.8 1294.28  745.05 1279.87  768.98 1268.86  790.83 1262.25  812.41 1260.11
  823.34 1261.09  834.18 1266.29  854.16 1272.14  878.72 1284.33  898.58 1290.53
  919.16 1294.74   951.3  1296.6 1011.95 1292.52 1042.76 1287.07 1065.35 1288.94
 1315.82 1273.72 1421.56 1272.72 1493.71 1277.22 1560.55 1278.06 1788.44 1278.11
#Mann= 3 , 0 , 0
       0     .14       0  790.83     .05       0  834.18     .14       0
Bank Sta=790.83,834.18
Exp/Cntr=0.3,0.1

Type RM Length L Ch R = 1 ,218965.2,1171.92,1173.44,1174.66
BEGIN DESCRIPTION:
31697.15
END DESCRIPTION:
XS GIS Cut Line= 3
  1111813.915221    679228.92734  1111946.928666   678704.698016
  1111939.104341   677601.469087
#Sta/Elev= 30
       0  1364.2  128.21 1352.66  529.67 1299.54  618.92 1296.85  704.62 1304.99
  757.74 1305.33  796.14 1298.46  842.77 1284.73  916.27 1251.31  923.85 1244.75
  927.18 1241.95  938.05 1240.88  963.04 1243.79  983.08 1249.29  997.31 1249.63
 1037.22 1271.23  1065.2 1283.25 1171.85 1320.28 1185.74 1321.43 1226.26 1333.82
 1313.26 1335.83 1354.42  1341.8 1398.69 1344.45  1408.9  1343.5  1419.8 1337.83
  1449.9 1339.44 1471.36 1348.93 1499.77 1350.48 1586.14 1353.68  1644.1 1351.72
#Mann= 3 , 0 , 0
       0     .13       0  923.85     .05       0  963.04     .12       0
Bank Sta=923.85,963.04
Exp/Cntr=0.3,0.1

Type RM Length L Ch R = 1 ,217791.7,112.33,105.02,97.04
BEGIN DESCRIPTION:
30523.71
END DESCRIPTION:
XS GIS Cut Line= 3
  1113074.760009   678620.529475  1113091.218201   678172.044729
  1113102.710801   677581.848923
#Sta/Elev= 30
       0 1284.55   71.35 1278.36   140.8 1266.18  191.88  1259.7  202.81 1256.94
  229.88 1253.19  237.63 1249.31  251.59 1245.64   271.2 1245.63  297.16 1238.17
  352.14 1229.24  363.15 1224.89  374.15 1223.86  396.12 1225.93  440.08 1233.31
  559.04  1245.1  586.58 1253.14  618.87 1264.68  629.55 1266.96     666 1266.24
  682.99 1281.39  709.26 1291.46  740.81 1295.13  829.71 1300.17   844.4 1298.48
  869.92 1288.64  892.46 1286.73  947.16 1295.02 1018.78 1311.89 1039.09 1317.97
#Mann= 3 , 0 , 0
       0     .11       0  352.14    .049       0  396.12     .12       0
Bank Sta=352.14,396.12
Exp/Cntr=0.5,0.3

Type RM Length L Ch R = 1 ,217686.7,86.73,86.14999,86.18
BEGIN DESCRIPTION:
30418.69
END DESCRIPTION:
XS GIS Cut Line= 5
  1113087.103642   678618.472196  1113200.253479   678270.793654
  1113185.852567   678202.903788  1113124.900988   678062.286626
  1113157.310936   677972.047001
#Sta/Elev= 30
       0 1283.08   33.85 1279.29   48.65 1278.98   62.96 1276.55   76.03  1275.5
    92.9 1270.86  109.33 1269.46   175.6 1257.85  189.73 1257.26  202.66  1254.8
  244.75 1249.26  260.44 1246.25  274.34 1245.68  288.89 1240.31   337.2 1241.29
  355.88 1239.36  371.01 1235.46  386.69  1230.3  388.66 1222.36  426.66 1222.36
  430.02 1226.05  440.06 1224.61  453.34 1229.23  464.18 1231.68  510.84 1237.09
  572.24 1242.14  599.07 1242.19     622 1244.59  669.23 1256.08  684.17 1261.85
#Mann= 3 , 0 , 0
       0     .14       0  386.69    .049       0  430.02     .11       0
#XS Ineff= 2 , 0
       0  382.18    1235  435.77       0    1235
Permanent Ineff=
       F       F
Bank Sta=386.69,430.02
Exp/Cntr=0.5,0.3

Type RM Length L Ch R = 2 ,217644.4,,,
BEGIN DESCRIPTION:
30376.4
END DESCRIPTION:
Bridge Culvert--1,0,-1,-1, 0
Deck Dist Width WeirC Skew NumUp NumDn MinLoCord MaxHiCord MaxSubmerge Is_Ogee
26,38,2.6,0, 85, 85, , , 0.95, 0, 0,0,,
       0    6.37   12.29   20.56   30.44   35.09    48.8   49.63   52.93   64.68
   66.77   80.04   84.59   95.43  102.58  110.82  120.75  125.96  138.64  141.27
  156.24  156.27  156.45  171.48  174.98  186.92  193.92  199.79  203.07  208.28
  218.07  232.27  233.74  264.36  268.75  279.56  294.59  304.23  309.69   324.4
  339.14  339.25  339.91  352.27  352.95  358.35  364.75  377.96   382.4  390.58
  402.78  416.17   422.1  479.12  486.51  489.59  499.98  505.04   512.2  517.79
  526.04  532.36  537.45   545.1  550.95  561.41  561.56  561.78  575.38  579.73
  587.94  592.33  602.44  605.93  608.64  615.96  624.01  637.25  639.51  645.45
  654.67  657.47  669.37  676.81  683.53
  1280.3  1279.4 1278.74 1278.16 1277.36 1276.79 1275.09 1274.98  1274.6 1273.01
 1272.85 1269.62 1268.76 1266.23 1265.31 1265.58 1263.96 1262.68 1260.07 1259.44
 1255.83 1255.82 1255.78 1251.96 1251.31 1247.98 1245.84 1244.82 1243.64 1241.77
 1239.83 1236.05 1236.08 1235.76 1235.71 1235.53 1235.14 1234.85 1234.73 1234.28
 1234.22 1234.22 1234.22  1234.2 1234.19  1234.2  1234.3  1234.4  1234.5  1234.6
  1234.6  1234.6  1234.7 1235.04 1235.16 1235.14 1235.25 1235.44 1235.61 1235.82
 1236.02 1236.21 1236.43 1236.73 1236.81 1237.47 1237.48 1237.49 1238.02 1238.19
  1238.8 1239.02  1239.6 1239.77 1239.87 1240.04 1240.17 1240.64 1240.76 1241.16
 1241.85 1242.03 1242.95 1243.45 1244.04
                                                                                
                                                                                
                                                                                
                                                                                
                                                                                
                                                                                
                                                                                
                                                                                
                                        
    -175 -168.63 -162.71 -154.44 -144.56 -139.91  -126.2 -125.37 -122.07 -110.32
 -108.23  -94.96  -90.41  -79.57  -72.42  -64.18  -54.25  -49.04  -36.36  -33.73
  -18.76  -18.73  -18.55   -3.52    -.02   11.92   18.92   24.79   28.07   33.28
   43.07   57.27   58.74   89.36   93.75  104.56  119.59  129.23  134.69   149.4
  164.14  164.25  164.91  177.27  177.95  183.35  189.75  202.96   207.4  215.58
  227.78  241.17   247.1  304.12  311.51  314.59  324.98  330.04   337.2  342.79
  351.04  357.36  362.45   370.1  375.95  386.41  386.56  386.78  400.38  404.73
  412.94  417.33  427.44  430.93  433.64  440.96  449.01  462.25  464.51  470.45
  479.67  482.47  494.37  501.81  508.53
  1280.3  1279.4 1278.74 1278.16 1277.36 1276.79 1275.09 1274.98  1274.6 1273.01
 1272.85 1269.62 1268.76 1266.23 1265.31 1265.58 1263.96 1262.68 1260.07 1259.44
 1255.83 1255.82 1255.78 1251.96 1251.31 1247.98 1245.84 1244.82 1243.64 1241.77
 1239.83 1236.05 1236.08 1235.76 1235.71 1235.53 1235.14 1234.85 1234.73 1234.28
 1234.22 1234.22 1234.22  1234.2 1234.19  1234.2  1234.3  1234.4  1234.5  1234.6
  1234.6  1234.6  1234.7 1235.04 1235.16 1235.14 1235.25 1235.44 1235.61 1235.82
 1236.02 1236.21 1236.43 1236.73 1236.81 1237.47 1237.48 1237.49 1238.02 1238.19
  1238.8 1239.02  1239.6 1239.77 1239.87 1240.04 1240.17 1240.64 1240.76 1241.16
 1241.85 1242.03 1242.95 1243.45 1244.04
                                                                                
                                                                                
                                                                                
                                                                                
                                                                                
                                                                                
                                                                                
                                                                                
                                        
BR Coef=-1 , 0 , 0 ,, 0 ,,,0.8,-1,1.2,0,
WSPro=,,,, 1 ,,,, 0 ,,,, 0 ,,,,-1 ,-1 ,-1 , 0 , 0 , 0 , 0 , 0
Culvert=2,9,38,49,0.013,0.2,1,8,1,1222.36,407.66,1222.3,251,Culvert #1  , 0 ,23
Culvert Bottom n=0.013
BC Design=,, 0 ,, 0 ,,,,,,

Type RM Length L Ch R = 1 ,217600.6,81.26,127.18,147.14
BEGIN DESCRIPTION:
30332.54
END DESCRIPTION:
XS GIS Cut Line= 6
  1113174.179472    678406.09694    1113253.4041   678350.213393
  1113282.544258   678244.049155  1113264.028832   678163.815655
  1113231.374684   678061.674995  1113278.429699   677937.516025
#Sta/Elev= 30
       0 1246.21    6.57 1246.38   12.63 1245.16   27.03 1235.34   59.56  1235.7
   92.93 1234.28  105.68 1232.54  149.45 1233.23  165.41 1232.26  200.77 1231.81
  217.97 1229.57  229.59 1230.42   229.8  1230.4     230 1222.54     231  1222.3
     271  1222.3   273.6 1230.66  284.17  1225.9  295.57 1230.43  299.26 1230.75
   304.9 1232.38  349.69 1233.28  370.52 1233.98  385.76 1235.36  426.05 1236.15
  460.12  1238.3  465.68 1237.87  494.33 1239.93  511.28 1246.79  529.39 1249.08
#Mann= 3 , 0 , 0
       0      .1       0  229.59    .049       0   273.6      .1       0
#XS Ineff= 2 , 0
       0     225    1234     280       0    1234
Permanent Ineff=
       F       F
Bank Sta=229.59,273.6
Exp/Cntr=0.5,0.3

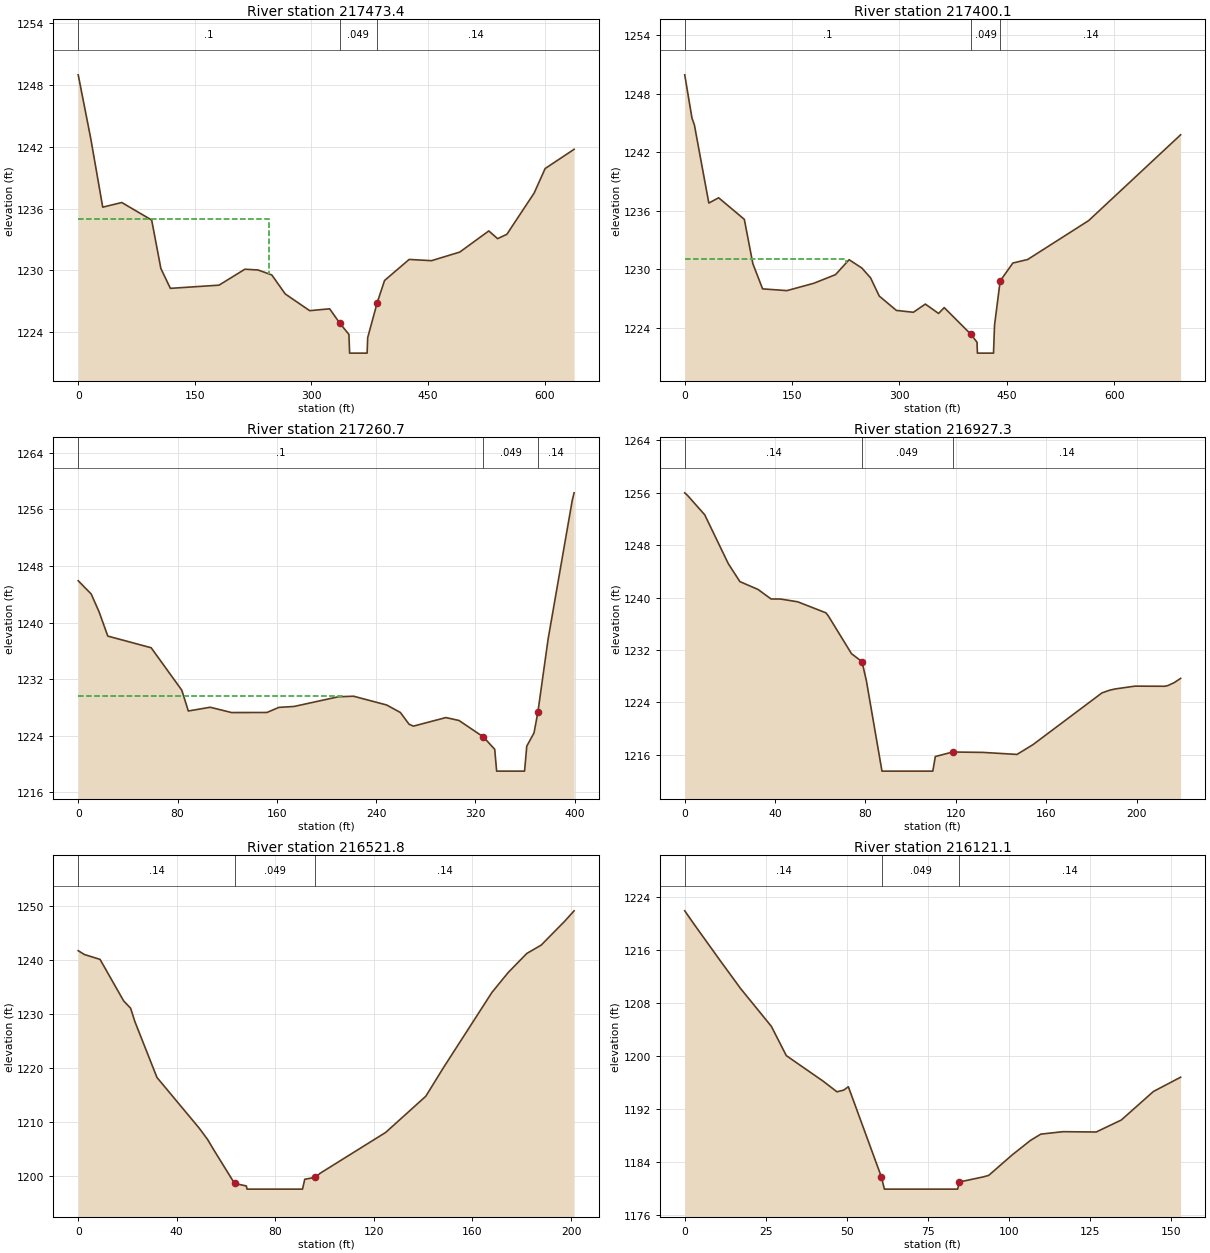
Type RM Length L Ch R = 1 ,217473.4,30.22,73.24,75.89
XS GIS Cut Line= 3
  1113170.796978   678439.921839   1113365.85608   678288.126645
  1113475.221118   677913.098903
#Sta/Elev= 30
       0 1248.94   16.15 1242.77   31.53 1236.13   56.05 1236.58   94.51 1234.88
  106.33 1230.19  118.54 1228.27  181.12 1228.58  214.31 1230.12  231.32 1230.05
  248.99 1229.57  266.26 1227.73  297.74 1226.11  323.41 1226.29  336.17 1224.93
  348.19 1223.81  349.09    1222  371.59    1222  372.34  1223.5  384.51 1226.87
  394.02 1229.03  425.68 1231.07  454.43 1230.95  490.71 1231.78  528.13 1233.83
  539.43 1233.08  551.32  1233.5  586.47  1237.5  600.58 1239.87  637.81 1241.73
#Mann= 3 , 0 , 0
       0      .1       0  336.17    .049       0  384.51     .14       0
#XS Ineff= 2 , 0
       0     246    1235               0
Permanent Ineff=
       F       F
Bank Sta=336.17,384.51
Exp/Cntr=0.3,0.1

Type RM Length L Ch R = 1 ,217400.1,27.16,139.45,174.62
XS GIS Cut Line= 4
   1113171.64259    678454.29743  1113427.390815   678272.282394
  1113504.024452   678095.555825  1113613.057643   677944.386921
#Sta/Elev= 30
       0 1249.96    10.1 1245.53    13.5 1244.82   33.66 1236.81    47.4 1237.35
   83.26 1235.14   95.16  1230.6  108.78 1228.01  142.77 1227.83  180.24 1228.58
  210.71 1229.47  229.66    1231  247.47 1230.15  259.67 1229.14  271.84 1227.27
  295.76  1225.8  319.43 1225.61  336.22 1226.45  354.69 1225.49  362.57 1226.09
  399.65 1223.37   408.4 1222.54  408.96 1221.42  431.46 1221.42   432.9 1224.29
  440.76 1228.82  458.51 1230.66  479.15 1231.02  564.41 1235.01  692.92 1243.81
#Mann= 3 , 0 , 0
       0      .1       0  399.65    .049       0  440.76     .14       0
#XS Ineff= 2 , 0
          225.39 1231.05
Permanent Ineff=
       F       F
Bank Sta=399.65,440.76
Exp/Cntr=0.3,0.1

Type RM Length L Ch R = 1 ,217260.7,162.46,333.4,323.08
XS GIS Cut Line= 3
  1113184.326911   678461.062374  1113438.013724   678288.555382
  1113530.727149   678290.428879
#Sta/Elev= 30
       0 1245.91   10.46 1244.04   16.84 1241.51   23.84 1238.09   58.78 1236.44
   83.46 1230.44   88.72  1227.5   106.3 1228.03  123.59 1227.28  152.06 1227.29
  161.64 1228.01  173.87 1228.14  209.58 1229.51  221.81 1229.59  248.49 1228.35
  259.57 1227.29  266.51 1225.64  270.05 1225.36  296.23 1226.57  306.78 1226.16
   326.4 1223.84  335.57 1222.09  337.12    1219  359.62    1219  361.39 1222.53
  367.23  1224.4  370.33 1227.31  378.56 1237.63  398.01 1257.25  399.52 1258.34
#Mann= 3 , 0 , 0
       0      .1       0   326.4    .049       0  370.33     .14       0
#XS Ineff= 2 , 0
          213.26 1229.59
Permanent Ineff=
       F       F
Bank Sta=326.4,370.33
Exp/Cntr=0.3,0.1

Type RM Length L Ch R = 1 ,216927.3,416.25,405.45,393.93
XS GIS Cut Line= 3
  1113175.025085   678507.571639    1113240.5049   678500.768045
  1113393.236555   678483.597514
#Sta/Elev= 29
       0    1256    1.28 1255.59    8.84 1252.65   19.28 1245.19   24.42 1242.44
   32.42 1241.25   38.23 1239.79   42.45 1239.78      50 1239.36   62.53 1237.67
   63.63 1237.17   73.82 1231.44   78.49 1230.21   80.43 1227.28   87.32  1213.5
  109.82  1213.5  110.94 1215.73  118.64 1216.42  131.99 1216.36  147.08 1216.05
  154.23 1217.56  184.73 1225.45  188.25 1225.87  190.56 1226.05  199.31 1226.48
  212.46 1226.46  213.86 1226.56  216.71 1227.02  219.53 1227.66
#Mann= 3 , 0 , 0
       0     .14       0   78.49    .049       0  118.64     .14       0
Bank Sta=78.49,118.64
Exp/Cntr=0.3,0.1

Type RM Length L Ch R = 1 ,216521.8,415.22,400.71,383.55
XS GIS Cut Line= 2
   1113421.00543   678862.223384  1113600.513347   678771.292076
#Sta/Elev= 29
       0 1241.71     2.5    1241    8.86  1240.1   18.43 1232.42   21.27 1231.05
   23.02 1228.55   31.96 1218.23   49.09 1208.85    52.5 1206.75   54.99 1204.84
   63.44 1198.61   68.22 1198.14   68.52 1197.55   74.23 1197.55   91.02 1197.55
   91.94 1199.38   95.81 1199.69   96.09 1199.71   96.35 1199.66   98.05 1200.45
   124.8 1208.06  141.05 1214.75  148.35 1220.14  167.89 1233.98  174.38 1237.61
  182.02 1241.19  187.87 1242.74  197.43 1247.17  201.23 1249.09
#Mann= 3 , 0 , 0
       0     .14       0   63.44    .049       0   96.09     .14       0
Bank Sta=63.44,96.09
Exp/Cntr=0.3,0.1

Type RM Length L Ch R = 1 ,216121.1,378.93,294.04,203.92
XS GIS Cut Line= 2
  1113721.031008   679188.441626  1113784.131603   679049.144038
#Sta/Elev= 27
       0 1221.84    2.84 1219.85   10.81 1214.41   17.21 1210.12   26.71 1204.41
   31.32 1199.99   42.69 1196.13   46.93 1194.53      49 1194.78   50.46 1195.29
   52.44 1192.65   60.66 1181.66   61.57 1179.84   61.66 1179.84    72.4 1179.84
   84.16 1179.84    84.7 1180.92      92 1181.68   93.73 1181.91  100.97    1185
  106.61 1187.19  109.81 1188.14  116.62 1188.51  126.88 1188.46  134.63 1190.27
  144.54 1194.58  152.92 1196.73
#Mann= 3 ,-1 , 0
       0     .14       0   60.93    .049       0    84.7     .14       0
Bank Sta=60.66,84.7
Exp/Cntr=0.3,0.1

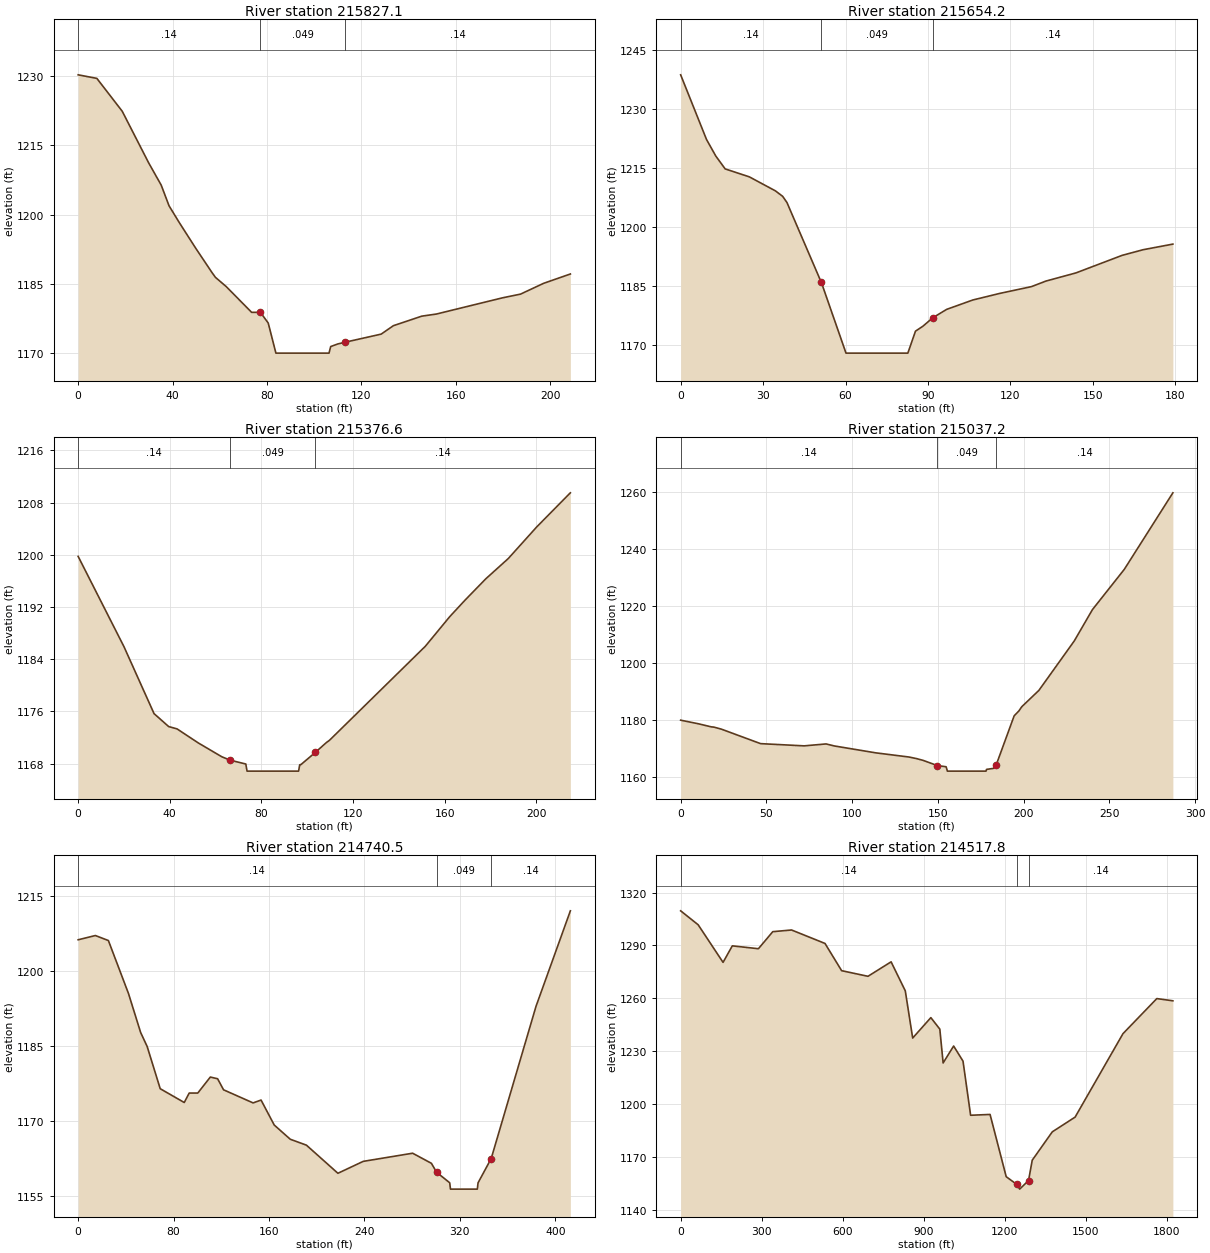
Type RM Length L Ch R = 1 ,215827.1,203.8,172.92,139.91
XS GIS Cut Line= 2
  1114114.961643   679144.194436  1113929.821018   679048.237387
#Sta/Elev= 27
       0  1230.2    7.93 1229.43   18.68 1222.32   29.87 1211.17   35.19 1206.35
    38.5 1201.89   42.89 1198.22   49.91 1192.63   56.72 1187.44   58.17 1186.41
   62.73 1184.42   73.49 1178.85   77.21 1178.85   80.53 1176.53   83.78 1170.03
  106.28 1170.03  106.99 1171.45  109.97 1172.01  112.85 1172.36  128.38 1174.14
  133.54 1175.96  145.56 1178.02  151.76 1178.48  179.74 1181.98  187.43 1182.79
  197.19 1185.12  208.53 1187.14
#Mann= 3 , 0 , 0
       0     .14       0   77.21    .049       0  112.85     .14       0
Bank Sta=77.21,112.85
Exp/Cntr=0.3,0.1

Type RM Length L Ch R = 1 ,215654.2,266.16,277.57,288.4
XS GIS Cut Line= 2
  1114017.875733   678919.542095  1113868.860109   679018.885859
#Sta/Elev= 24
       0 1238.58    9.41 1222.18   12.81 1217.96    16.2 1214.72      25  1212.7
   34.46 1209.16   37.12 1207.76   38.68 1206.19   51.07 1186.11   51.14 1186.05
   60.16    1168   82.66    1168   85.44 1173.57   88.17 1174.84   91.74 1176.97
    96.8  1179.1  106.28 1181.47  115.94 1183.12  127.65 1184.87  132.89 1186.27
  143.81 1188.34  160.61 1192.79  168.22 1194.22  179.09 1195.65
#Mann= 3 , 0 , 0
       0     .14       0   51.07    .049       0   91.74     .14       0
Bank Sta=51.07,91.74
Exp/Cntr=0.3,0.1

Type RM Length L Ch R = 1 ,215376.6,305.34,339.4,373.09
XS GIS Cut Line= 2
  1113978.195739   678676.493252  1113768.654073   678724.116361
#Sta/Elev= 30
       0 1199.75      20 1185.92   33.14 1175.66   39.51 1173.68   43.18 1173.32
   52.45 1171.17   62.71 1169.05   66.43 1168.52   73.19 1167.94   73.74 1166.85
   85.93 1166.85   96.24 1166.85   96.72 1167.81   97.03 1167.84   97.32 1167.87
  103.55 1169.72  108.38 1171.23  108.69 1171.31  109.54 1171.52  110.21 1171.74
  151.54 1185.97  153.99 1187.01  162.23 1190.52  168.97 1193.07  178.01 1196.33
  187.78 1199.42   199.7 1204.07  200.02  1204.2  214.39 1209.32  214.89 1209.49
#Mann= 3 , 0 , 0
       0     .14       0   66.43    .049       0  103.55     .14       0
Bank Sta=66.43,103.55
Exp/Cntr=0.3,0.1

Type RM Length L Ch R = 1 ,215037.2,279.18,296.65,311.78
XS GIS Cut Line= 2
  1114049.035098   678503.115414  1113870.448492   678278.393905
#Sta/Elev= 28
       0 1179.94   10.45 1178.66    17.8  1177.6    19.4  1177.5    23.8 1176.78
   46.62  1171.7   72.07 1170.92   84.81  1171.6   89.52  1170.9  113.77 1168.47
  133.18    1167  137.77 1166.42  141.52  1165.8  149.61 1164.02   154.8 1163.58
  155.57 1162.05  178.07 1162.05  178.38 1162.66  183.28  1163.1  184.02 1164.24
  194.49 1181.47  197.26 1183.19  198.94 1184.67   208.9 1190.39  229.55 1207.77
  240.14 1218.76  258.72  1232.9  287.04 1259.76
#Mann= 3 , 0 , 0
       0     .14       0  149.61    .049       0  184.02     .14       0
Bank Sta=149.61,184.02
Exp/Cntr=0.3,0.1

Type RM Length L Ch R = 1 ,214740.5,236.87,222.79,208.46
XS GIS Cut Line= 3
  1114352.632373   678622.173166  1114233.574621   678480.792088
  1114196.369093   678256.070579
#Sta/Elev= 30
       0 1206.29   14.44 1207.14   25.35 1206.14   42.19 1195.55   52.39 1187.75
   57.85 1184.95   68.79 1176.51   88.94 1173.75   93.09 1175.64  100.28 1175.64
   110.8 1178.84   116.9  1178.5  121.89 1176.29  146.64 1173.67  153.33 1174.24
  164.36 1169.25  177.84  1166.4  191.37 1165.22  217.75  1159.6  238.96 1161.98
  280.38 1163.61  296.14 1161.59  300.45 1159.81  311.46  1157.7   312.1 1156.43
   334.6 1156.43  335.23 1157.69  346.25 1162.55  383.83    1193  412.61 1212.08
#Mann= 3 , 0 , 0
       0     .14       0  300.45    .049       0  346.25     .14       0
Bank Sta=300.45,346.25
Exp/Cntr=0.3,0.1

Type RM Length L Ch R = 1 ,214517.8,442.12,438.76,435.4
BEGIN DESCRIPTION:
27249.74
END DESCRIPTION:
XS GIS Cut Line= 3
  1115175.119686   679306.059239  1114491.745069   678393.161046
  1114082.132242   677847.244193
#Sta/Elev= 30
       0 1309.65   64.85 1301.73  157.04 1280.39  191.28 1289.76  287.98 1288.14
  341.19 1297.82  410.81 1298.77  534.59 1291.13  596.13 1275.67  693.74 1272.48
  779.34 1280.69  831.88 1264.23  859.26 1237.43  926.56 1249.02  959.77 1242.48
  972.05 1223.28 1010.92  1232.9 1045.68 1224.31 1073.81  1193.6 1145.88 1194.05
 1205.61 1158.71 1245.05 1154.31 1255.44 1151.66 1288.32 1156.53 1302.02 1168.08
 1376.24 1184.17 1460.81 1192.55 1638.08 1239.92 1763.34 1259.83 1822.84 1258.57
#Mann= 3 , 0 , 0
       0     .14       0 1245.05    .049       0 1288.32     .14       0
Bank Sta=1245.05,1288.32
Exp/Cntr=0.3,0.1