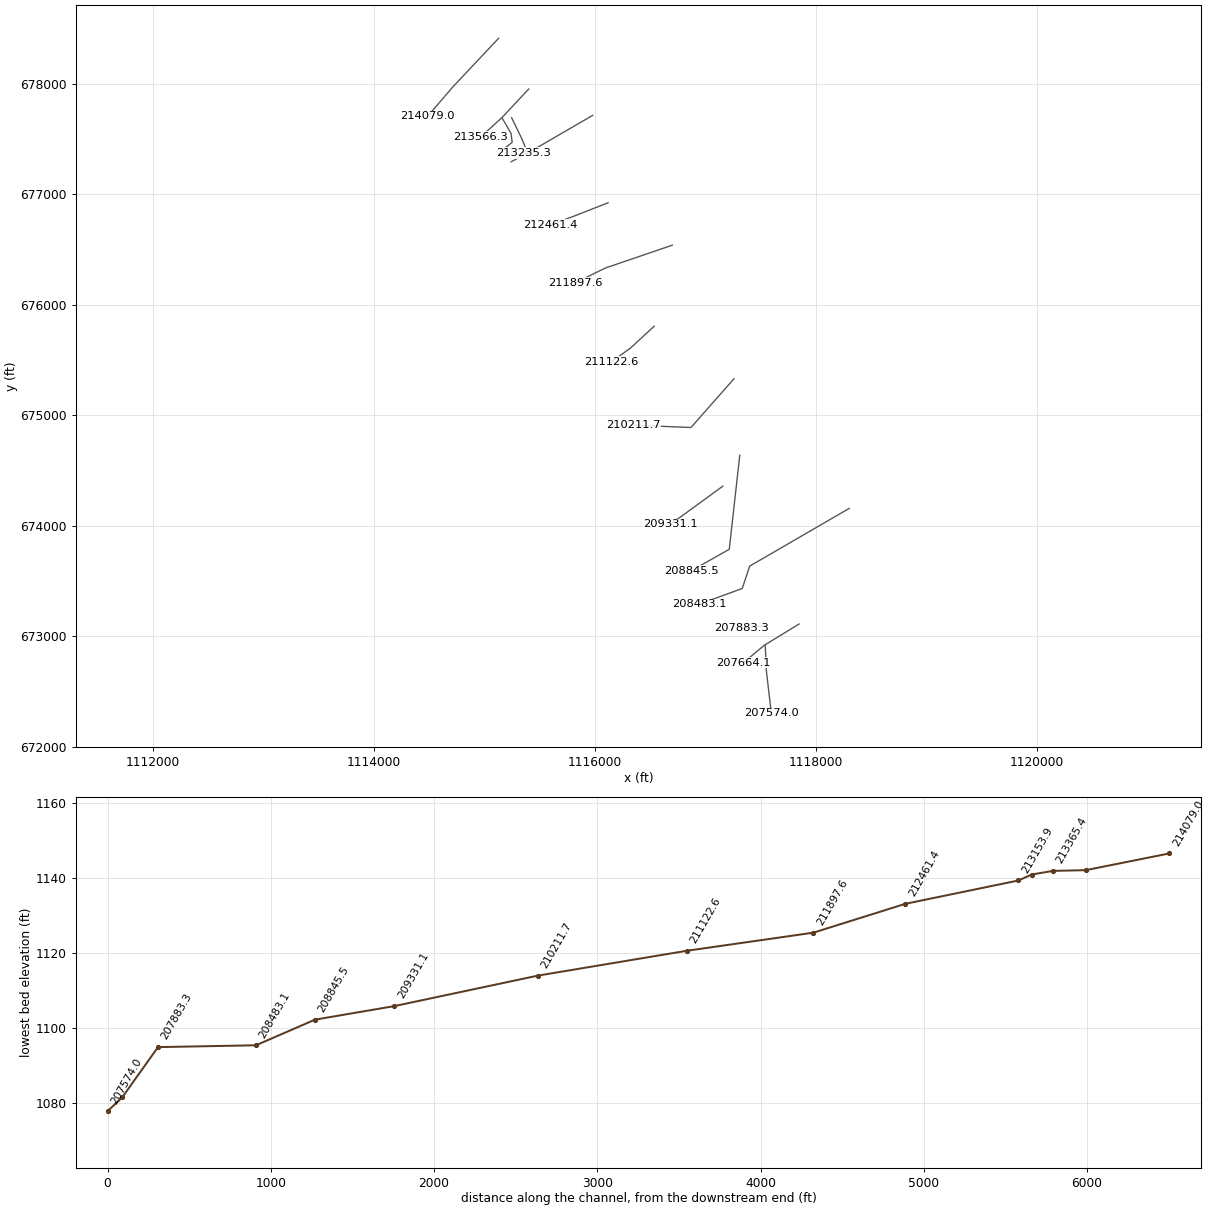
HEC-RAS study 2ndBroadRv.prj: 2ndBroadRv

--- 2ndBroadRv.g01 (geometry) --- (continued)

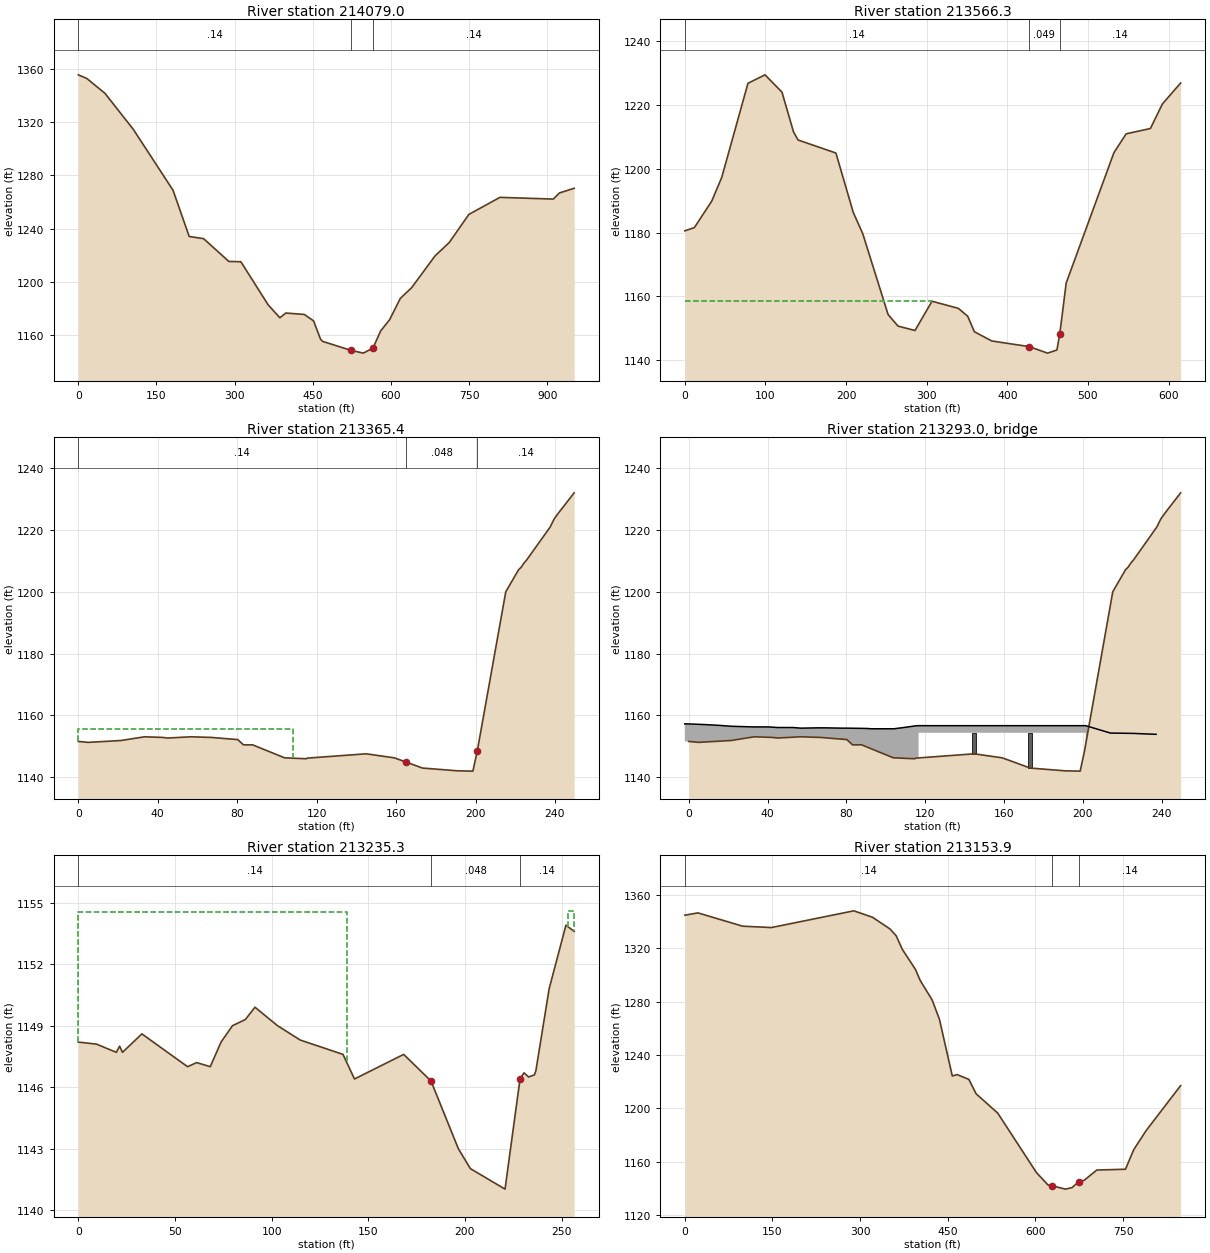
Type RM Length L Ch R = 1 ,214079.0,514.92,512.7,510.41
BEGIN DESCRIPTION:
26810.98
END DESCRIPTION:
XS GIS Cut Line= 3
  1115127.438381   678408.693617  1114714.476068   677970.447867
  1114486.925366   677704.972101
#Sta/Elev= 30
       0  1355.4   16.31 1352.66   51.04 1341.56  105.34 1314.61  181.76 1268.86
   212.9 1234.14  240.47 1232.53  288.96 1215.42  312.04  1215.2  364.36  1182.9
  386.97 1173.17  398.14 1176.72  433.79 1175.69  451.63 1170.84     465 1157.06
  469.19 1155.43  524.19 1148.65  547.23 1146.66  565.83 1150.56  580.23 1163.26
  597.56 1171.72  618.05 1187.67  640.04 1195.84   684.9 1219.66  712.04 1229.62
  749.65 1250.69  809.34  1263.5  911.69  1262.2  923.57  1266.8  951.81 1270.31
#Mann= 3 , 0 , 0
       0     .14       0  524.19    .049       0  565.83     .14       0
Bank Sta=524.19,565.83
Exp/Cntr=0.3,0.1

Type RM Length L Ch R = 1 ,213566.3,168.76,200.89,232.93
BEGIN DESCRIPTION:
26298.28
END DESCRIPTION:
XS GIS Cut Line= 3
  1115399.558747   677949.828561  1115159.147894   677692.837661
  1114964.781764   677515.666762
#Sta/Elev= 30
       0 1180.55   11.85 1181.55   33.46 1189.89   45.88 1197.35   78.35 1226.83
   99.51 1229.48  120.52 1224.05  134.78 1211.63   140.4 1209.05  187.43 1204.95
  208.91 1186.34   220.7 1179.65  252.13 1154.29  264.43 1150.67   285.5 1149.29
   306.6 1158.47  339.26 1156.23  350.84 1153.77  359.16 1148.89  380.77    1146
  426.92 1144.24  449.97 1142.19   461.5 1143.17  465.03 1148.19  473.02  1164.2
  532.19 1205.06  547.41 1210.98  577.44 1212.64   592.3 1220.34  614.91 1226.91
#Mann= 3 , 0 , 0
       0     .14       0  426.92    .049       0  465.03     .14       0
#XS Ineff= 2 , 0
           306.5 1158.45
Permanent Ineff=
       F       F
Bank Sta=426.92,465.03
Exp/Cntr=0.5,0.3

Type RM Length L Ch R = 1 ,213365.4,111.49,130.14,154.42
BEGIN DESCRIPTION:
26097.39  Upstream xs of Bridge 37111-0370
END DESCRIPTION:
XS GIS Cut Line= 5
  1115159.346115   677687.549818  1115197.768818   677622.426594
  1115239.830477   677548.725524  1115250.548454   677467.853384
  1115163.273382   677399.160818
#Sta/Elev= 30
       0  1151.6    5.02  1151.3  21.496  1151.9  33.305  1153.1  42.497  1152.9
  44.972  1152.7  56.639  1153.1  66.822  1152.9  80.257  1152.2  83.156  1150.5
  87.752  1150.5 103.874  1146.3 114.834    1146 115.258  1146.2 144.957  1147.6
 159.099  1146.3 165.0811144.925 173.241    1143 190.919  1142.1 198.697    1142
 200.903 1148.53 215.243    1200 221.678  1207.1 222.951  1207.9 224.436  1209.3
 225.779  1210.3 237.659    1221 239.568  1223.5 241.689  1225.4 249.679    1232
#Mann= 3 , 0 , 0
       0     .14       0 165.081    .048       0 200.903     .14       0
#XS Ineff= 2 , 0
       0  108.14  1155.7  220.28       0 1156.21
Permanent Ineff=
       F       F
Bank Sta=165.081,200.903
Skew Angle= 45
Exp/Cntr=0.5,0.3

Type RM Length L Ch R = 3 ,213293.0,,,
BEGIN DESCRIPTION:
26025.02  Bridge : 37111-0370
END DESCRIPTION:
Bridge Culvert--1,0,-1,-1, 0
Deck Dist Width WeirC Skew NumUp NumDn MinLoCord MaxHiCord MaxSubmerge Is_Ogee
54.9,35,2.6,45, 35, 26, , , 0.95, 0, 0,0,,
   -1.98  -1.909   2.828    9.97  15.486  21.708  27.294  32.668  35.638  40.447
  45.255  52.962  56.993  65.549  68.801  77.994   80.61   90.58  92.419 103.167
 104.228 109.107 113.561 115.753 116.107 116.673 116.673 201.525 201.525 214.112
 215.597 225.638 229.385 237.022 237.234
  1157.3  1157.3  1157.2    1157  1156.8  1156.5  1156.4  1156.3  1156.3  1156.3
  1156.1  1156.1  1155.9    1156    1156  1155.9  1155.9  1155.8  1155.7  1155.7
  1155.7  1156.1  1156.5  1156.7  1156.7  1156.7  1156.7  1156.7  1156.7  1154.3
  1154.3  1154.2  1154.1  1153.9  1153.9
                                                                                
                                                                                
                                                  1154.4  1154.4
                                        
       0  32.173  32.244  36.982  44.123  49.639  55.861  61.448  66.822  69.791
    74.6  79.408  87.116  91.146  99.702 102.955 149.907 150.189 152.028 152.028
 236.881 236.881  259.72 263.539 271.105 271.388
  1157.3  1157.3  1157.3  1157.2    1157  1156.8  1156.5  1156.4  1156.3  1156.3
  1156.3  1156.1  1156.1  1155.9    1156    1156  1156.7  1156.7  1156.7  1156.7
  1156.7  1156.7  1154.2  1154.1  1153.9  1153.9
                                                                                
                                                                          1154.4
  1154.4
Pier Skew= 45
Pier Skew, UpSta & Num, DnSta & Num=  ,144.957, 2 ,180.312, 2 , 0 , 0 , 0 ,,
       2       2
  1146.6  1154.9
       2       2
  1146.6  1154.9
Pier Skew, UpSta & Num, DnSta & Num=  ,173.241, 2 ,208.596, 2 , 0 , 0 , 0 ,,
       2       2
    1142  1154.9
       2       2
    1142  1154.9
BR Coef=-1 , 1 , 0 ,, 0 ,,,0.8,0,1.2,0,
WSPro=,,,, 1 ,,,, 0 ,,,, 0 ,,,,-1 ,-1 ,-1 , 0 , 0 , 0 , 0 , 0
BC Design=,, 0 ,, 0 ,,,,,,

Type RM Length L Ch R = 1 ,213235.3,139.28,81.38,17.51
BEGIN DESCRIPTION:
25967.26  Down stream xs of Bridge 37111-0370
END DESCRIPTION:
XS GIS Cut Line= 5
  1115245.308766    677690.80597   1115336.77956   677501.956112
  1115371.856597   677417.186513  1115379.493142   677386.129679
  1115354.411569   677371.216335
#Sta/Elev= 30
       0  1148.2   9.405  1148.1  19.658  1147.7  21.355    1148   22.84  1147.7
   32.88  1148.6  56.498    1147  61.235  1147.2  68.236    1147  73.822  1148.2
  79.762    1149  86.408  1149.3  91.358  1149.9 103.025    1149 114.763  1148.3
 136.896  1147.6 142.836  1146.4 168.291  1147.6 182.434  1146.3 196.576    1143
 202.791 1142.03 220.716 1141.03 228.4731146.401 230.517  1146.7 232.921  1146.5
 235.891  1146.6 236.669  1146.8 243.528  1150.8 252.225  1153.9 256.468  1153.6
#Mann= 3 , 0 , 0
       0     .14       0 182.434    .048       0 228.473     .14       0
#XS Ineff= 2 , 0
       0  138.76 1154.53 253.286       0  1154.6
Permanent Ineff=
       F       F
Bank Sta=182.434,228.473
Skew Angle= 45
Exp/Cntr=0.5,0.3

Type RM Length L Ch R = 1 ,213153.9,696.95,692.48,687.9
BEGIN DESCRIPTION:
25885.88
END DESCRIPTION:
XS GIS Cut Line= 3
  1115978.354222   677711.657126  1115435.357275    677396.63602
  1115241.213709   677292.009743
#Sta/Elev= 30
       0 1344.87   22.41 1346.64   98.99 1336.66  148.14 1335.63  289.15 1348.18
  321.24 1343.34   351.3  1334.5  361.76 1329.39   372.1 1319.33  394.45 1304.36
  402.58  1296.1  423.21 1281.28  435.69 1266.78  457.66  1224.3  465.86 1225.36
  486.02 1221.74  498.36 1210.97  535.36 1196.48  601.76 1151.78  621.66 1142.47
  629.08 1141.84  651.36 1139.44  662.53 1140.57  674.06 1145.03  683.25 1146.05
  704.84 1153.76  753.95 1154.36  767.95 1168.92  788.93 1183.13   848.3 1217.09
#Mann= 3 , 0 , 0
       0     .14       0  629.08    .048       0  674.06     .14       0
Bank Sta=629.08,674.06
Exp/Cntr=0.3,0.1

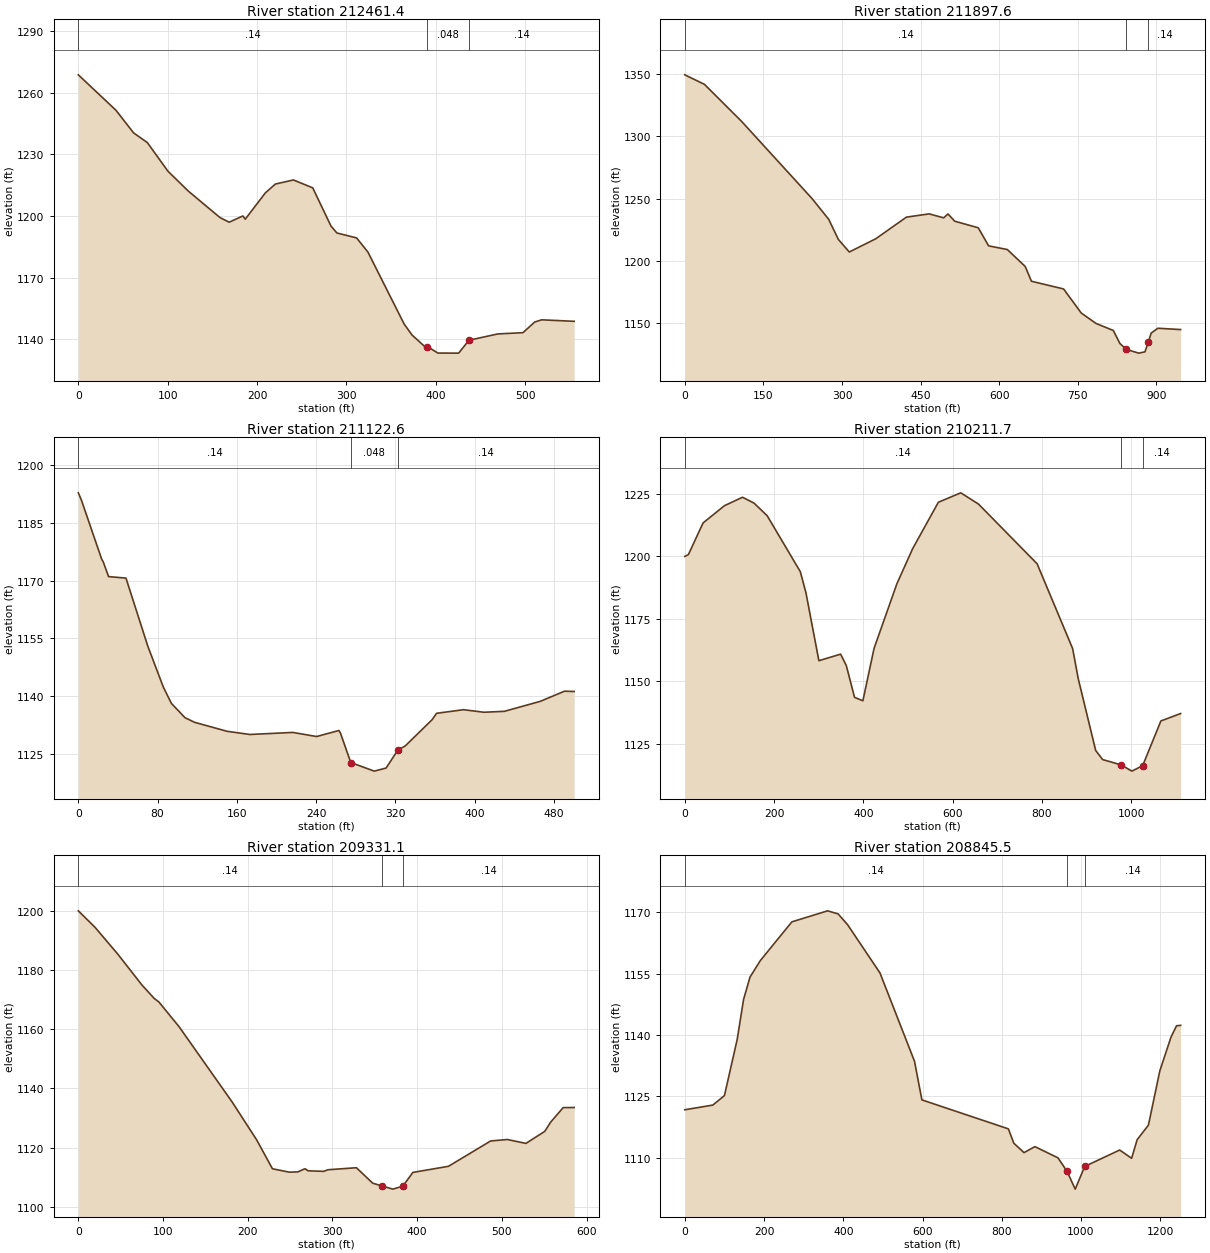
Type RM Length L Ch R = 1 ,212461.4,560.72,563.85,566.96
BEGIN DESCRIPTION:
25193.39
END DESCRIPTION:
XS GIS Cut Line= 3
  1116117.705208    676921.18643  1115805.876505   676798.983275
  1115599.395349   676723.133056
#Sta/Elev= 30
       0 1268.73   42.17 1251.46   61.81 1240.47   77.18 1235.77  100.27 1221.81
  123.15 1212.09  158.56 1199.22  168.85 1196.97  184.08 1200.02   186.8 1198.44
  209.31 1211.25  220.53 1215.55  240.75 1217.54  262.36 1213.69  282.67 1195.16
  289.32 1191.73  311.39 1189.33  324.05 1182.46  364.66 1147.36  373.51 1142.02
  388.44 1136.13  390.76 1136.38  402.39 1133.25  425.63 1133.22  437.25  1139.5
  469.41 1142.56   497.6 1143.18  510.78 1148.38  518.59 1149.44  554.89 1148.71
#Mann= 3 , 0 , 0
       0     .14       0  390.76    .048       0  437.25     .14       0
Bank Sta=390.76,437.25
Exp/Cntr=0.3,0.1

Type RM Length L Ch R = 1 ,211897.6,767.06,775.01,780.07
BEGIN DESCRIPTION:
24629.55
END DESCRIPTION:
XS GIS Cut Line= 3
  1116699.223613     676537.7214  1116094.264794   676331.323405
  1115818.518179    676196.39537
#Sta/Elev= 30
       0 1349.61   37.48 1341.96  108.54 1312.05  243.01 1249.89  274.66 1233.25
  293.08 1217.06  313.86 1206.95  364.41  1217.6  422.91 1235.02  466.41 1237.64
  493.97 1234.46  502.22 1237.58  515.13 1231.74  560.01 1226.46  579.76  1211.9
  615.48 1208.93  649.69 1195.26  661.49  1183.4  722.88 1177.19  756.58 1157.79
  784.91 1149.39  817.71 1143.76  830.31 1133.29  842.52 1128.52  866.27 1125.52
  878.15 1126.54  884.66 1134.64  890.04 1141.68  902.73 1145.56  946.19 1144.49
#Mann= 3 , 0 , 0
       0     .14       0  842.52    .048       0  884.66     .14       0
Bank Sta=842.52,884.66
Exp/Cntr=0.3,0.1

Type RM Length L Ch R = 1 ,211122.6,932.72,910.83,889.94
BEGIN DESCRIPTION:
23854.54
END DESCRIPTION:
XS GIS Cut Line= 3
  1116534.881457   675804.502557  1116319.972474   675606.449182
  1116151.416426   675484.246027
#Sta/Elev= 30
       0 1192.68    3.16 1190.77   23.69 1175.43    25.1 1174.86   30.52 1171.01
   48.09 1170.62   70.19 1152.97    85.7 1142.49   93.91 1138.22  107.65 1134.52
   117.3 1133.32  150.19 1130.99  173.19 1130.17  216.52  1130.7  240.48 1129.64
  263.04  1131.2  264.63 1130.49  274.97 1122.92  298.67 1120.69  310.65 1121.49
  322.63  1126.2  329.75 1127.16  357.03 1133.98  361.63 1135.65  388.83 1136.58
  409.43 1135.92  430.03 1136.16  466.24 1138.74  490.75 1141.37  500.45 1141.29
#Mann= 3 , 0 , 0
       0     .14       0  274.97    .048       0  322.63     .14       0
Bank Sta=274.97,322.63
Exp/Cntr=0.3,0.1

Type RM Length L Ch R = 1 ,210211.7,875,880.64,885
BEGIN DESCRIPTION:
22943.71
END DESCRIPTION:
XS GIS Cut Line= 4
  1117256.330894   675328.782869  1116867.735725   674888.375044
  1116454.106695   674905.241092  1116345.255865   674911.155449
#Sta/Elev= 30
       0 1199.91    8.03 1200.62   40.94 1213.28   88.72 1220.17   129.2 1223.55
  154.95 1221.22  184.43 1216.18  258.68 1193.81  271.34 1185.34  300.29 1158.22
  348.96 1160.84  361.67 1156.28  380.14 1143.57  398.81 1142.21  423.87 1163.17
  474.91 1188.95  510.19 1202.97  567.82 1221.55  617.99 1225.32  657.81 1220.81
  788.99 1196.95  868.46 1163.09   881.1 1151.01  920.09 1122.35  935.76  1118.7
  976.56  1116.6 1001.31 1114.08 1025.37 1116.28 1066.15 1134.14 1110.32  1137.1
#Mann= 3 , 0 , 0
       0     .14       0  976.56    .047       0 1025.37     .14       0
Bank Sta=976.56,1025.37
Exp/Cntr=0.3,0.1

Type RM Length L Ch R = 1 ,209331.1,488.91,485.63,482.34
BEGIN DESCRIPTION:
22063.07
END DESCRIPTION:
XS GIS Cut Line= 3
  1117155.883635   674357.621864  1116879.784426   674156.361781
  1116682.368004    674013.59445
#Sta/Elev= 30
       0 1199.94   19.62  1194.4   46.57 1185.32   74.97 1174.93   89.57 1170.35
   95.08 1169.16  119.04 1160.76  181.62 1135.35  210.53 1122.57  229.14 1112.82
  249.04 1111.67   259.2 1111.76  267.47 1112.83  271.31 1112.13  289.58 1111.94
  294.58 1112.48  328.24 1113.17  347.55 1107.94  358.42 1107.02  371.23 1105.94
  383.06 1106.94   394.9 1111.58  436.95 1113.65  486.75 1122.21  506.43  1122.7
  528.35 1121.39  550.52 1125.43   557.6 1128.58  572.33 1133.47   585.3 1133.51
#Mann= 3 , 0 , 0
       0     .14       0  358.42    .047       0  383.06     .14       0
Bank Sta=358.42,383.06
Exp/Cntr=0.3,0.1

Type RM Length L Ch R = 1 ,208845.5,339.91,362.38,384.34
BEGIN DESCRIPTION:
21577.44
END DESCRIPTION:
XS GIS Cut Line= 3
  1117309.132697   674637.775349  1117214.077368   673786.803667
  1116870.067545   673592.166505
#Sta/Elev= 30
       0 1121.73    70.8 1122.88  100.04  1125.2  132.29 1138.94  148.31 1148.69
  164.59 1154.16  190.84 1158.23  270.24 1167.67  360.45 1170.37  386.99 1169.62
  410.94 1166.98  492.62 1155.19  579.86 1133.58  598.45 1124.15  816.84 1117.06
  830.42 1113.56  856.26 1111.25  883.69 1112.72   941.9 1109.98  964.44 1106.75
  985.47 1102.33 1009.46 1107.88 1097.69 1111.89 1127.86 1109.87 1141.81 1114.42
  1170.3 1117.98 1198.94 1131.22 1227.14 1139.47 1241.22 1142.27 1251.52 1142.37
#Mann= 3 , 0 , 0
       0     .14       0  964.44    .047       0 1009.46     .14       0
Bank Sta=964.44,1009.46
Exp/Cntr=0.3,0.1

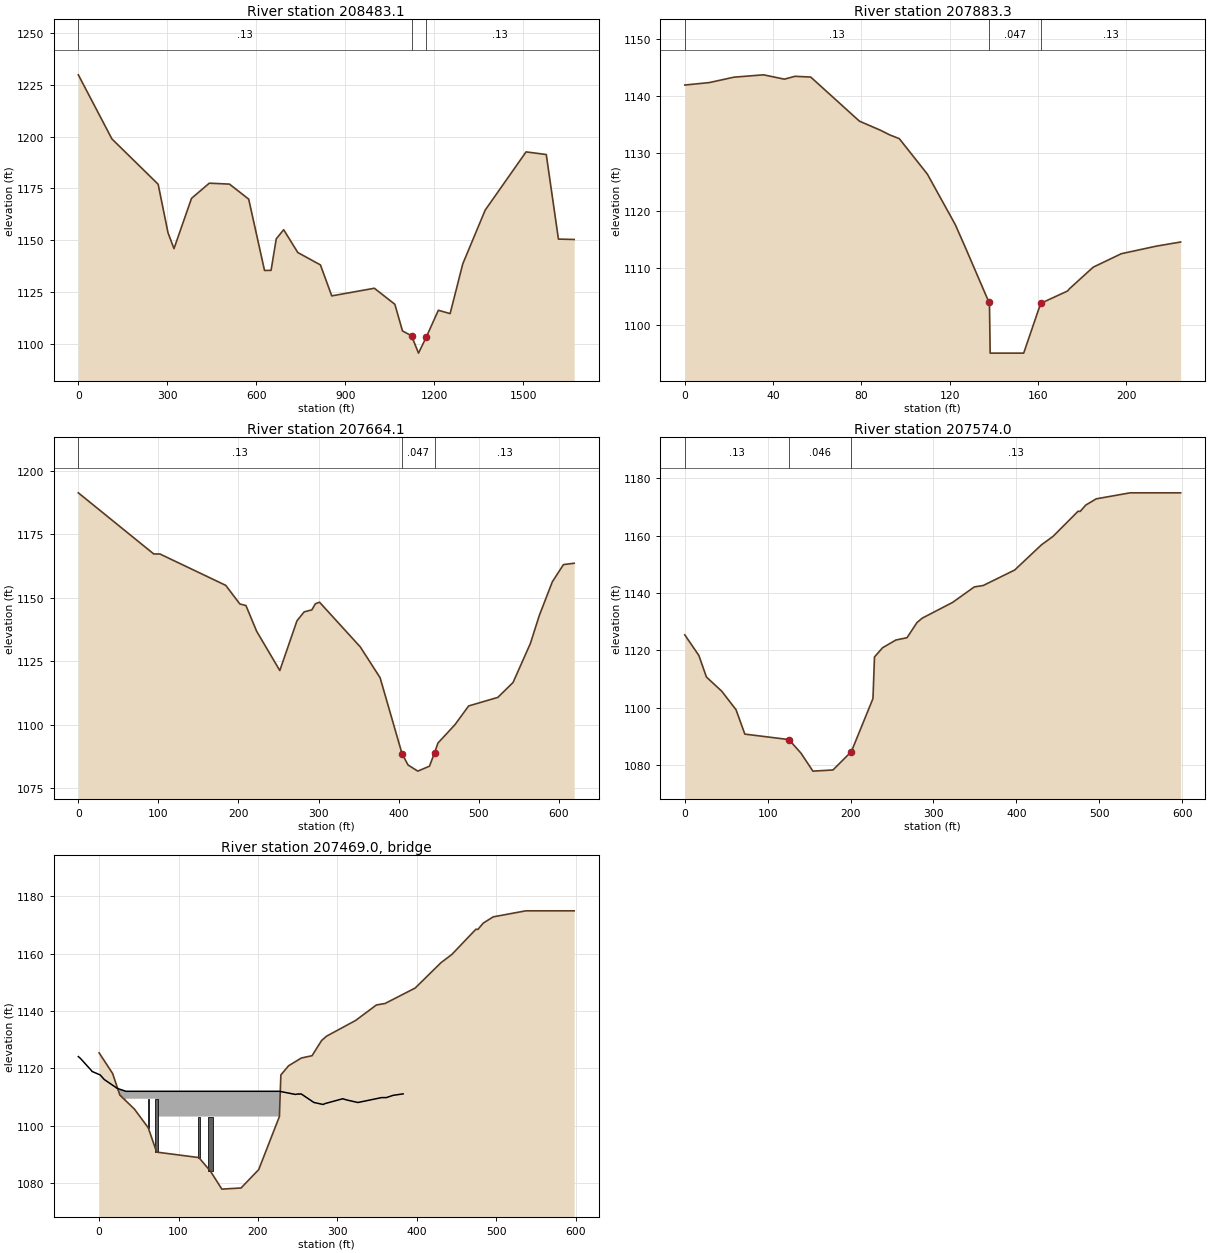
Type RM Length L Ch R = 1 ,208483.1,615.56,599.74,582.37
BEGIN DESCRIPTION:
21215.05
END DESCRIPTION:
XS GIS Cut Line= 4
   1118299.06119   674156.520864  1117398.731238   673634.343355
  1117331.308801   673432.076089  1116939.415988   673288.803433
#Sta/Elev= 30
       0  1229.8  113.22 1198.87  269.08 1176.99  302.31 1153.57   322.4 1145.92
  381.53 1170.19  441.55 1177.51  509.52 1177.06  574.29  1169.8  627.61 1135.39
  649.62 1135.43  667.13 1150.65  692.16 1155.04  739.84 1144.03  816.07 1138.06
  854.21 1123.12  997.81  1126.8 1066.96 1119.06  1092.6 1106.21 1123.18 1103.86
 1146.63 1095.49 1172.54 1103.15 1213.56 1116.17 1253.18 1114.56 1295.84 1138.57
 1371.37 1164.51 1509.17 1192.61 1577.29 1191.34 1618.27 1150.52 1671.27 1150.34
#Mann= 3 , 0 , 0
       0     .13       0 1123.18    .047       0 1172.54     .13       0
Bank Sta=1123.18,1172.54
Exp/Cntr=0.3,0.1

Type RM Length L Ch R = 1 ,207883.3,200.63,219.24,237.46
XS GIS Cut Line= 2
   1117552.87349    673093.95539  1117329.095416   673074.282583
#Sta/Elev= 25
       0    1142   11.07 1142.43   22.32 1143.38   35.69 1143.79   45.12 1143.03
    49.9 1143.53   57.05  1143.4   79.11 1135.67   88.69 1134.07   92.86 1133.26
   97.18  1132.6  109.89 1126.39  122.56 1117.52  127.13 1113.51  137.83 1103.89
  138.03 1103.81  138.35    1095  153.54    1095  161.24 1103.72  173.46  1105.9
   174.2 1106.26     185 1110.06  197.77 1112.43  213.82 1113.77  224.64 1114.48
#Mann= 3 , 0 , 0
       0     .13       0  137.83    .047       0  161.24     .13       0
Bank Sta=137.83,161.24
Exp/Cntr=0.3,0.1

Type RM Length L Ch R = 1 ,207664.1,49.24,90.1,130.95
BEGIN DESCRIPTION:
20396.07
END DESCRIPTION:
XS GIS Cut Line= 4
  1117845.506723   673110.955422  1117529.464084   672917.115983
  1117427.883834   672832.311201  1117337.712178   672759.199016
#Sta/Elev= 30
       0 1191.42   94.18  1167.3  101.91 1167.29   184.1 1154.91  201.69 1147.57
  209.32 1146.95   222.7 1136.79   251.6  1121.3  273.02 1140.92     282 1144.45
  291.62 1145.24  296.04 1147.65  301.24 1148.26  352.16  1130.6  376.83 1118.47
  404.25 1088.47  411.71 1084.05  423.88 1081.61   438.5 1083.56  444.93 1088.91
  449.09 1092.69  470.27 1099.92  487.43 1107.33  523.86 1110.71  542.85 1116.58
  564.53    1132  575.66 1143.04  591.96 1156.34  605.82  1163.1  619.17 1163.64
#Mann= 3 , 0 , 0
       0     .13       0  404.25    .047       0  444.93     .13       0
Bank Sta=404.25,444.93
Exp/Cntr=0.5,0.3

Type RM Length L Ch R = 1 ,207574.0,173.95,167.42,159.62
BEGIN DESCRIPTION:
20305.97  Upstream xs of Bridge 37111-0409
END DESCRIPTION:
XS GIS Cut Line= 3
  1117539.445866   672918.854431  1117550.452999   672682.200612
  1117594.481623   672302.453745
#Sta/Elev= 30
       0  1125.4      17  1118.2   26.08  1110.7  44.433  1105.8  61.819  1099.3
  72.444  1090.8  125.57  1088.9 140.059  1084.2 154.548  1077.9 178.696  1078.3
 200.913  1084.7 226.993  1103.2 228.828  1117.7 238.584  1120.9 254.618  1123.6
 268.044  1124.4 280.118  1129.7   286.3  1131.2 323.006  1136.7 349.182  1142.1
 360.001  1142.6 397.961    1148  430.32  1156.8 444.133  1159.7 474.463  1168.5
 476.878  1168.4 483.542  1170.6 496.196  1172.8 537.248  1174.9 598.101  1174.9
#Mann= 3 , 0 , 0
       0     .13       0  125.57    .046       0 200.913     .13       0
#XS Ineff= 2 , 0
       0   7.621 1112.83 239.115       0 1113.04
Permanent Ineff=
       F       F
Bank Sta=125.57,200.913
Skew Angle= 15
Exp/Cntr=0.5,0.3

Type RM Length L Ch R = 3 ,207469.0,,,
BEGIN DESCRIPTION:
20201  Bridge : 37111-0409
END DESCRIPTION:
Bridge Culvert--1,0,-1,-1, 0
Deck Dist Width WeirC Skew NumUp NumDn MinLoCord MaxHiCord MaxSubmerge Is_Ogee
98,14,2.6,15, 30, 31, , , 0.95, 0, 0,0,,
 -26.177 -23.665 -10.239   -8.79   1.352   6.472  22.892  33.807  33.807  72.444
  72.444 226.993 226.993 247.277 250.948 251.624 254.328 270.459  282.05 284.272
 306.681 311.414  325.71  325.71 325.807     326 355.557 361.546 370.336 382.796
  1124.1  1123.5  1119.4  1118.9  1117.7  1116.1    1113    1112    1112    1112
    1112    1112    1112  1110.9  1111.1    1111  1111.1  1108.1  1107.4  1107.7
  1109.4    1109  1108.1  1108.1  1108.1  1108.1  1109.8  1109.8  1110.6  1111.1
                                                                  1109.4  1109.4
  1103.2  1103.2
                                                                                
       0     8.5  11.012  24.438  25.887  36.029  41.148  57.569  67.615  67.615
 106.252 106.252   260.8   260.8 281.954 285.624   286.3 288.908 305.136 316.727
 318.949 341.358 346.091  360.29 360.387 360.387  360.58 390.234 396.223 405.013
 417.377
  1124.1  1124.1  1123.5  1119.4  1118.9  1117.7  1116.1    1113    1112    1112
    1112    1112    1112    1112  1110.9  1111.1    1111  1111.1  1108.1  1107.4
  1107.7  1109.4    1109  1108.1  1108.1  1108.1  1108.1  1109.8  1109.8  1110.6
  1111.1
                                                                          1109.4
  1109.4  1103.2  1103.2
                                                                                
        
Pier Skew= 15
Pier Skew, UpSta & Num, DnSta & Num=  ,61.819, 2 ,95.627, 2 , 0 , 0 , 0 ,,
       1       1
  1098.3  1109.9
       1       1
  1098.3  1109.9
Pier Skew, UpSta & Num, DnSta & Num=  ,72.444, 2 ,106.252, 2 , 0 , 0 , 0 ,,
       3       3
  1089.8  1109.9
       3       3
  1089.8  1109.9
Pier Skew, UpSta & Num, DnSta & Num=  ,125.57, 2 ,159.378, 2 , 0 , 0 , 0 ,,
       3       3
  1087.9  1109.9
       3       3
  1087.9  1109.9
Pier Skew, UpSta & Num, DnSta & Num=  ,140.059, 2 ,173.867, 2 , 0 , 0 , 0 ,,
       6       6
  1083.2  1109.9
       6       6
  1083.2  1109.9
BR Coef=-1 , 1 , 0 ,, 0 ,,,0.8,0,2,0,
WSPro=,,,, 1 ,,,, 0 ,,,, 0 ,,,,-1 ,-1 ,-1 , 0 , 0 , 0 , 0 , 0
BC Design=,, 0 ,, 0 ,,,,,,