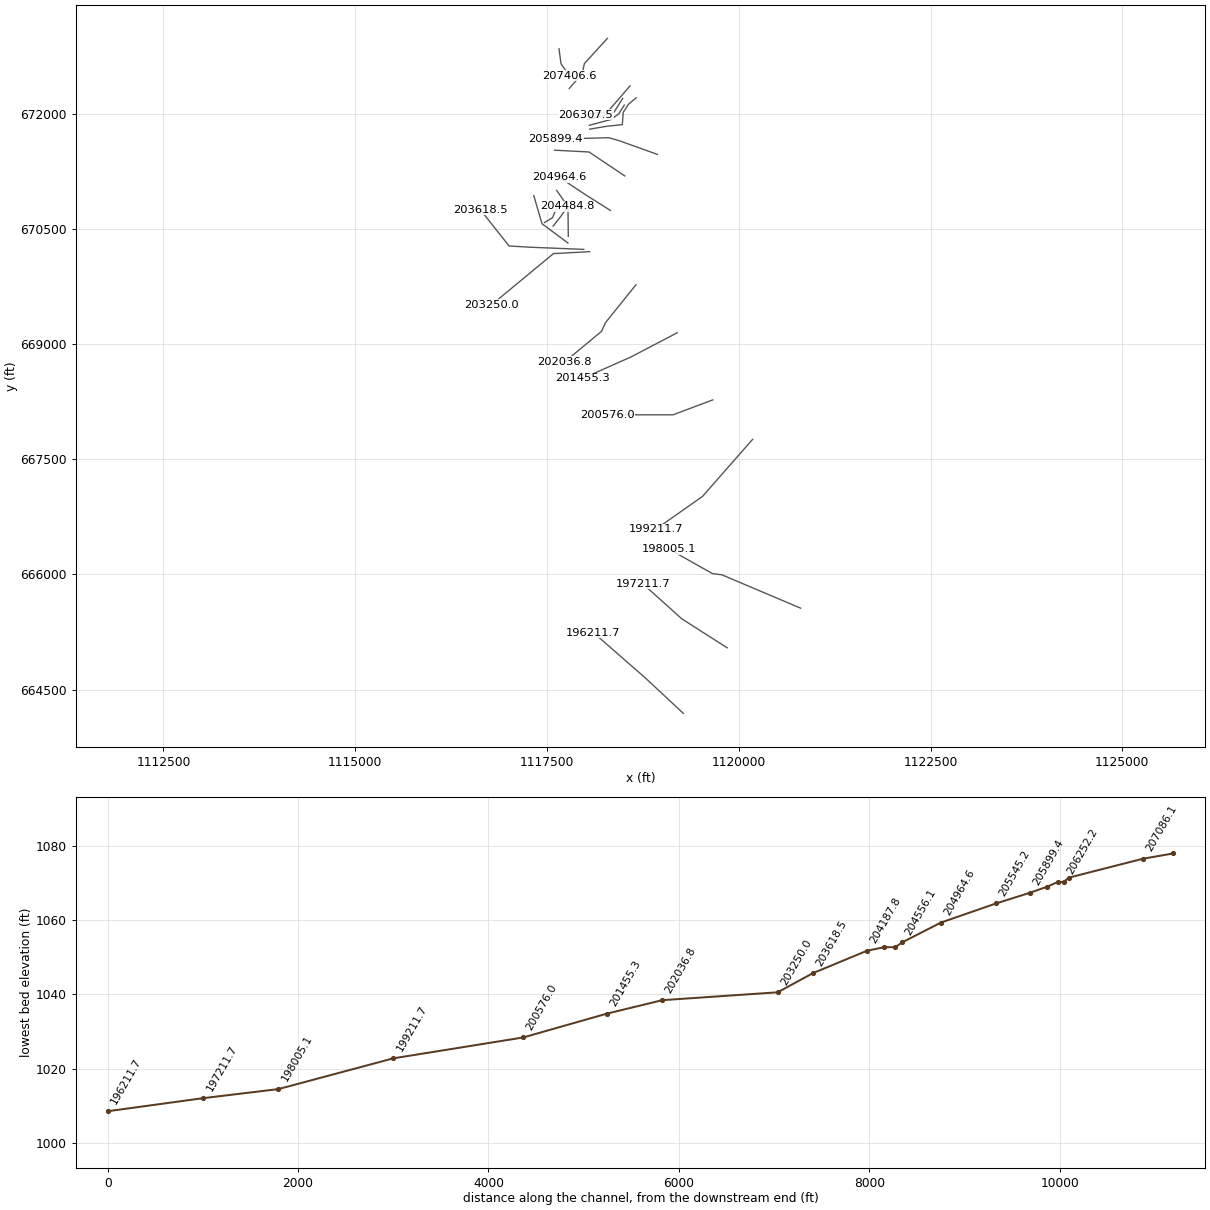
HEC-RAS study 2ndBroadRv.prj: 2ndBroadRv

--- 2ndBroadRv.g01 (geometry) --- (continued)

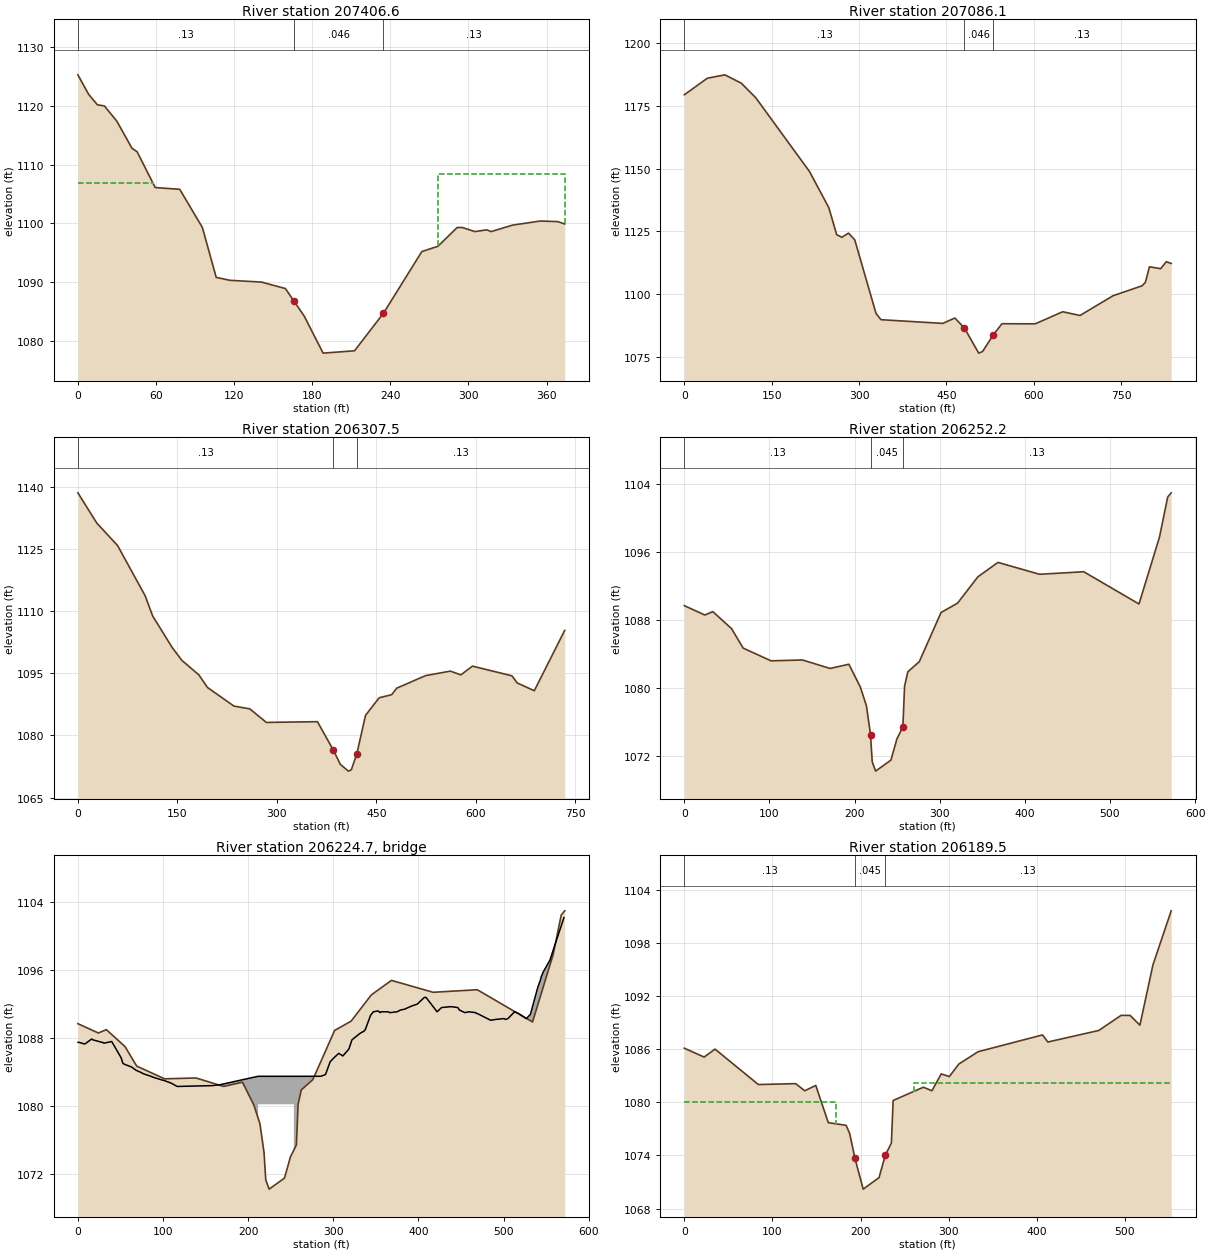
Type RM Length L Ch R = 1 ,207406.6,334.74,320.5,307.4
BEGIN DESCRIPTION:
20138.55  Down stream xs of Bridge 37111-0409
END DESCRIPTION:
XS GIS Cut Line= 4
  1117656.968633   672853.026286  1117664.959993   672792.027706
   1117682.53887   672660.186301  1117790.624051   672500.803872
#Sta/Elev= 30
       0  1125.3    8.21    1122  14.972  1120.2  20.381    1120  29.944  1117.4
  41.535  1112.8  45.495  1112.2  59.404  1106.1   78.24  1105.8  95.627  1099.3
 106.252  1090.8 116.877  1090.3 141.025    1090 159.378  1088.9  166.13 1086.71
 173.867  1084.2 188.356  1077.9 212.504  1078.3  234.72  1084.7 264.181  1095.2
 276.545  1096.1 291.323  1099.3 295.284  1099.3 304.943  1098.6 314.119  1098.9
 317.403  1098.6 333.824  1099.7 355.171  1100.4 368.597  1100.3  373.91  1099.9
#Mann= 3 , 0 , 0
       0     .13       0  166.13    .046       0  234.72     .13       0
#XS Ineff= 2 , 0
       0  57.898 1106.86 276.361       0  1108.4
Permanent Ineff=
       F       F
Bank Sta=166.13,234.72
Skew Angle= 15
Exp/Cntr=0.5,0.3

Type RM Length L Ch R = 1 ,207086.1,792.4,778.58,762.39
BEGIN DESCRIPTION:
19818.05
END DESCRIPTION:
XS GIS Cut Line= 4
   1118287.86441   672989.616404  1117987.191884   672660.497625
  1117959.165527    672528.89571  1117790.624051   672336.461716
#Sta/Elev= 30
       0  1179.4   39.46 1185.99   69.65 1187.34   97.96 1183.98  122.68 1178.21
  214.89 1148.85  248.21 1134.38  261.62 1123.68  270.45 1122.61   281.9 1124.28
  292.66 1121.62   329.2 1092.29  337.68 1089.79  443.97 1088.31  464.68 1090.47
  481.13 1086.42  505.61 1076.47  512.23 1077.12   530.7 1083.78  545.55 1088.18
  602.75 1088.15   649.8 1092.95  679.54 1091.47   736.3 1099.33  786.34 1103.31
  791.85 1104.68   798.8 1110.86  818.13 1110.12  827.65 1112.88  836.14  1112.2
#Mann= 3 , 0 , 0
       0     .13       0  481.13    .046       0   530.7     .13       0
Bank Sta=481.13,530.7
Exp/Cntr=0.3,0.1

Type RM Length L Ch R = 1 ,206307.5,68.47,55.23,41.95
BEGIN DESCRIPTION:
19039.47
END DESCRIPTION:
XS GIS Cut Line= 4
  1118582.837504   672370.172934  1118342.645129   672092.055405
  1118290.606487   672032.455961  1118005.533034   671995.135686
#Sta/Elev= 30
       0 1138.64   28.39 1131.36   59.86  1125.9   101.5 1113.75  112.81 1108.87
  142.26 1101.24  156.89 1098.14  182.51 1094.63  195.41  1091.6   235.3  1087.1
  259.23 1086.43  284.17 1083.15  361.26 1083.33  385.45 1076.39  395.84    1073
  407.94 1071.38  412.26  1071.7  420.48 1075.45   433.7 1084.84  454.29 1089.11
  473.27 1089.86  480.82 1091.43  524.32 1094.46  561.59 1095.55  577.57 1094.64
  594.99 1096.76  654.58 1094.41  662.36  1092.7  688.25 1090.81  734.11  1105.4
#Mann= 3 , 0 , 0
       0     .13       0  385.45    .046       0  420.48     .13       0
Bank Sta=385.45,420.48
Exp/Cntr=0.5,0.3

Type RM Length L Ch R = 1 ,206252.2,55.17,62.73,70.35
BEGIN DESCRIPTION:
18984.23  Upstream xs of Bridge 37111-0381
END DESCRIPTION:
XS GIS Cut Line= 5
  1118485.917784   672205.830778  1118388.230595   672049.473274
   1118377.34616   672029.881319   1118307.68586   671999.404929
  1118026.602535   671931.927185
#Sta/Elev= 30
       0  1089.7    24.1  1088.6    33.4    1089    55.4    1087    69.1  1084.7
   101.8  1083.2   138.8  1083.3   171.2  1082.3   193.3  1082.8   206.8  1080.1
   213.9  1077.9   218.7  1074.5   220.7  1071.3   224.7  1070.2   242.7  1071.5
   249.7    1074   256.7  1075.4   258.7  1080.2   262.5  1081.9     276  1083.1
   301.6  1088.9     321    1090   344.8  1093.1   368.4  1094.8   417.3  1093.4
   469.2  1093.7   534.1  1089.9   558.2  1097.8   567.8  1102.5   571.9    1103
#Mann= 3 , 0 , 0
       0     .13       0   218.7    .045       0   256.7     .13       0
#XS Ineff= 2 , 0
       0   195.4    1082  272.13       0    1082
Permanent Ineff=
       F       F
Bank Sta=218.7,256.7
Exp/Cntr=0.5,0.3

Type RM Length L Ch R = 3 ,206224.7,,,
BEGIN DESCRIPTION:
18956.64  Bridge : 37111-0381
END DESCRIPTION:
Bridge Culvert--1,0,-1,-1, 0
Deck Dist Width WeirC Skew NumUp NumDn MinLoCord MaxHiCord MaxSubmerge Is_Ogee
20.6,14,2.6,0, 89, 88, , , 0.95, 0, 0,0,,
      .2     1.2     8.1    16.3    17.4    28.3    29.2    30.5    39.7    50.7
      53    57.6    62.9    68.5    75.2    76.8    85.7      88    97.5   101.4
   109.4   116.7   158.1   166.7   211.7   211.7   253.7   253.7   268.6   285.3
   290.8   292.7   296.3     301   306.4   311.3   318.3     322     332   335.9
   337.6   343.9   346.3   347.1   352.6   352.7   355.1     356   356.6   364.4
   366.7   374.9   378.8   383.5     388   392.6   398.6   407.1   407.7   408.3
   408.9     422   427.2   437.1   438.9   446.3   448.3   454.7   459.1   467.4
   468.2   468.7   469.1     485   490.9   500.6   502.4   505.2     513   517.6
   526.8   531.6   540.3   543.2   544.2   546.7   554.6   557.5     571
  1087.5  1087.5  1087.3  1087.9  1087.8  1087.5  1087.5  1087.4  1087.6  1085.7
    1085  1084.8  1084.6  1084.2  1083.9  1083.8  1083.5  1083.4  1083.1    1083
  1082.7  1082.3  1082.4  1082.5  1083.5  1083.5  1083.5  1083.5  1083.5  1083.5
  1083.7  1084.2  1085.2  1085.7  1086.2  1085.9  1086.7  1087.8  1088.6  1088.8
    1089  1090.7    1091  1091.1  1091.2  1091.2    1091  1091.1  1091.1  1091.1
    1091  1091.1  1091.3  1091.4  1091.6  1091.8    1092  1092.8  1092.8  1092.8
  1092.8  1091.1  1091.6  1091.7  1091.7  1091.6  1091.3    1091  1091.1    1091
  1090.9  1090.9  1090.9  1090.1  1090.2  1090.3  1090.2  1090.3  1091.1  1090.9
  1090.3  1090.8    1094  1094.8  1095.2  1095.8  1097.2  1098.1  1102.2
                                                                                
                                                                                
                                          1080.2  1080.2
                                                                                
                                                                                
                                                                                
                                                                                
                                                                                
                                                                        
   -11.2   -10.3    -3.3     4.9       6    16.9    17.7    19.1    28.3    39.3
    41.6    46.2    51.4    57.1    63.8    65.4    74.3    76.6    86.1   121.3
   160.7     190     190     232     232   257.2   264.9   267.6   273.8   279.4
   281.3   284.9   289.6     295   299.9   306.8   310.5   320.6   324.5   326.2
   332.5   334.9   335.6   341.1   341.3   343.7   344.5   345.2     353   355.3
   363.4   367.3     372   376.5   381.1   387.1   395.7   396.3   396.9   397.4
   410.5   415.8   425.7   427.5   434.9   436.9   443.3   447.6     456   456.8
   457.3   457.7   473.5   479.4   489.2     491   493.7   501.6   506.1   515.4
   520.2   528.9   531.8   532.8   535.3   543.1   546.1   559.6
  1087.5  1087.5  1087.3  1087.9  1087.8  1087.5  1087.5  1087.4  1087.6  1085.7
    1085  1084.8  1084.6  1084.2  1083.9  1083.8  1083.5  1083.4  1083.1    1083
    1083  1083.5  1083.5  1083.5  1083.5  1083.5  1083.1  1083.2  1083.5  1083.7
  1084.2  1085.2  1085.7  1086.2  1085.9  1086.7  1087.8  1088.6  1088.8    1089
  1090.7    1091  1091.1  1091.2  1091.2    1091  1091.1  1091.1  1091.1    1091
  1091.1  1091.3  1091.4  1091.6  1091.8    1092  1092.8  1092.8  1092.8  1092.8
  1091.1  1091.6  1091.7  1091.7  1091.6  1091.3    1091  1091.1    1091  1090.9
  1090.9  1090.9  1090.1  1090.2  1090.3  1090.2  1090.3  1091.1  1090.9  1090.3
  1090.8    1094  1094.8  1095.2  1095.8  1097.2  1098.1  1102.2
                                                                                
                                                                                
                  1080.2  1080.2
                                                                                
                                                                                
                                                                                
                                                                                
                                                                                
                                                                
BR Coef=-1 , 1 , 0 ,, 0 ,,,0.8,0,1.2,0,
WSPro=,,,, 1 ,,,, 0 ,,,, 0 ,,,,-1 ,-1 ,-1 , 0 , 0 , 0 , 0 , 0
BC Design=,, 0 ,, 0 ,,,,,,

Type RM Length L Ch R = 1 ,206189.5,124.03,107.23,90.29
BEGIN DESCRIPTION:
18921.51  Down stream xs of Bridge 37111-0381
END DESCRIPTION:
XS GIS Cut Line= 4
  1118507.959239   672119.133619  1118436.122026   672005.935581
  1118335.985336   671931.921543  1118051.885926   671856.076966
#Sta/Elev= 30
       0  1086.1    22.5  1085.1    34.8    1086      84    1082   126.3  1082.1
   136.7  1081.3   149.2  1081.9   163.4  1077.7   183.6  1077.4  187.641076.491
  193.61  1073.7     203  1070.2     221  1071.5     228    1074     235  1075.4
     237  1080.2   271.3  1081.7     281  1081.3   291.6  1083.2   300.8  1082.9
   311.4  1084.3   333.3  1085.7   406.6  1087.6   412.6  1086.8   470.4  1088.1
   495.7  1089.8     506  1089.8   517.1  1088.7   531.9  1095.5   552.6  1101.6
#Mann= 3 , 0 , 0
       0     .13       0  193.61    .045       0     228     .13       0
#XS Ineff= 2 , 0
       0  172.03    1080  260.14       0 1082.12
Permanent Ineff=
       F       F
Bank Sta=193.61,228
Exp/Cntr=0.5,0.3

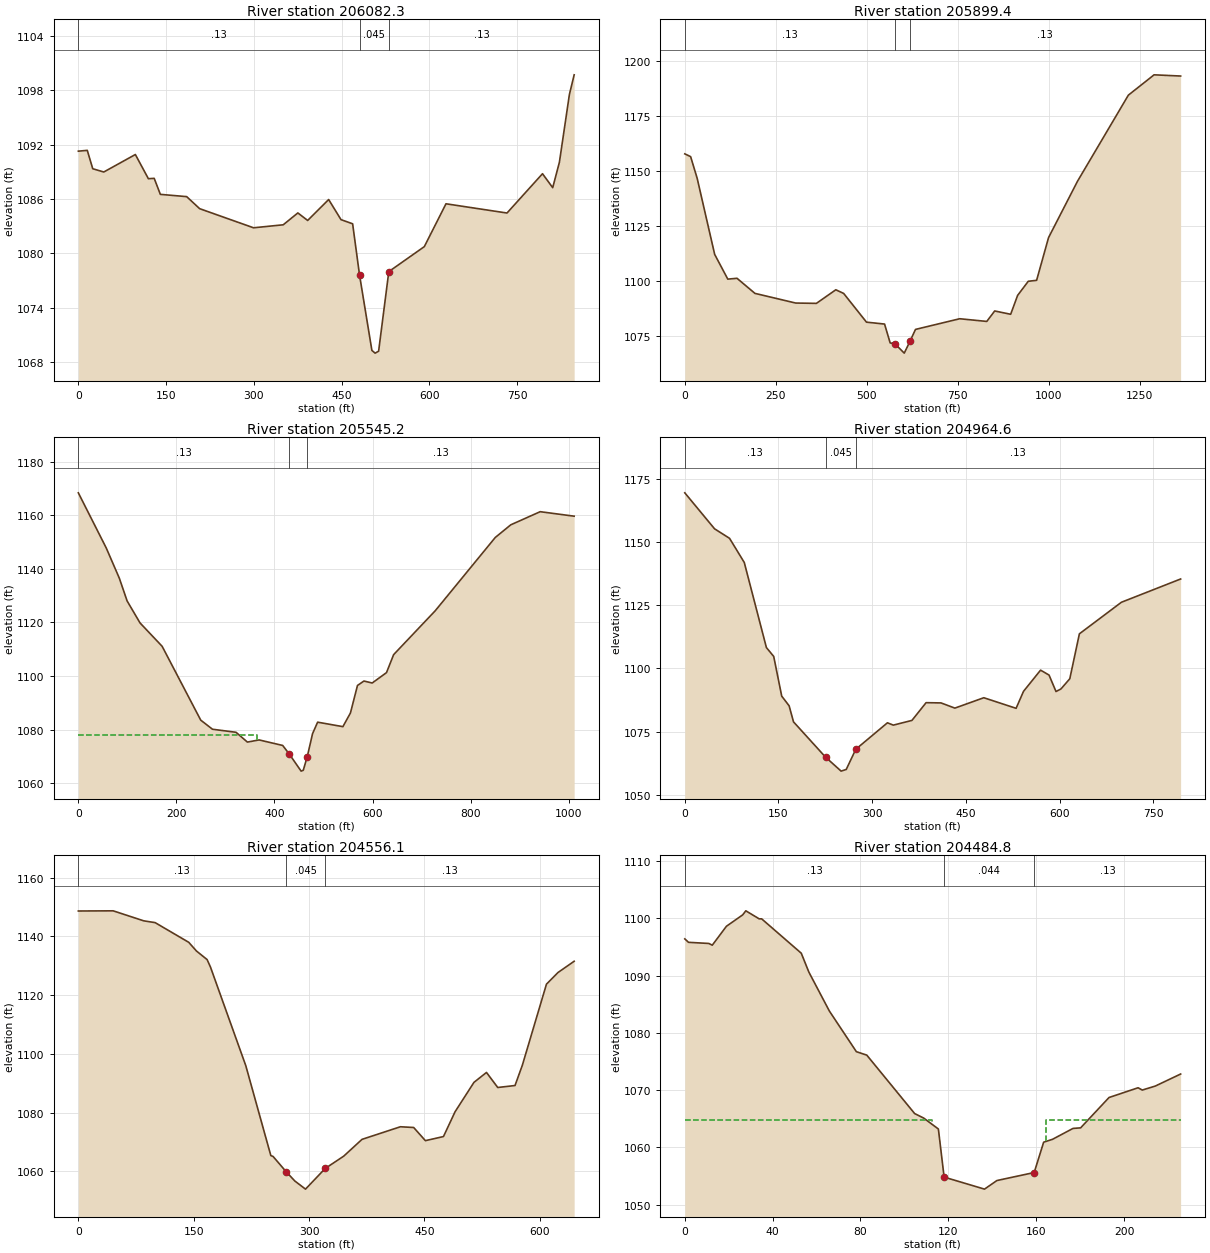
Type RM Length L Ch R = 1 ,206082.3,194.3,182.86,171.36
BEGIN DESCRIPTION:
18814.28
END DESCRIPTION:
XS GIS Cut Line= 6
  1118662.901658    672214.25856  1118561.768003   672129.980559
  1118494.345567   672024.633013  1118481.703893   671864.504748
  1118279.436628   671843.435248  1118056.099817   671805.510138
#Sta/Elev= 30
       0 1091.27   15.29 1091.36   24.65 1089.33    43.5 1088.97   97.45  1090.9
   119.7 1088.23  129.64 1088.27  140.17  1086.5  185.14 1086.25  207.33 1084.92
  299.42 1082.81  350.14 1083.14  375.11 1084.45  391.87 1083.62  427.74 1085.93
  448.84 1083.71  468.71 1083.25   480.5  1077.6  501.62 1069.27  507.11 1068.97
  513.12 1069.18  530.52 1077.97  591.22 1080.73  628.25 1085.46   732.5 1084.44
  793.14 1088.78   810.6 1087.24  822.04 1090.05  839.12 1097.53  847.24  1099.7
#Mann= 3 , 0 , 0
       0     .13       0   480.5    .045       0  530.52     .13       0
Bank Sta=480.5,530.52
Exp/Cntr=0.3,0.1

Type RM Length L Ch R = 1 ,205899.4,350,354.18,360
BEGIN DESCRIPTION:
18631.41
END DESCRIPTION:
XS GIS Cut Line= 4
  1118938.982387   671476.680559  1118438.298939   671656.273505
  1118304.964752    671694.36898  1117613.803924   671675.321265
#Sta/Elev= 30
       0 1157.85   16.04 1156.58   34.03 1146.73   82.05 1112.19   118.1 1100.95
  143.48 1101.32  192.67 1094.47  304.65 1090.08   361.5 1089.93  414.86 1096.11
  436.38 1094.45  499.12  1081.4  548.78 1080.53  564.08 1071.98  577.27 1071.57
  602.82 1067.33  618.75 1072.77  633.72  1078.1  755.18 1082.95  829.55 1081.73
  851.25 1086.48  895.15 1084.98  914.28 1093.56  943.53 1099.97  966.41  1100.4
  999.25 1119.82 1078.83 1145.43 1218.48 1184.52 1289.11 1193.75 1362.01  1193.2
#Mann= 3 , 0 , 0
       0     .13       0  577.27    .045       0  618.75     .13       0
Bank Sta=577.27,618.75
Exp/Cntr=0.3,0.1

Type RM Length L Ch R = 1 ,205545.2,579.09,580.63,581.12
BEGIN DESCRIPTION:
18277.23
END DESCRIPTION:
XS GIS Cut Line= 3
  1118514.615611   671195.158191  1118048.210677   671508.026106
  1117599.187333   671531.201486
#Sta/Elev= 30
       0 1168.33   57.04 1147.71   83.59 1136.48   99.49 1127.99  125.79 1119.79
  170.97 1111.04  249.64  1083.5  273.62  1080.1  321.68 1078.96  344.81 1075.31
  368.78 1076.11  416.79 1074.05  430.56 1070.76  454.38 1064.47  458.78 1064.79
  466.78 1069.79  477.69 1078.44  488.05 1082.74  539.59 1081.07  554.94 1086.16
  569.34 1096.44  582.44 1098.09  599.34 1097.36  628.52 1101.23  643.05 1107.94
  727.87 1124.31  850.38 1151.67  881.99 1156.39  941.98 1161.29 1011.24 1159.61
#Mann= 3 , 0 , 0
       0     .13       0  430.56    .045       0  466.78     .13       0
#XS Ineff= 2 , 0
          365.07 1077.81
Permanent Ineff=
       F       F
Bank Sta=430.56,466.78
Exp/Cntr=0.3,0.1

Type RM Length L Ch R = 1 ,204964.6,438.2,408.54,377.84
BEGIN DESCRIPTION:
17696.59
END DESCRIPTION:
XS GIS Cut Line= 3
  1118326.315501   670746.134847  1118004.756812   670948.919564
  1117660.022744   671177.776645
#Sta/Elev= 30
       0 1169.55   47.64  1155.3   71.65 1151.53   95.23 1141.97  130.68 1108.26
  142.38 1104.75   155.2 1089.03  167.04  1085.2   174.1 1078.83  225.41 1064.85
  250.32 1059.32  258.52 1059.99  273.85 1067.99  324.47 1078.46  333.89 1077.54
  363.73 1079.41  386.35 1086.43  410.23 1086.34  432.45 1084.28   478.8 1088.39
   530.5  1084.2  542.39 1090.93   569.7 1099.32  583.28 1097.36  594.39 1090.85
   602.3 1091.86  616.48 1095.91  631.85  1113.7   699.1  1126.2  793.94 1135.42
#Mann= 3 , 0 , 0
       0     .13       0  225.41    .045       0  273.85     .13       0
Bank Sta=225.41,273.85
Exp/Cntr=0.3,0.1

Type RM Length L Ch R = 1 ,204556.1,93.13,71.22,49.32
BEGIN DESCRIPTION:
17288.05
END DESCRIPTION:
XS GIS Cut Line= 3
  1117777.676562   670408.692548  1117773.580261   670796.351346
  1117626.093714   671007.046394
#Sta/Elev= 30
       0 1148.61   45.29 1148.67   85.13 1145.26   99.85 1144.66  143.58 1137.96
  153.64    1135  167.49 1132.08  171.82 1129.57  217.82 1095.97  250.37 1065.39
  253.28  1065.1  270.33  1059.9  281.53 1056.76  295.46 1053.98  321.13 1061.02
  345.13 1065.19  368.94 1070.91  418.89  1075.2  436.15 1074.95  451.39 1070.47
  474.91 1071.87  489.94 1080.28  514.54  1090.3  530.85 1093.68  545.48 1088.56
  567.93 1089.23  577.42 1096.08  608.84 1123.71  623.85 1127.68  644.87 1131.51
#Mann= 3 , 0 , 0
       0     .13       0  270.33    .045       0  321.13     .13       0
Bank Sta=270.33,321.13
Exp/Cntr=0.5,0.3

Type RM Length L Ch R = 1 ,204484.8,107.02,115.57,124.61
BEGIN DESCRIPTION:
17216.83  Upstream xs of Bridge 37111-0382
END DESCRIPTION:
XS GIS Cut Line= 4
  1117579.929003   670541.339718  1117676.354727   670663.623503
  1117733.131508   670744.917538  1117767.971809   670799.113547
#Sta/Elev= 30
       0  1096.4   1.697  1095.8   10.96  1095.6  12.516  1095.3   18.95  1098.6
  26.375  1100.6  27.789  1101.3   33.87  1099.9  35.002  1099.9  53.033  1093.9
  56.498  1090.6  65.832  1083.8  78.135  1076.7  82.873  1076.1 104.652  1065.9
 108.824  1065.1 115.471  1063.2 118.087  1054.8 136.472  1052.7 142.128  1054.2
 159.099  1055.6 163.412  1060.9 167.443  1061.4 176.777  1063.3 180.242  1063.4
 193.182  1068.7 206.404  1070.4 208.314    1070 214.253  1070.7 225.779  1072.8
#Mann= 3 , 0 , 0
       0     .13       0 118.087    .044       0 159.099     .13       0
#XS Ineff= 2 , 0
       0  112.64 1064.74  164.59       0 1064.85
Permanent Ineff=
       F       F
Bank Sta=118.087,159.099
Skew Angle= 45
Exp/Cntr=0.5,0.3

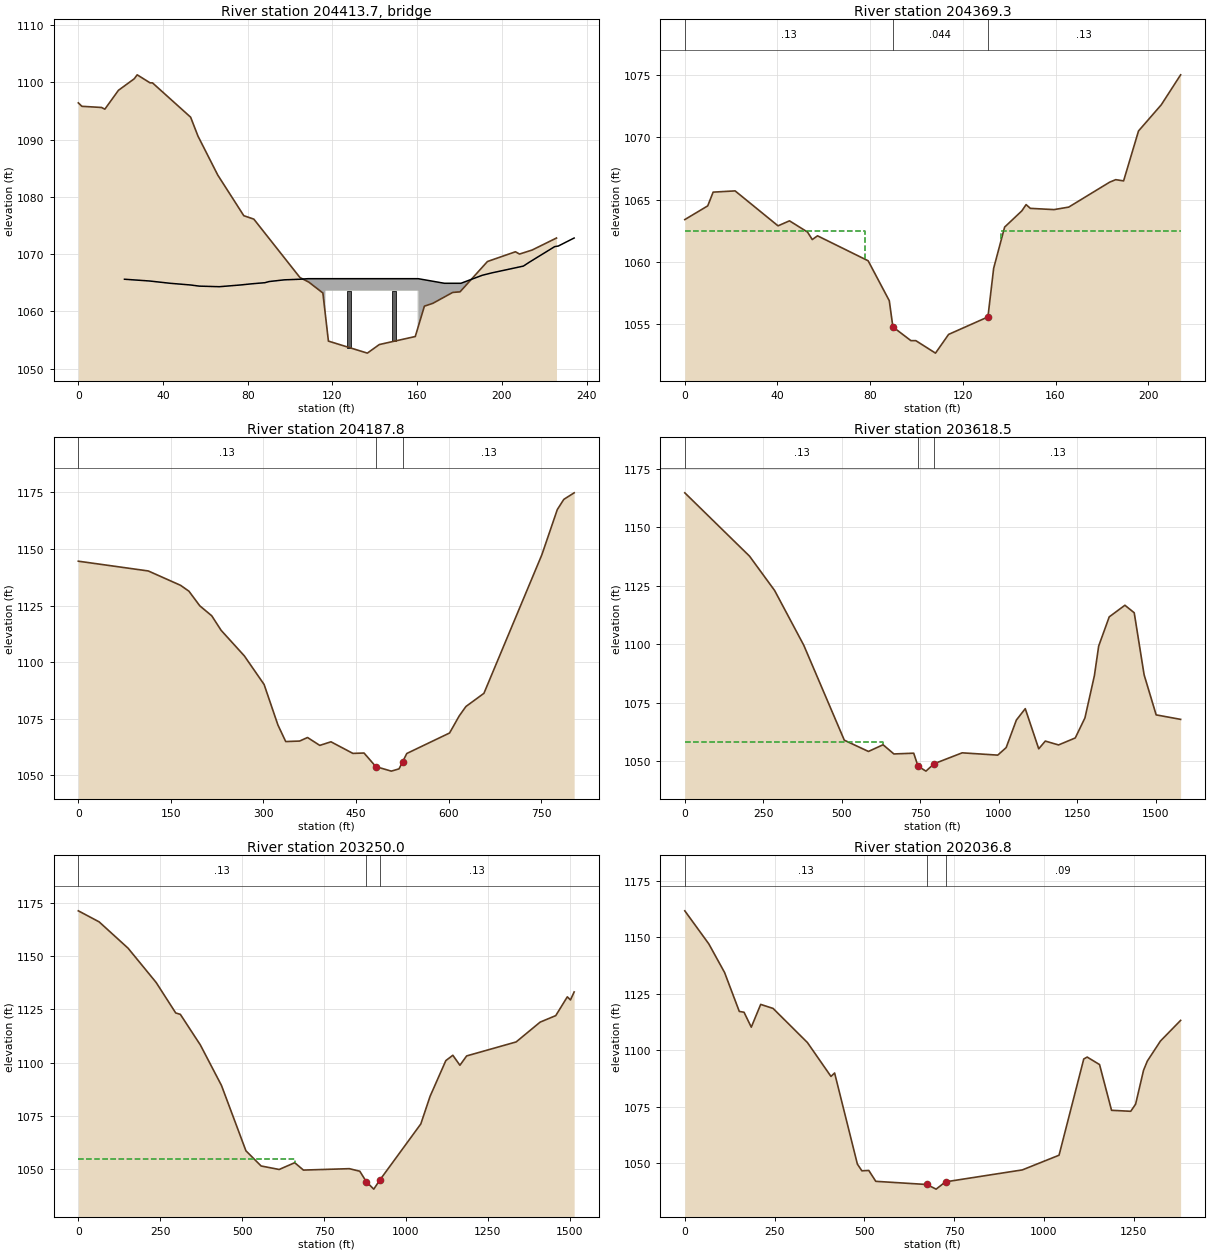
Type RM Length L Ch R = 3 ,204413.7,,,
BEGIN DESCRIPTION:
17145.72  Bridge : 37111-0382
END DESCRIPTION:
Bridge Culvert--1,0,-1,-1, 0
Deck Dist Width WeirC Skew NumUp NumDn MinLoCord MaxHiCord MaxSubmerge Is_Ogee
61.1,20,2.6,45, 30, 26, 1064.3, , 0.95, 0, 0,0,,
  21.779  21.991  33.517  43.275  52.962  57.134  66.609  76.509  81.742  88.105
  90.085  97.298  104.51 108.399 116.673 116.673 160.513 160.513 172.817 177.555
 179.888 180.666 190.777 195.091 210.152 213.051 224.931 226.628 233.557 234.123
  1065.6  1065.6  1065.3  1064.9  1064.6  1064.4  1064.3  1064.6  1064.8    1065
  1065.2  1065.5  1065.6  1065.7  1065.7  1065.7  1065.7  1065.7  1064.9  1064.9
  1064.9  1064.9  1066.3  1066.7  1067.9  1068.6  1071.3  1071.4  1072.7  1072.8
                                                                                
                                          1063.6  1063.6
                                                                                
  -3.889  -3.677    7.92  17.607  27.365  31.537  41.012  49.215  57.134  64.488
  71.701  82.731  88.388  88.388 132.229 132.229 147.149 151.957 154.291 154.998
  162.21 169.423 173.736 199.263 207.889 208.526
  1065.6  1065.6  1065.3  1064.9  1064.6  1064.4  1064.3  1064.7  1064.9  1065.2
  1065.5  1065.7  1065.7  1065.7  1065.7  1065.7  1064.9  1064.9  1064.9  1064.9
  1066.4  1066.7  1068.1  1071.3  1072.7  1072.8
                                                                                
                          1063.6  1063.6
                                                
Pier Skew= 45
Pier Skew, UpSta & Num, DnSta & Num=  ,127.986, 2 ,99.702, 2 , 0 , 0 , 0 ,,
       2       2
  1052.7  1064.1
       2       2
  1052.7  1064.1
Pier Skew, UpSta & Num, DnSta & Num=  ,149.2, 2 ,120.915, 2 , 0 , 0 , 0 ,,
       2       2
  1053.7  1064.1
       2       2
  1053.7  1064.1
BR Coef=-1 , 1 , 0 ,, 0 ,,,0.8,0,1,0,
WSPro=,,,, 1 ,,,, 0 ,,,, 0 ,,,,-1 ,-1 ,-1 , 0 , 0 , 0 , 0 , 0
BC Design=,, 0 ,, 0 ,,,,,,

Type RM Length L Ch R = 1 ,204369.3,159.98,181.46,202.46
BEGIN DESCRIPTION:
17101.25  Down stream xs of Bridge 37111-0382
END DESCRIPTION:
XS GIS Cut Line= 4
   1117466.15363   670587.692654  1117573.124255   670652.010069
  1117613.126057   670753.950199  1117638.933697   670817.178869
#Sta/Elev= 30
       0  1063.4   9.899  1064.5  12.233  1065.6  21.708  1065.7  40.234  1062.9
  45.184  1063.3  52.962  1062.4  55.013  1061.8  57.276  1062.1  79.125  1060.1
  88.247  1056.9  89.803  1054.8  97.581  1053.7  99.702  1053.7 108.187  1052.7
 113.844  1054.2 130.815  1055.6  133.29  1059.5 138.027  1062.8 145.452  1064.1
  147.29  1064.6 149.129  1064.3 159.311  1064.2 165.675  1064.4 183.353  1066.4
 185.969  1066.6 189.363  1066.5 195.798  1070.5 205.627  1072.6 213.971    1075
#Mann= 3 , 0 , 0
       0     .13       0  89.803    .044       0 130.815     .13       0
#XS Ineff= 2 , 0
       0   77.67  1062.5  136.61       0  1062.5
Permanent Ineff=
       F       F
Bank Sta=89.803,130.815
Skew Angle= 45
Exp/Cntr=0.5,0.3

Type RM Length L Ch R = 1 ,204187.8,531.94,569.26,605.76
BEGIN DESCRIPTION:
16919.79
END DESCRIPTION:
XS GIS Cut Line= 3
  1117773.415626   670321.343155  1117434.670369   670572.738973
  1117328.146695   670939.180383
#Sta/Elev= 30
       0 1144.61  113.36 1140.29  165.71 1133.93  179.23 1131.34  196.83 1124.87
  216.16 1120.47  231.38 1114.04  268.97 1102.74  301.02 1090.09  323.36 1072.21
  336.05 1064.83  358.55 1065.05  371.38 1066.62  391.26 1063.13  409.36 1064.72
  444.93 1059.59  462.96 1059.76  482.08 1053.75  507.15 1051.75  519.69 1052.75
  525.71 1055.97  532.23 1059.55  601.58 1068.62   617.2 1076.17  628.09 1080.34
  657.25 1086.17  751.21 1147.52  776.12 1167.43  786.71 1171.96  803.45 1174.85
#Mann= 3 , 0 , 0
       0     .13       0  482.08    .044       0  525.71     .13       0
Bank Sta=482.08,525.71
Exp/Cntr=0.3,0.1

Type RM Length L Ch R = 1 ,203618.5,345.27,368.54,391.23
BEGIN DESCRIPTION:
16350.53
END DESCRIPTION:
XS GIS Cut Line= 4
  1117979.732058   670238.612178  1117286.281302   670266.130056
  1117005.598815   670282.640801  1116631.355559   670755.948483
#Sta/Elev= 30
       0 1164.65  206.19 1137.57  286.11 1122.88  378.75 1099.52  507.84 1058.93
  584.67 1054.12  631.29 1056.98  665.63 1053.05   728.8 1053.37  742.46 1047.83
  767.76 1045.71  793.92 1048.88  883.12 1053.53  996.34 1052.55 1023.16 1055.77
 1055.62 1067.53 1083.93 1072.41 1126.82 1055.25 1147.73 1058.55 1189.88  1056.9
 1243.13 1059.89 1273.92 1068.45 1304.05 1086.52 1317.63 1099.14 1351.25 1111.64
 1401.17  1116.6 1430.84 1113.39 1462.34 1086.87 1500.66 1069.75 1578.55 1067.83
#Mann= 3 , 0 , 0
       0     .13       0  742.46    .044       0  793.92     .13       0
#XS Ineff= 2 , 0
           631.5 1058.28
Permanent Ineff=
       F       F
Bank Sta=742.46,793.92
Exp/Cntr=0.3,0.1

Type RM Length L Ch R = 1 ,203250.0,1199.09,1213.17,1226.85
BEGIN DESCRIPTION:
15982
END DESCRIPTION:
XS GIS Cut Line= 3
  1118056.099817   670208.441515  1117584.142894   670183.158079
  1116782.004923   669519.670392
#Sta/Elev= 30
       0  1171.2   63.42 1166.03  151.92 1153.65  237.56 1137.57  297.29 1123.26
  311.44 1122.61   372.5 1108.25  437.01 1089.23  511.64 1058.57  558.08 1051.44
  613.12  1049.8  660.57 1052.99  687.12 1049.52  827.12 1050.18  859.24 1048.98
  879.21 1044.05  901.93 1040.58  920.83 1044.94 1045.52 1071.18 1073.76 1084.13
 1121.86  1100.9 1143.28 1103.41 1164.86 1098.72 1185.42  1103.1 1336.48 1109.66
 1409.75 1118.96 1457.38 1122.01 1492.76 1130.83 1502.32 1129.37 1513.61 1133.13
#Mann= 3 , 0 , 0
       0     .13       0  879.21    .044       0  920.83     .13       0
#XS Ineff= 2 , 0
          660.29 1054.79
Permanent Ineff=
       F       F
Bank Sta=879.21,920.83
Exp/Cntr=0.3,0.1

Type RM Length L Ch R = 1 ,202036.8,601.49,581.57,560.65
BEGIN DESCRIPTION:
14768.82
END DESCRIPTION:
XS GIS Cut Line= 4
  1118659.782466   669777.021615  1118261.606665    669281.84551
  1118211.240857   669169.921511  1117732.070572   668772.876792
#Sta/Elev= 30
       0 1161.64   66.94 1146.99  110.73 1134.35  151.72 1117.12  164.95 1116.75
   185.1 1110.14  211.28 1120.22  245.82 1118.44  341.47 1103.33  406.93 1088.35
   417.1 1089.86  480.53 1049.53  492.99 1046.57  512.26 1046.73  531.73 1041.91
  673.58 1040.51  699.73 1038.46  725.88 1041.68  939.79 1046.97 1041.96 1053.47
 1110.75 1096.06 1120.25 1096.91 1154.71  1093.6  1188.1 1073.35 1241.58 1072.91
 1255.11 1076.07 1277.22 1091.06 1287.76 1095.15 1324.27 1104.01 1380.44 1113.15
#Mann= 3 , 0 , 0
       0     .13       0  673.58    .044       0  725.88     .09       0
Bank Sta=673.58,725.88
Exp/Cntr=0.3,0.1

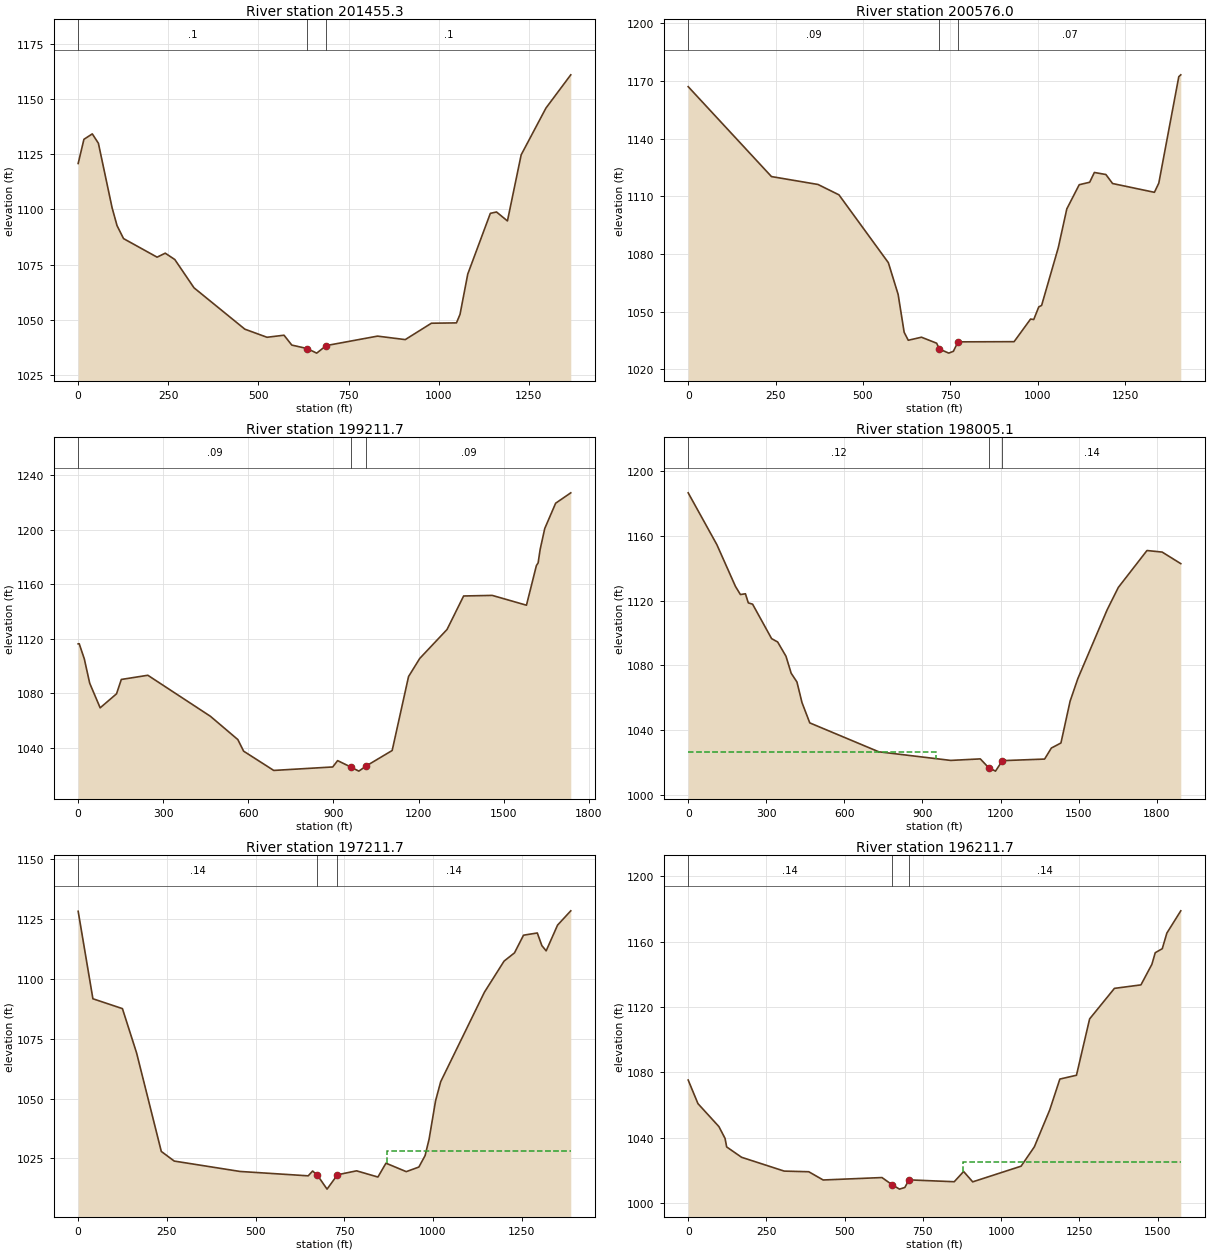
Type RM Length L Ch R = 1 ,201455.3,893.66,879.31,865.16
BEGIN DESCRIPTION:
14187.25
END DESCRIPTION:
XS GIS Cut Line= 3
  1119197.629461   669151.044472  1118592.590856   668834.604727
  1117967.760744   668557.703396
#Sta/Elev= 30
       0 1120.82   15.98 1131.79   39.15 1134.25   56.08 1130.02   94.09 1100.75
  107.81 1092.64  125.85 1086.77  218.92 1078.35   241.5 1080.16  268.08 1077.27
  321.26 1064.46  462.31  1045.7  523.74 1042.03  570.95 1042.96  592.49 1038.49
     635 1036.92  661.57 1034.84  688.07 1038.26  830.24 1042.55  907.12 1040.97
  979.75  1048.4 1049.19 1048.55 1059.09 1052.42  1080.5 1070.66 1143.18 1098.22
 1160.27 1098.84 1190.59 1094.78 1228.66 1124.75 1297.48 1145.98 1366.23 1161.03
#Mann= 3 , 0 , 0
       0      .1       0     635    .044       0  688.07      .1       0
Bank Sta=635,688.07
Exp/Cntr=0.3,0.1

Type RM Length L Ch R = 1 ,200576.0,1338.56,1364.24,1382.4
BEGIN DESCRIPTION:
13307.95
END DESCRIPTION:
XS GIS Cut Line= 3
  1119661.253936   668276.133227  1119144.407273   668081.802147
  1118287.602974   668081.802147
#Sta/Elev= 30
       0 1166.99  238.18 1120.24  371.33 1116.13  431.25 1110.74  572.54 1075.47
  600.53 1058.97  617.77 1039.26  629.49 1035.13  667.26 1036.71  710.66  1033.6
   718.7 1030.54  745.35 1028.44  758.59 1029.41  771.84  1034.3  932.23  1034.4
  979.35 1046.16  988.38 1045.91 1002.76 1052.48 1010.88 1053.24 1058.54 1083.24
 1082.96 1103.42 1118.45    1116 1148.38 1117.29 1161.79 1122.37 1194.75 1121.31
 1213.85 1116.63 1333.56 1112.05 1346.12 1116.83  1403.3 1172.17 1408.98 1173.14
#Mann= 3 , 0 , 0
       0     .09       0   718.7    .044       0  771.84     .07       0
Bank Sta=718.7,771.84
Exp/Cntr=0.3,0.1

Type RM Length L Ch R = 1 ,199211.7,1230.6,1206.6,1180.67
BEGIN DESCRIPTION:
11943.71
END DESCRIPTION:
XS GIS Cut Line= 3
  1120181.163063   667762.002297  1119528.251374   667018.586527
  1118917.077581   666588.700724
#Sta/Elev= 30
       0 1116.28    3.76 1116.34    21.7 1105.21   40.66 1087.38   77.55  1069.3
  135.22 1079.59  152.14 1090.13   245.6 1093.21  466.21  1063.1  562.88    1046
   583.3 1037.49  689.44 1023.34  897.44 1025.89  914.75 1030.55  963.07 1025.65
  989.42 1022.83 1015.85 1026.66    1107 1037.98 1164.75 1092.27 1204.25 1105.57
 1300.41 1126.82 1358.91 1151.42 1459.87 1151.85 1580.43 1144.65 1615.52 1173.79
 1621.62 1175.75 1628.68 1185.59 1644.89 1200.94  1683.3 1219.53 1736.64 1227.16
#Mann= 3 , 0 , 0
       0     .09       0  963.07    .044       0 1015.85     .09       0
Bank Sta=963.07,1015.85
Exp/Cntr=0.3,0.1

Type RM Length L Ch R = 1 ,198005.1,806.22,793.4,774.51
BEGIN DESCRIPTION:
10737.11
END DESCRIPTION:
XS GIS Cut Line= 4
  1120807.777424   665560.508299  1119780.125374   665995.814595
  1119657.382377   666011.395722   1119088.50569   666331.652252
#Sta/Elev= 30
       0  1186.8  110.25 1154.71  181.77 1128.84   200.7 1123.84  219.96 1124.33
  230.99 1118.69  247.46 1117.89  320.51 1096.57  343.76  1094.5  375.81 1085.64
  395.71 1075.14  417.89 1069.73  437.22 1057.01  467.17 1044.42  732.37 1026.53
 1008.73  1021.2 1122.38 1022.14 1154.26 1016.72 1180.75 1014.57 1207.18 1021.05
 1369.35 1022.03 1395.31 1028.86 1432.14 1031.98 1467.33 1057.85 1497.11 1071.84
  1609.3 1114.27 1652.45 1128.22 1762.72  1151.1 1821.01 1150.13  1892.6 1142.98
#Mann= 3 , 0 , 0
       0     .12       0 1154.26    .043       0 1207.18     .14       0
#XS Ineff= 2 , 0
          950.41 1026.37
Permanent Ineff=
       F       F
Bank Sta=1154.26,1207.18
Exp/Cntr=0.3,0.1

Type RM Length L Ch R = 1 ,197211.7,1005.19,1000,998.18
BEGIN DESCRIPTION:
9943.711
END DESCRIPTION:
XS GIS Cut Line= 3
  1119849.134017   665044.200766  1119257.644003   665421.708349
   1118746.42063   665880.866427
#Sta/Elev= 30
       0 1128.29   41.55 1091.71  124.79 1087.59  164.78 1069.03  234.37 1027.88
  270.88 1023.85   456.3 1019.51  648.65 1017.68     661 1019.69  674.53 1017.94
   701.7 1012.12  731.12 1018.12  784.93 1019.77  845.11 1017.18  867.82 1022.97
  925.02 1019.43  960.55 1021.35  978.08 1026.13  989.41 1033.01 1007.68 1049.08
 1022.17 1057.06 1145.25 1094.42 1200.76 1107.45 1230.15  1110.9 1255.61 1118.29
 1294.52 1119.22 1307.37 1113.94 1319.44 1111.74 1351.59  1122.5 1388.84 1128.48
#Mann= 3 , 0 , 0
       0     .14       0  674.53    .043       0  731.12     .14       0
#XS Ineff= 2 , 0
                          869.93         1027.95
Permanent Ineff=
       F       F
Bank Sta=674.53,731.12
Exp/Cntr=0.3,0.1

Type RM Length L Ch R = 1 ,196211.7,950.58,971.91,992.08
BEGIN DESCRIPTION:
8943.711
END DESCRIPTION:
XS GIS Cut Line= 3
  1119277.338001   664189.379115  1118783.467075   664650.074399
  1118106.314362   665241.363749
#Sta/Elev= 30
       0 1075.34   31.24 1060.91   98.13 1046.89  117.81 1039.65  123.01 1034.43
  170.72 1028.09  306.86 1019.65  385.33 1019.25  431.39 1014.21  619.36  1015.7
  652.27 1011.24  675.39 1008.62  692.37 1009.63  705.62 1014.28  850.39 1013.15
  880.27 1019.41  909.32 1013.07 1063.96 1022.65 1106.26 1034.45 1155.53 1057.07
 1187.88 1075.94 1240.94 1078.27    1283 1112.73 1362.28 1131.41 1447.01 1133.54
 1482.01 1146.13 1492.72 1153.22 1515.16 1155.67 1529.87 1165.23 1574.36 1178.84
#Mann= 3 , 0 , 0
       0     .14       0  652.27    .043       0  705.62     .14       0
#XS Ineff= 2 , 0
                          879.12         1025.49
Permanent Ineff=
       F       F
Bank Sta=652.27,705.62
Exp/Cntr=0.3,0.1