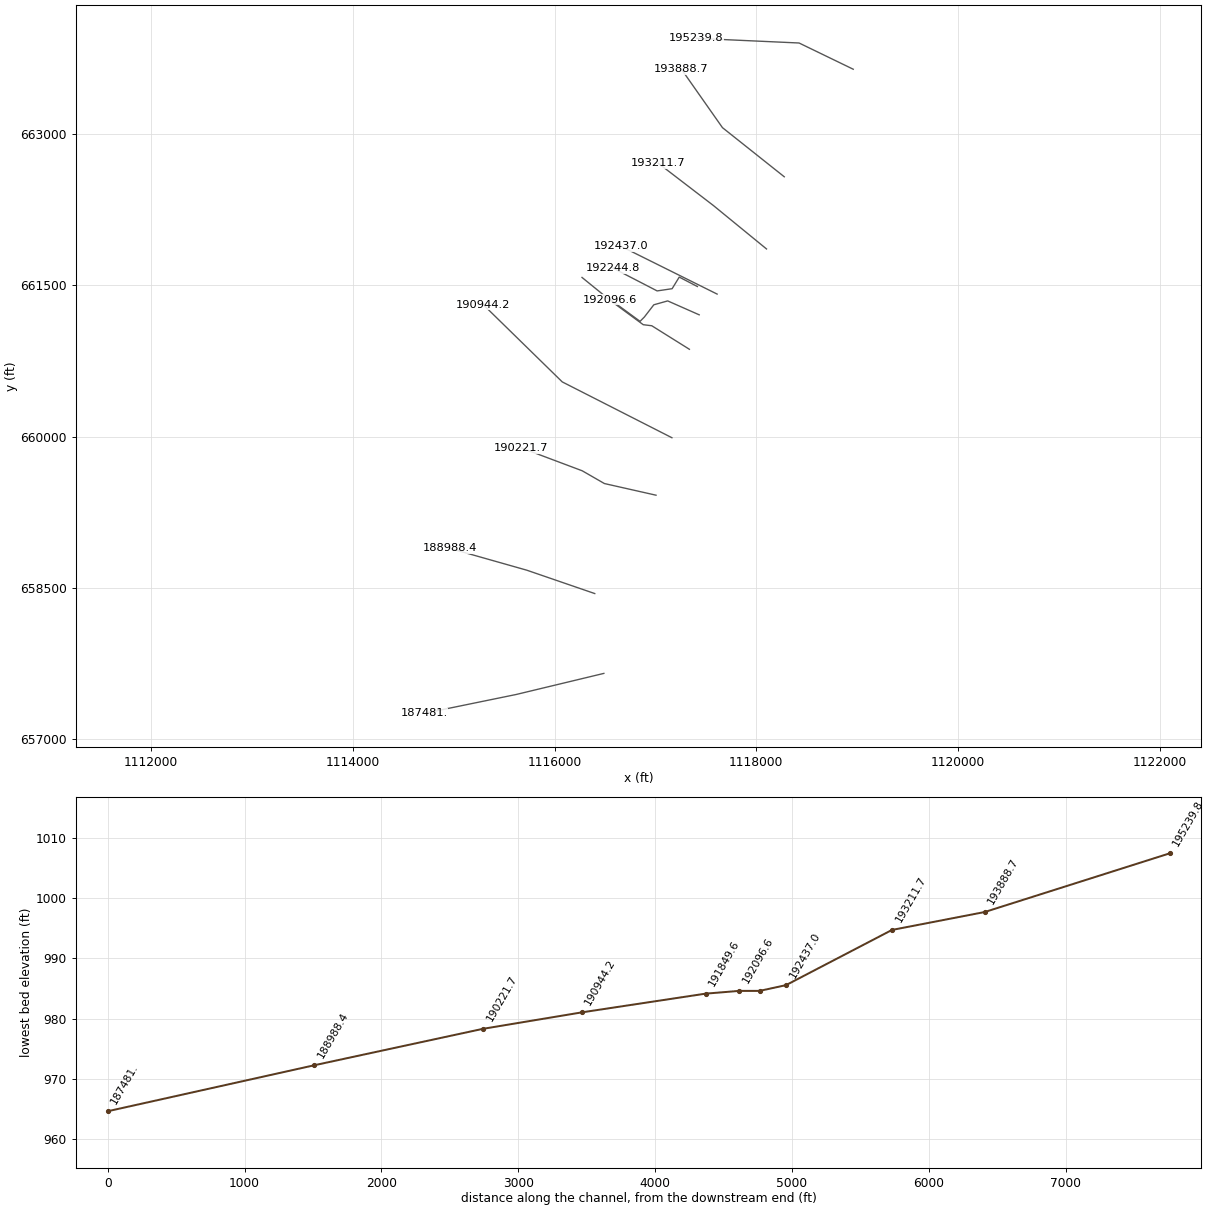
HEC-RAS study 2ndBroadRv.prj: 2ndBroadRv

--- 2ndBroadRv.g01 (geometry) --- (continued)

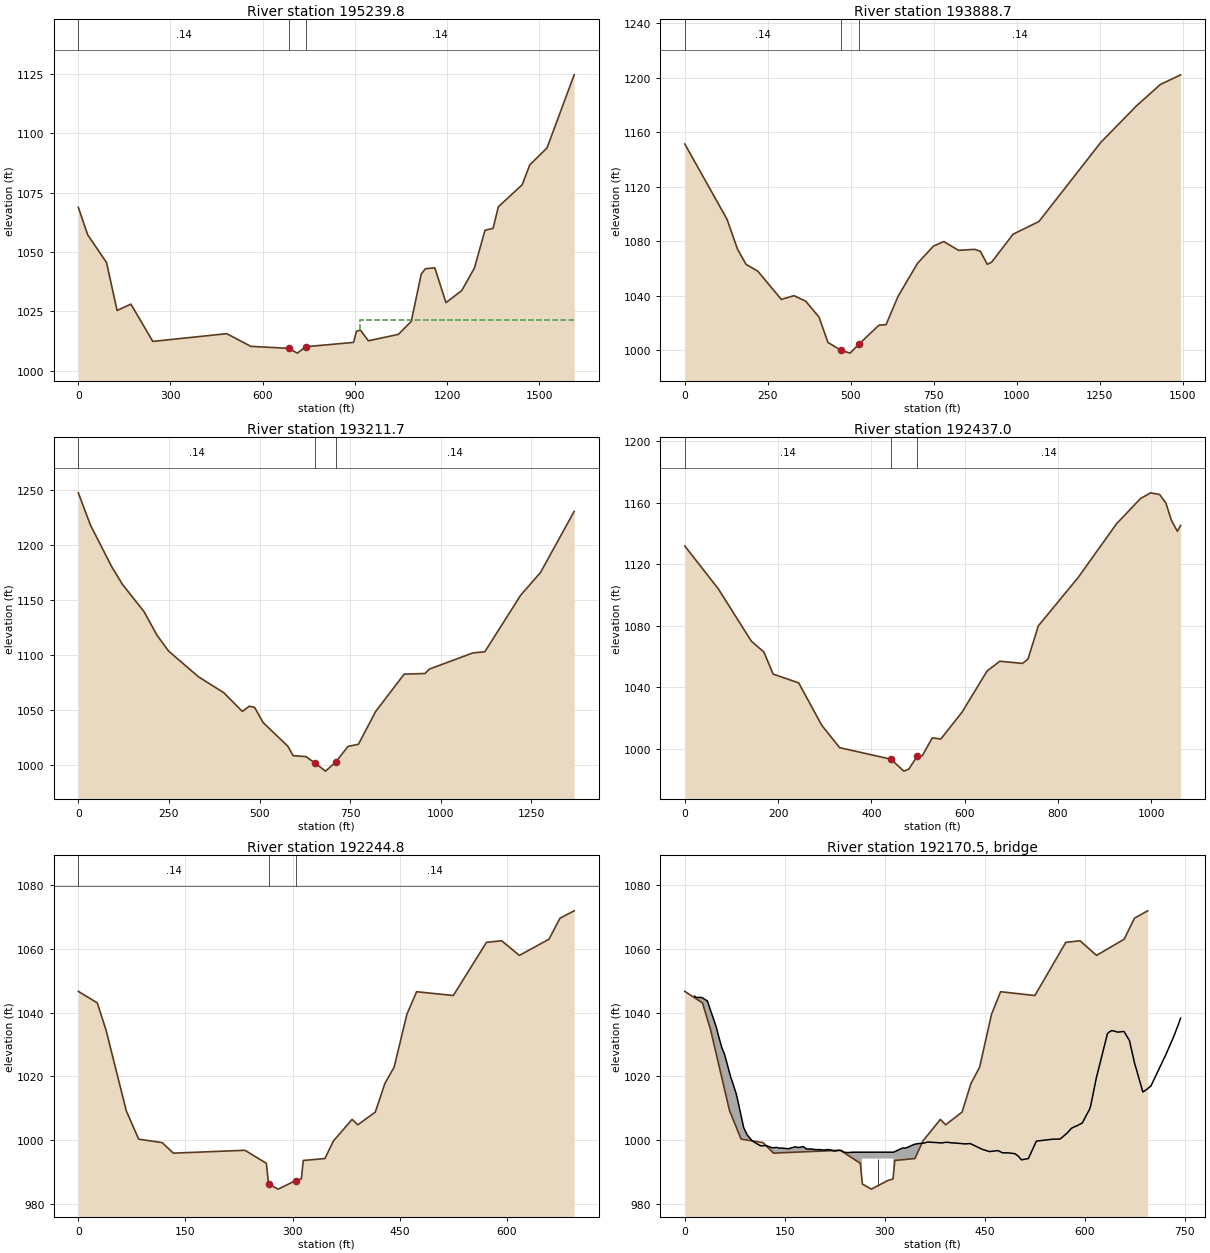
Type RM Length L Ch R = 1 ,195239.8,1367.68,1351.11,1330.02
BEGIN DESCRIPTION:
7971.796
END DESCRIPTION:
XS GIS Cut Line= 3
   1118960.63833   663641.749847  1118423.803671   663901.779132
  1117407.359995   663948.023051
#Sta/Elev= 30
       0 1068.74   30.49  1057.2   91.81 1045.53  126.16 1025.34  171.04 1028.03
   242.5 1012.34  483.25  1015.6  561.51 1010.26  684.62 1009.42  712.79 1007.41
  740.98 1010.12  896.02 1011.92  905.28 1016.62  918.11 1017.11  944.29  1012.6
 1041.87  1015.3 1083.84  1020.8 1116.18 1040.66 1129.51 1042.91 1160.35 1043.33
 1196.76 1028.66 1248.05 1033.73  1289.5 1043.27 1323.64  1059.1 1350.18 1059.94
 1367.11 1068.98 1444.66 1078.24 1469.51 1086.61 1525.78 1093.79 1613.99 1124.52
#Mann= 3 , 0 , 0
       0     .14       0  684.62    .043       0  740.98     .14       0
#XS Ineff= 2 , 0
                          917.08         1021.26
Permanent Ineff=
       F       F
Bank Sta=684.62,740.98
Exp/Cntr=0.3,0.1

Type RM Length L Ch R = 1 ,193888.7,677.31,676.98,677.47
BEGIN DESCRIPTION:
6620.689
END DESCRIPTION:
XS GIS Cut Line= 3
  1118277.012494    662575.45004  1117664.130906   663062.612306
  1117256.038894   663643.771454
#Sta/Elev= 30
       0 1151.38  127.36 1095.95  158.74 1074.07  184.35 1062.95  219.83 1057.91
  290.65 1037.14  328.81  1039.9  364.05 1035.86  404.23 1024.13  431.14 1005.53
  469.71  999.81  497.59  997.68  525.99 1004.69  584.74 1018.21  605.99  1018.6
  641.83 1039.24  700.66 1063.64  748.81 1076.34  779.93 1079.68  824.27 1073.23
  872.99 1073.95  889.88 1072.54  910.99 1062.92  924.51 1064.69  988.51 1085.07
 1066.27 1094.38 1252.61 1152.55 1361.03 1179.59 1432.14 1195.11 1493.04 1202.19
#Mann= 3 , 0 , 0
       0     .14       0  469.71    .043       0  525.99     .14       0
Bank Sta=469.71,525.99
Exp/Cntr=0.3,0.1

Type RM Length L Ch R = 1 ,193211.7,767.99,774.75,780.53
BEGIN DESCRIPTION:
5943.711
END DESCRIPTION:
XS GIS Cut Line= 3
  1118100.826921   661860.023888  1117572.921636   662291.666174
  1117028.589302   662708.905106
#Sta/Elev= 30
       0 1247.16   33.34 1217.94   92.24 1180.06  121.69 1164.12   181.2 1139.41
  217.36  1117.8  249.27 1103.52  331.51 1080.28  401.04  1065.9  452.49 1048.86
  471.55  1053.6  486.19 1052.56  509.93 1038.71   578.2 1017.24  592.42 1008.73
  627.89  1007.9  653.59 1001.83  681.94  994.71  710.02 1002.91  743.85 1017.11
  772.74 1019.07   820.2 1048.83  898.82 1082.68  956.48 1083.28  968.75 1087.32
 1088.51 1101.96 1121.33 1102.98 1220.21 1154.28 1274.91 1174.89 1367.76 1230.29
#Mann= 3 , 0 , 0
       0     .14       0  653.59    .043       0  710.02     .14       0
Bank Sta=653.59,710.02
Exp/Cntr=0.3,0.1

Type RM Length L Ch R = 1 ,192437.0,169.72,192.18,214.64
BEGIN DESCRIPTION:
5168.957
END DESCRIPTION:
XS GIS Cut Line= 2
   1117611.30578   661412.442417  1116659.186849   661885.750099
#Sta/Elev= 30
       0 1131.77   71.67 1104.05  142.55 1070.03  169.68 1062.89  189.45 1048.57
  244.25 1042.87   293.6 1015.38  332.03 1000.78  441.77  993.34  469.67  985.55
  480.36  986.86  498.42  995.19  509.32   995.6  530.67 1007.14  549.13 1006.43
  594.69 1023.91   648.2 1050.58  675.56 1056.94  724.09 1055.53  735.96 1058.32
  758.07 1079.89  843.65 1111.35  925.75 1146.19  977.05 1162.57  998.84 1166.32
  1018.2 1165.23 1031.71 1159.69 1043.35 1148.58 1056.26 1141.32 1063.27 1145.18
#Mann= 3 , 0 , 0
       0     .14       0  441.77    .042       0  498.42     .14       0
Bank Sta=441.77,498.42
Exp/Cntr=0.5,0.3

Type RM Length L Ch R = 1 ,192244.8,141.57,148.25,156.86
BEGIN DESCRIPTION:
4976.778  Upstream xs of Bridge 37111-0395
END DESCRIPTION:
XS GIS Cut Line= 5
  1117415.514391   661487.463949  1117235.682178   661580.976696
  1117165.202565   661465.909559  1117016.605993   661443.895248
  1116577.496373    661670.89278
#Sta/Elev= 30
       0  1046.7  26.517  1043.1  38.749  1034.6  67.175  1009.2  84.499  1000.3
  117.45   999.2 133.077   995.9 233.416   996.8 263.397   992.7 266.438   986.2
 279.873   984.6 304.622   987.3   312.4   987.8 315.087   993.6 345.351   994.2
  357.23   999.7 383.464  1006.5 391.454  1004.8 415.991  1008.8 429.426  1017.8
 442.366  1022.9 460.185  1039.5 473.832  1046.6 525.239  1045.4 571.696  1062.1
  592.98  1062.6 617.799    1058 659.306  1063.1 674.721  1069.7  694.52    1072
#Mann= 3 , 0 , 0
       0     .14       0 266.438    .042       0 304.622     .14       0
#XS Ineff= 2 , 0
       0 220.971   996.1 357.867       0   996.1
Permanent Ineff=
       F       F
Bank Sta=266.438,304.622
Skew Angle= 45
Exp/Cntr=0.5,0.3

Type RM Length L Ch R = 3 ,192170.5,,,
BEGIN DESCRIPTION:
4902.502  Bridge : 37111-0395
END DESCRIPTION:
Bridge Culvert--1,0,-1,-1, 0
Deck Dist Width WeirC Skew NumUp NumDn MinLoCord MaxHiCord MaxSubmerge Is_Ogee
63.3,22,2.6,45, 150, 127, 996.2, , 0.95, 0, 0,0,,
  14.708  17.041  22.415  25.385  33.093  33.588    33.8  42.426  47.235   50.77
  55.296  59.821  69.014  69.862  71.701  76.792  79.055  88.388  93.338 101.046
   105.5 111.864 114.056 116.602  120.42 123.107 130.956 131.734 132.088 138.522
 140.714  147.22 148.917 154.715 155.281 155.422 155.846 164.119 166.736 168.433
  170.13 172.534 177.484 182.716 183.282 183.848  190.99 192.333 197.566 204.425
 205.556 206.475  210.93 212.132 216.728 218.425 222.385 224.294 225.779 232.072
 236.103 238.578  242.82  246.71 251.518 252.225 253.003 265.731 265.731 313.107
 313.107 326.683 331.492 344.856 350.089 357.301  363.17 364.372 370.736 371.231
 371.585 377.312 383.888  385.09 385.939 390.747 394.283 401.707 404.889  415.92
 420.092 426.668 427.517 428.365 446.326 449.508 454.175 457.074 461.034 469.802
 476.802  483.59 493.207  495.54 500.632 505.086 515.481 526.724  527.36 527.997
 552.958 561.726  564.13 573.605  580.11  584.07 585.343 586.687 596.515  602.95
 607.193 609.102 616.809 617.446 632.295 633.285 634.133 636.538 640.639 642.831
  649.76 657.609 659.094 660.438 667.085 674.792 675.358  676.63 687.237 692.399
 699.399 701.026 703.713 713.683 720.825 721.885 731.785 733.765 740.341 743.947
  1045.2  1044.8  1044.8  1044.8  1043.8  1043.8  1043.7  1038.5  1035.5  1032.6
  1029.2  1026.8  1019.7  1019.2  1018.1  1014.8  1012.9  1003.9  1001.7   999.8
   999.2   998.4   998.2   998.2   998.3   998.2   997.6   997.6   997.6   997.7
   997.5   997.5   997.4   997.3   997.3   997.3   997.3   997.8   997.9   997.7
   997.7   997.7     998   997.2   997.2   997.2   997.2   997.1     997     997
   996.9   996.9   996.9     997     997   996.9   996.7   996.6   996.6   996.8
   996.6   996.2   996.1   996.1   996.2   996.1   996.2   996.2   996.2   996.2
   996.2   997.5   997.5   998.7   998.9     999   999.3   999.4   999.3   999.3
   999.3   999.2   999.1   999.1   999.1   999.3   999.3   999.1   999.1   998.9
   998.8   998.9   998.9   998.9   997.1   996.9   996.6   996.4   996.5   996.7
     996     996   995.8   995.7   994.9   993.8   994.2   999.3   999.6   999.7
  1000.3  1000.3  1000.5  1002.2  1003.7  1004.1  1004.3  1004.3  1005.4    1008
  1009.6  1010.9  1018.7  1019.5  1031.9  1032.8  1033.4  1033.9  1034.4  1034.3
  1033.9  1034.1  1034.1  1033.6  1031.3  1024.3  1023.7  1022.9  1015.1  1015.8
    1017  1017.7  1018.9  1023.3  1026.4  1026.9  1031.6  1032.6  1036.2  1038.3
                                                                                
                                                                                
                                                                                
                                                                                
                                                                                
                                                                                
                                                                   994.2   994.2
                                                                                
                                                                                
                                                                                
                                                                                
                                                                                
                                                                                
                                                                                
                                                                                
  30.193  32.456   37.83    40.8  48.508  49.003  49.215  57.912   62.65  66.185
  70.711  75.307  84.429  85.277  87.116  92.207  94.469 103.874 108.753  116.46
 120.915 127.279 129.471 146.442 147.149 147.502 156.129 164.332  170.13 170.696
 170.837 171.261 198.131 198.697 199.333 206.404 207.748 212.981 219.839 220.971
  221.89 226.345 227.547 232.143 233.911   237.8  239.78 241.194 253.993 258.235
 262.195 266.933  267.64 268.418 281.216 281.216 328.593 328.593 342.098 352.917
 367.696 379.787 386.151 386.646     387 392.727 401.354 406.162 417.193 420.304
 425.678 431.335 435.507 442.083 443.002  443.78 448.447 461.811 464.923  469.59
 476.449 492.217 499.005 508.622 510.955 516.047 520.501 530.896 542.139 542.775
 568.372 579.545  589.02 595.596 599.485 600.758 602.172 612.001 618.365 622.607
 624.587 632.224 632.861  647.71   648.7 649.619 651.952 656.054 673.024 674.509
 675.853 682.499 690.207 690.843 692.045 702.723 707.814 714.814 716.441 719.128
 729.098  736.24 737.371   747.2  749.18 755.826 759.362
  1045.2  1044.8  1044.8  1044.8  1043.8  1043.8  1043.7  1038.5  1035.5  1032.6
  1029.2  1026.8  1019.7  1019.2  1018.1  1014.8  1012.9  1003.9  1001.7   999.8
   999.2   998.4   998.2   997.6   997.6   997.6   997.5   997.4   997.3   997.3
   997.3   997.3   997.2   997.2   997.2   997.2   997.1     997     997   996.9
   996.9   996.9     997     997   996.9   996.7   996.6   996.6   996.2   996.1
   996.1   996.2   996.1   996.2   996.2   996.2   996.2   996.2   997.5   999.2
   999.2   999.4   999.3   999.3   999.3   999.2   999.1   999.3   999.1   999.1
   999.2   998.9   998.8   998.9   998.9   998.9   997.7   997.1   996.9   996.6
   996.5     996     996   995.8   995.7   994.9   993.8   994.2   999.3   999.6
  1000.3  1000.5  1002.2  1003.7  1004.1  1004.3  1004.3  1005.4    1008  1009.6
  1010.9  1018.7  1019.5  1031.9  1032.8  1033.4  1033.9  1034.4  1034.1  1034.1
  1033.6  1031.3  1024.3  1023.7  1022.9  1015.1  1015.8    1017  1017.7  1018.9
  1023.3  1026.4  1026.9  1031.6  1032.6  1036.2  1038.3
                                                                                
                                                                                
                                                                                
                                                                                
                                                                                
                                           994.2   994.2
                                                                                
                                                                                
                                                                                
                                                                                
                                                                                
                                                                                
                                                        
Pier Skew= 45
Pier Skew, UpSta & Num, DnSta & Num=  ,289.801, 2 ,305.23, 2 , 0 , 0 , 0 ,,
       1       1
   983.6   994.7
       1       1
   983.6   994.7
BR Coef=-1 , 1 , 0 ,, 0 ,,,0.8,0,1.2,0,
WSPro=,,,, 1 ,,,, 0 ,,,, 0 ,,,,-1 ,-1 ,-1 , 0 , 0 , 0 , 0 , 0
BC Design=,, 0 ,, 0 ,,,,,,

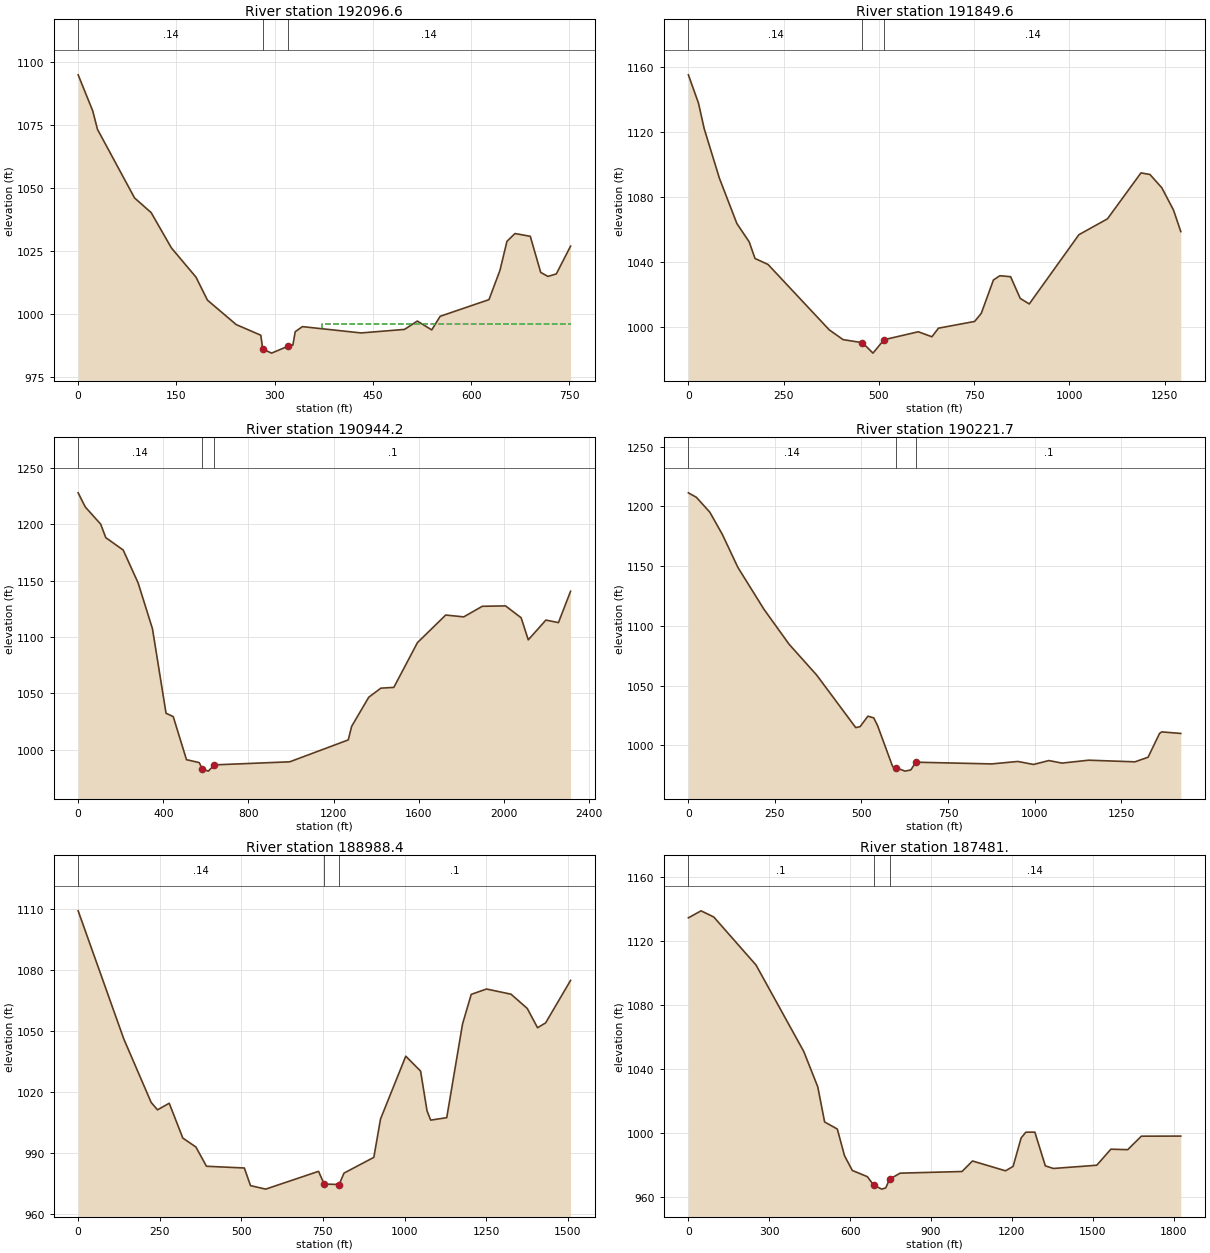
Type RM Length L Ch R = 1 ,192096.6,265.76,246.99,226.06
BEGIN DESCRIPTION:
4828.53  Down stream xs of Bridge 37111-0395
END DESCRIPTION:
XS GIS Cut Line= 6
  1117433.497573   661206.925751  1117121.173941   661344.830867
  1116983.584503    661306.30581  1116890.023689   661185.227117
  1116847.244671   661142.186174  1116552.319866   661357.984794
#Sta/Elev= 30
       0  1094.9  22.274  1080.6  29.486  1073.3  86.126  1046.1  111.44  1040.3
 142.411  1026.3 179.959  1014.7 197.424  1005.6 241.406   995.9 278.883   991.7
 281.923   986.2 295.359   984.6 320.107   987.3 327.885   987.8 331.492   993.1
 342.452   995.1 432.042   992.6 498.369     994 517.956   997.3 539.947   993.8
 552.816   999.2 627.345  1005.8 644.104  1017.4 654.781  1028.9 667.014    1032
 690.419  1030.9 706.329  1016.6  717.36    1015 730.158    1016 751.937    1027
#Mann= 3 , 0 , 0
       0     .14       0 281.923    .042       0 320.107     .14       0
#XS Ineff= 2 , 0
       0 236.669   996.2  373.07       0   996.2
Permanent Ineff=
       F       F
Bank Sta=281.923,320.107
Skew Angle= 45
Exp/Cntr=0.5,0.3

Type RM Length L Ch R = 1 ,191849.6,915.87,905.38,894.83
BEGIN DESCRIPTION:
4581.54
END DESCRIPTION:
XS GIS Cut Line= 5
  1117336.388207   660865.244595  1116963.275143    661098.61343
  1116878.951918   661108.938699  1116559.513147   661343.598231
  1116271.781624   661577.380077
#Sta/Elev= 30
       0 1154.99   26.51 1137.62   41.44    1122   81.35 1091.55  127.28 1063.69
  159.58 1052.45   174.9 1042.24  209.08 1038.56  369.79   998.4  406.07  992.43
  456.77  990.54  484.41  984.14  513.32  992.36  603.37  997.26  639.03  994.19
  656.32  999.46  751.26  1003.6  768.63 1008.58  800.42 1029.03  817.26 1031.65
  845.55 1031.06  870.78 1017.73  894.52 1014.34 1024.79 1056.85 1099.62 1066.56
 1187.62 1094.78 1211.11 1093.82 1242.29 1085.68  1273.1 1071.92 1292.14 1058.73
#Mann= 3 , 0 , 0
       0     .14       0  456.77    .042       0  513.32     .14       0
Bank Sta=456.77,513.32
Exp/Cntr=0.3,0.1

Type RM Length L Ch R = 1 ,190944.2,724.02,722.53,720.96
BEGIN DESCRIPTION:
3676.165
END DESCRIPTION:
XS GIS Cut Line= 4
  1117163.017877   659988.402235  1116554.802373   660298.047494
  1116075.800278   660541.909698  1115293.986193    661306.30581
#Sta/Elev= 30
       0 1227.81   33.63 1215.22  105.94 1200.02   129.7 1188.08  211.53 1177.09
   281.7 1147.94  349.14 1107.26  412.89 1032.34  446.66 1029.38  508.94  991.18
  568.83  988.59  582.38  983.09  611.22  981.03  640.28  986.57  994.04  989.29
 1268.99 1008.71  1284.9 1020.74 1365.19 1046.54 1422.31 1054.61 1483.05 1055.29
 1593.91 1094.96  1726.7 1119.43  1811.5 1117.81 1898.57  1127.2    2008 1127.54
 2081.24 1117.01 2114.69 1097.45 2197.47 1114.97 2256.38 1112.73 2313.41 1140.51
#Mann= 3 , 0 , 0
       0     .14       0  582.38    .042       0  640.28      .1       0
Bank Sta=582.38,640.28
Exp/Cntr=0.3,0.1

Type RM Length L Ch R = 1 ,190221.7,1225.73,1233.28,1240.49
BEGIN DESCRIPTION:
2953.633
END DESCRIPTION:
XS GIS Cut Line= 4
  1117005.598815   659418.578693  1116493.766121   659534.153863
  1116273.623002   659660.736123  1115671.142115   659886.957478
#Sta/Elev= 30
       0  1211.4   23.12 1207.65   61.78 1195.25   97.93 1176.68  142.86 1149.01
  218.38 1113.83  291.22 1084.46  370.54 1058.76  483.45 1014.73   496.1 1015.61
  518.56 1024.34  535.47 1022.87  546.54 1016.37  588.69   983.1  594.85  980.15
  598.64  981.29  625.92   978.3  642.46   979.3  657.05  985.78  876.39  984.34
  951.39   986.4  996.91  983.89 1041.25  987.15 1079.21  985.02 1156.08  987.46
 1289.81  986.08 1327.73  989.94 1360.81 1009.86 1367.15 1011.16 1422.21 1009.87
#Mann= 3 , 0 , 0
       0     .14       0  598.64    .042       0  657.05      .1       0
Bank Sta=598.64,657.05
Exp/Cntr=0.3,0.1

Type RM Length L Ch R = 1 ,188988.4,1490.39,1507.43,1520.5
BEGIN DESCRIPTION:
1720.354
END DESCRIPTION:
XS GIS Cut Line= 3
  1116398.032747   658443.493131  1115725.091792   658674.888515
  1114958.045029   658892.232783
#Sta/Elev= 30
       0 1108.93  139.72 1046.05  223.66 1014.85  243.15 1011.19  279.03 1014.43
  320.77  997.31  360.82  992.94   393.2  983.48   509.2  982.63  528.14  973.97
  574.62  972.25  736.67  980.99   753.7  974.74  799.64  974.52  814.62  980.12
  905.99  987.85  926.55  1006.7 1003.89 1037.54  1049.3 1030.21 1069.01  1010.7
 1080.26 1006.13  1129.4 1007.35 1177.86 1053.39 1204.49 1067.91 1251.29 1070.53
 1326.35 1067.99 1375.98 1061.02 1407.71 1051.51 1432.47 1053.91 1508.86 1074.76
#Mann= 3 , 0 , 0
       0     .14       0   753.7    .042       0  799.64      .1       0
#XS Ineff= 2 , 0
          509.14  982.63
Permanent Ineff=
       F       F
Bank Sta=753.7,799.64
Exp/Cntr=0.3,0.1

Type RM Length L Ch R = 1 ,187481. ,248.45,212.92,237.36
BEGIN DESCRIPTION:
212.921
END DESCRIPTION:
XS GIS Cut Line= 3
  1116488.262554   657651.930313  1115618.697303   657442.794373
  1114705.824965   657255.587717
#Sta/Elev= 30
       0 1134.29   47.18 1138.66   94.38 1134.78  250.93 1104.76  428.09 1050.66
   479.9 1028.57  505.34 1006.63  552.34  1002.2  579.01  985.55  607.94  976.32
  663.73  972.42  687.17  967.17  716.88  964.63  731.74  965.37   746.6  970.87
  785.24  974.62 1014.83  975.65 1053.59  982.23 1176.42  976.08 1204.39  978.87
 1233.98  996.61 1251.51 1000.23 1285.02 1000.26  1323.9  979.16 1353.88  977.55
 1514.59  979.57 1566.96   989.6 1629.37  989.31 1679.97  997.74 1826.23   997.8
#Mann= 3 , 0 , 0
       0      .1       0  687.17    .042       0   746.6     .14       0
Bank Sta=687.17,746.6
Exp/Cntr=0.3,0.1
Stream Node=2ndBroadRv      ,Main            , 0 , 0 ,Upstream end
Stream Node=2ndBroadRv      ,Main            , 0 , 1 ,Downstream end

Chan Stop Cuts=-1
Use User Specified Reach Order=0
User Specified Reach Order=2ndBroadRv      ,Main