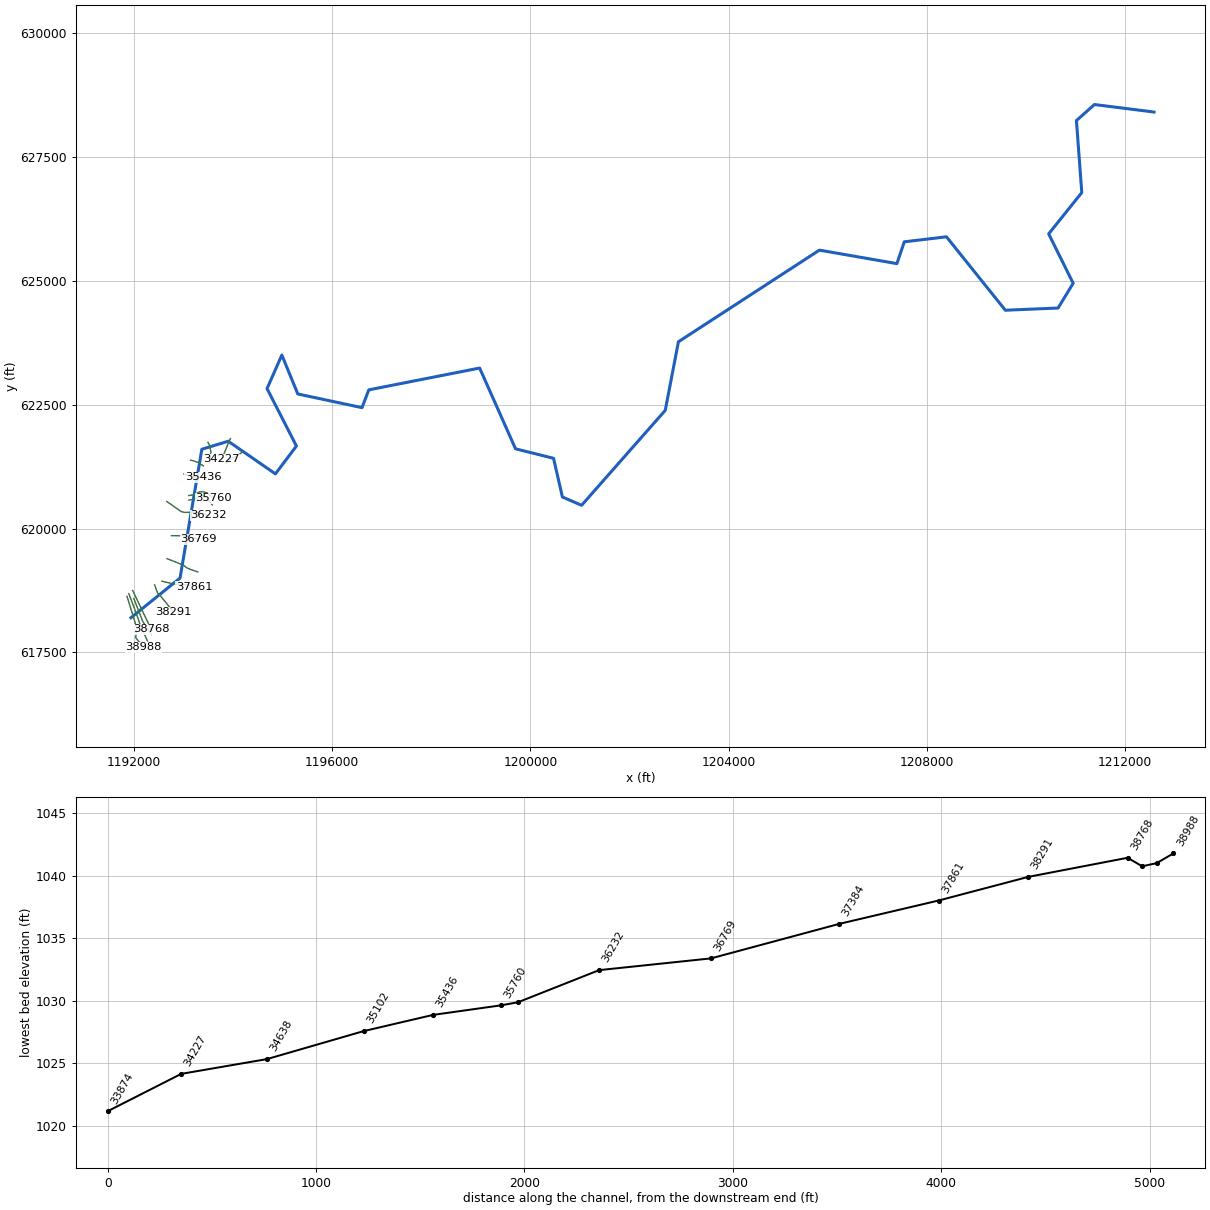
--- lds_hinton_crk.prj (project) ---

Proj Title=Hinton Creek Limited Detail Study
Current Plan=p02
Default Exp/Contr=0.3,0.1
English Units
Geom File=g01
Flow File=f02
Flow File=f01
Flow File=f03
Plan File=p02
Y Axis Title=Elevation
X Axis Title(PF)=Main Channel Distance
X Axis Title(XS)=Station
BEGIN DESCRIPTION:
Hinton Creek
END DESCRIPTION:
DSS Export Rating Curves= 0
DSS Export Rating Curve Sorted= 0
DSS Export Volume Flow Curves= 0
DXF OffsetX= 0
DXF OffsetY= 0
DXF ScaleX= 1
DXF ScaleY= 10

--- lds_hinton_crk.p02 (plan) ---

Plan Title=Floodway Run
Program Version=3.13
Short Identifier=Floodway
Geom File=g01
Flow File=f02
Subcritical Flow
K Sum by GR= 0
Std Step Tol= 0.01
Critical Tol= 0.01
Num of Std Step Trials= 20
Max Error Tol= 0.3
Flow Tol Ratio= 0.001
Split Flow NTrial= 30
Split Flow Tol= 0.02
Split Flow Ratio= 0.02
Log Output Level= 0
Friction Slope Method= 1
Unsteady Friction Slope Method= 2
Unsteady Bridges Friction Slope Method= 1
Parabolic Critical Depth
Global Vel Dist= 0 , 0 , 0
Global Log Level= 0
CheckData=True
Encroach Param=-1 ,10,10, 2
Encroach River=Hinton Creek
Encroach Reach=Reach-1
Encroach Node=38988
       1 4732.42 5280.71
Encroach Node=38907
       1 4792.47    5168
Encroach Node=38838
       1 4902.35 5128.24
Encroach Node=38768
       1 4824.73 5052.91
Encroach Node=38291
       1 4941.69 5188.13
Encroach Node=37861
       1    4838 5098.71
Encroach Node=37384
       1 4764.48    5030
Encroach Node=36769
       1  4809.2 5047.41
Encroach Node=36232
       1 4796.79 5105.58
Encroach Node=35843
       1    4936    5064
Encroach Node=35760
       1  4978.3 5030.55
Encroach Node=35436
       1 4961.73 5068.62
Encroach Node=35102
       1  4977.7  5034.4
Encroach Node=34638
       1  4978.9    5033
Encroach Node=34227
       1 4976.21 5180.25
Encroach Node=33874
       1  4971.2  5023.4
Encroach Node=33357
       1  4921.5  5025.2
Encroach Node=32885
       1 4819.26 5028.57
Encroach Node=32574
       1 4979.24  5091.5
Encroach Node=32137
       1 4953.01 5021.12
Encroach Node=31789
       1  4975.3  5028.7
Encroach Node=31473
       1    4952 5032.25
Encroach Node=31240
       1  4943.5    5030
Encroach Node=30978
       1    4960    5025
Encroach Node=30601
       1  4976.6 5070.74
Encroach Node=30150
       1  4972.9 5176.84
Encroach Node=29822
       1 4981.91  5143.9
Encroach Node=29459
       1 4969.66 5069.32
Encroach Node=29242
       1  4946.5    5018
Encroach Node=28934
       1 4940.16 5031.06
Encroach Node=28482
       1  4961.5    5041
Encroach Node=28100
       1    4979    5059
Encroach Node=27797
       1    4966    5032
Encroach Node=27519
       1    4935    5030
Encroach Node=27147
       1  4984.4 5029.54
Encroach Node=26855
       1  4978.6 5024.31
Encroach Node=26479
       1    4975    5025
Encroach Node=26143
       1 4975.03 5026.85
Encroach Node=25675
       1    4920    5015
Encroach Node=25219
       1 4967.33    5023
Encroach Node=24798
       1    4976    5025
Encroach Node=24040
       1 4957.65    5070
Encroach Node=23620
       1  4916.5  5083.5
Encroach Node=23524
       1  4902.5 5075.36
Encroach Node=22987
       1 4943.48 5023.95
Encroach Node=22575
       1  4853.8  5026.3
Encroach Node=22027
       1    4975 5361.22
Encroach Node=21361
       1 4964.61  5075.2
Encroach Node=20938
       1 4913.25 5024.59
Encroach Node=20528
       1 4947.06    5023
Encroach Node=20033
       1  4974.3 5081.58
Encroach Node=19518
       1 4924.44 5064.75
Encroach Node=18952
       1 4941.41 5174.99
Encroach Node=18231
       1  4868.9 5475.99
Encroach Node=17624
       1  4896.5  5099.5
Encroach Node=17518
       1  4898.5  5105.5
Encroach Node=16761
       1 4968.87  5026.2
Encroach Node=16294
       1 4906.77  5122.6
Encroach Node=15248
       1 4974.31 5302.77
Encroach Node=14603
       1 4941.36 5384.21
Encroach Node=14095
       1  4975.8 5350.85
Encroach Node=13635
       1  4722.3 5115.91
Encroach Node=13101
       1    4640    5050
Encroach Node=13021
       1    4720    5150
Encroach Node=12515
       1    4760    5260
Encroach Node=11838
       1 4719.38  5036.7
Encroach Node=11424
       1 4885.84 5038.09
Encroach Node=10851
       1 4815.87  5041.2
Encroach Node=10373
       1 4917.24 5036.87
Encroach Node=10005
       1 4763.31  5028.7
Encroach Node=9484
       1  4759.1  5128.6
Encroach Node=9026
       1  4770.1  5026.6
Encroach Node=8475
       1 4929.72 5258.62
Encroach Node=7668
       1  4686.8 5220.86
Encroach Node=7011
       1    4897    5103
Encroach Node=6930
       1 4922.05 5055.86
Encroach Node=6367
       1 4774.31 5230.54
Encroach Node=5681
       1 4850.76 5032.92
Encroach Node=5062
       1  4965.2 5036.75
Encroach Node=4416
       1  4734.1  5027.8
Encroach Node=4043
       1  4924.8 5286.79
Encroach Node=3506
       1 4837.12 5461.79
Encroach Node=2792
       1 4715.23 5072.65
Encroach Node=1938
       1 4700.94 5197.23
Encroach Node=1399
       1 4939.29 5050.06
Encroach Node=1299
       1 4968.27 5042.83
Encroach Node=758
       1 4720.75 5140.77
BEGIN DESCRIPTION:
Floodway Run
END DESCRIPTION:
Computation Interval=1HOUR
Output Interval=1HOUR
Run HTab= 0
Run UNet= 0
Run PostProcess= 0
UNET Theta= 1
UNET Theta Warmup= 1
UNET ZTol= 0.02
UNET ZSATol= 0.05
UNET MxIter= 20
UNET MaxInSteps= 0
UNET DtIC= 0
UNET DtMin= 0
UNET MaxCRTS= 20
UNET WFStab= 2
UNET SFStab= 1
UNET WFX= 1
UNET SFX= 1
UNET DSS MLevel= 4
UNET DZMax Abort= 100
UNET Convert EG Bridges=-1
UNET Use Existing IB Tables=-1
UNET Froude Reduction=False
UNET Froude Limit= 1
UNET Froude Power= 10
Instantaneous Interval=1HOUR
Write IC File= 0
Echo Input=False
Echo Output=False
Write Detailed= 0
Detailed Automatic Start=False, 10

--- lds_hinton_crk.p01 (plan) ---

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Plan Title=Multiple Run
Short Identifier=Multiple
Geom File=g01
Flow File=f01
Encroach Param=-1 ,0,0, 0
Multiple Run

--- lds_hinton_crk.f02 (steady flow) ---

Flow Title=Floodway
Program Version=3.13
Number of Profiles= 2
Profile Names=100-year,100-FW
River Rch & RM=Hinton Creek,Reach-1         ,38988
    3530    3530
River Rch & RM=Hinton Creek,Reach-1         ,37861
    3730    3730
River Rch & RM=Hinton Creek,Reach-1         ,25675
    3950    3950
River Rch & RM=Hinton Creek,Reach-1         ,22575
    4000    4000
River Rch & RM=Hinton Creek,Reach-1         ,20528
    4490    4490
River Rch & RM=Hinton Creek,Reach-1         ,18952
    4660    4660
River Rch & RM=Hinton Creek,Reach-1         ,13101
    4970    4970
River Rch & RM=Hinton Creek,Reach-1         ,11838
    5060    5060
River Rch & RM=Hinton Creek,Reach-1         ,7011
    5380    5380
River Rch & RM=Hinton Creek,Reach-1         ,6367
    5550    5550
River Rch & RM=Hinton Creek,Reach-1         ,2792
    5640    5640
Boundary for River Rch & Prof#=Hinton Creek,Reach-1         , 1
Up Type= 0
Dn Type= 3
Dn Slope=0.001
Boundary for River Rch & Prof#=Hinton Creek,Reach-1         , 2
Up Type= 0
Dn Type= 3
Dn Slope=0.001
DSS Import GetInterval= 0
DSS Import GetPeak= 0
DSS Import FillOption= 0

--- lds_hinton_crk.f01 (steady flow) ---

Flow Title=Multiple
Number of Profiles=4
Profile Names=10-year,50-year,100-year,500-year
River Rch & RM= Hinton Creek,Reach-1,38988
    1482    2514    3042    4528
River Rch & RM= Hinton Creek,Reach-1,37861
    1570    2657    3213    4774
River Rch & RM= Hinton Creek,Reach-1,25675
    1669    2817    3403    5047
River Rch & RM= Hinton Creek,Reach-1,22575
    1693    2856    3449    5113
River Rch & RM= Hinton Creek,Reach-1,20528
    1911    3208    3867    5712
River Rch & RM= Hinton Creek,Reach-1,18952
    1989    3333    4015    5924
River Rch & RM= Hinton Creek,Reach-1,13101
    2131    3561    4286    6310
River Rch & RM= Hinton Creek,Reach-1,11838
    2173    3628    4365    6422
River Rch & RM= Hinton Creek,Reach-1,7011
    2318    3861    4640    6814
River Rch & RM= Hinton Creek,Reach-1,6367
    2395    3983    4784    7019
River Rch & RM= Hinton Creek,Reach-1,2792
    2438    4052    4866    7135
Boundary for River Rch & Prof#=Hinton Creek,Reach-1,1
Up Type=0
Dn Type=3
Dn Slope=0.005
Boundary for River Rch & Prof#=Hinton Creek,Reach-1,2
Up Type=0
Dn Type=3
Dn Slope=0.005
Boundary for River Rch & Prof#=Hinton Creek,Reach-1,3
Up Type=0
Dn Type=3
Dn Slope=0.005
Boundary for River Rch & Prof#=Hinton Creek,Reach-1,4
Up Type=0
Dn Type=3
Dn Slope=0.005

--- lds_hinton_crk.f03 (steady flow) ---

Flow Title=100-year Single
Number of Profiles=1
Profile Names=100-year
River Rch & RM= Hinton Creek,Reach-1,38988
    3042
River Rch & RM= Hinton Creek,Reach-1,37861
    3213
River Rch & RM= Hinton Creek,Reach-1,25675
    3403
River Rch & RM= Hinton Creek,Reach-1,22575
    3449
River Rch & RM= Hinton Creek,Reach-1,20528
    3867
River Rch & RM= Hinton Creek,Reach-1,18952
    4015
River Rch & RM= Hinton Creek,Reach-1,13101
    4286
River Rch & RM= Hinton Creek,Reach-1,11838
    4365
River Rch & RM= Hinton Creek,Reach-1,7011
    4640
River Rch & RM= Hinton Creek,Reach-1,6367
    4784
River Rch & RM= Hinton Creek,Reach-1,2792
    4866
Boundary for River Rch & Prof#=Hinton Creek,Reach-1,1
Up Type=0
Dn Type=3
Dn Slope=0.005

--- lds_hinton_crk.g01 (geometry) ---

Geom Title=Existing Conditions
Program Version=3.13

River Reach=Hinton Creek    ,Reach-1
Reach XY= 30
      1191943.75       618199.69        1192934.       619000.94
      1193373.88        621601.5        1193906.       621762.94
      1194858.25       621104.06      1195281.88       621666.56
        1194689.       622825.44      1194987.63       623503.38
      1195309.63       622716.94      1196604.75       622440.88
      1196741.88       622800.25        1198978.       623240.38
      1199702.38       621609.81      1200468.75       621418.44
      1200647.75       620637.19      1201035.13       620469.94
      1202722.38       622386.31      1202988.25       623770.88
      1205832.25       625620.94      1207395.75       625348.56
      1207545.25       625789.13      1208395.63       625890.19
      1209583.25       624407.75      1210647.38       624452.19
      1210951.88         624952.      1210457.38         625949.
      1211125.63         626783.      1211017.88       628236.75
      1211381.63       628560.06      1212583.75       628408.56

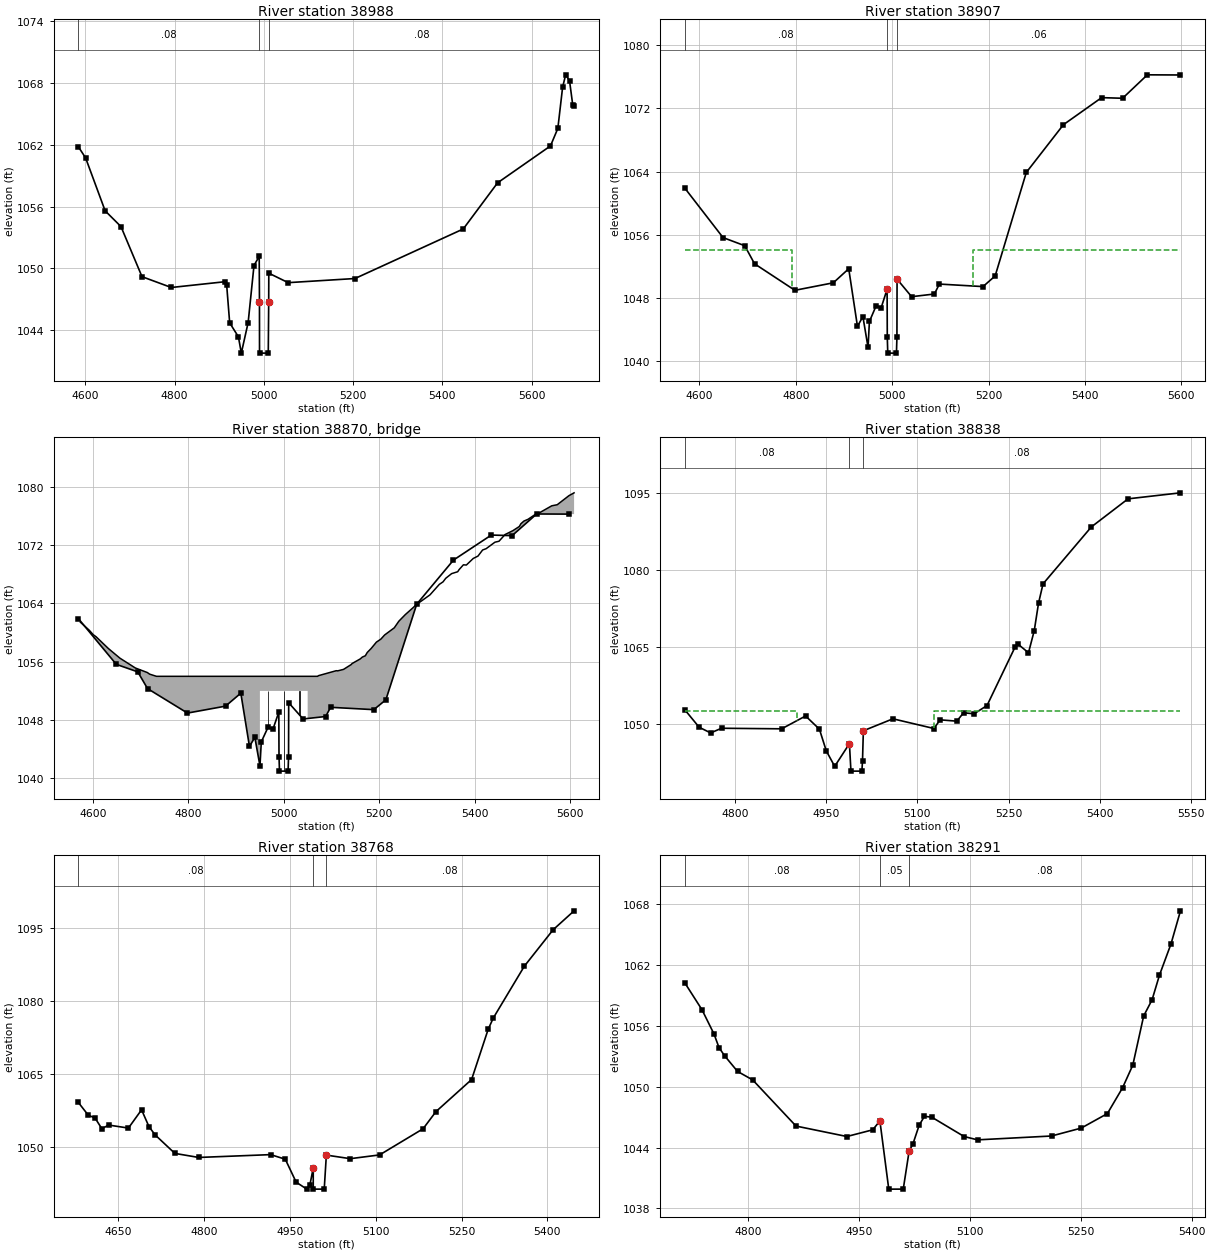
Type RM Length L Ch R = 1 ,38988   ,81,81,81
BEGIN DESCRIPTION:
XS 100
END DESCRIPTION:
XS GIS Cut Line= 4
       1191864.2       618631.24      1192060.76        617995.1
      1192038.49       617799.47      1192193.86       617605.66
#Sta/Elev= 30
  4584.1 1061.81  4600.4 1060.73  4644.2 1055.59  4679.7 1054.06  4726.8  1049.2
  4792.5 1048.15  4912.8 1048.71  4916.6 1048.37  4923.3 1044.72  4942.9 1043.36
  4949.4 1041.78  4964.7 1044.75  4977.8 1050.28  4989.5 1051.18 4990.07 1046.79
  4990.2 1041.78  5009.8 1041.78 5010.77 1046.77    5011 1049.54  5054.4 1048.62
  5204.1 1049.02  5446.8 1053.83  5523.8 1058.31  5642.3 1061.89  5658.8 1063.59
  5669.5 1067.59  5676.3 1068.79    5685 1068.22  5692.1  1065.9  5695.2  1065.8
#Mann= 3 ,-1 , 0
  4584.1     .08       0 4990.07     .05       0 5010.77     .08       0
Bank Sta=4990.07,5010.77
Exp/Cntr=0.5,0.3

Type RM Length L Ch R = 1 ,38907   ,69,69,69
BEGIN DESCRIPTION:
Hinton Creek Rd SR 1753 - US
END DESCRIPTION:
XS GIS Cut Line= 6
      1191899.73       618686.87      1192019.06       618373.45
      1192053.16       618273.92       1192089.1       618185.45
      1192116.01       618092.52      1192276.02       617730.54
#Sta/Elev= 30
  4569.7 1061.92  4649.2 1055.64  4694.2 1054.61  4714.6 1052.32  4798.3 1048.96
    4878 1049.91    4910 1051.69  4928.1 1044.39  4939.4 1045.63  4950.1 1041.72
  4952.9 1045.01  4967.1 1047.03  4977.2 1046.73  4989.6 1049.09    4990    1043
    4991    1041    5009    1041    5010    1043  5010.3 1050.37  5040.5 1048.15
  5087.7 1048.49  5098.1 1049.75  5188.6 1049.43  5213.8 1050.78  5278.4 1063.89
  5355.4 1069.94  5434.7 1073.37  5478.2 1073.29  5529.6 1076.26  5598.3 1076.24
#Mann= 3 ,-1 , 0
  4569.7     .08       0  4989.6     .05       0  5010.3     .06       0
#XS Ineff= 2 , 0
       0 4792.47  1054.1    5168       0  1054.1
Permanent Ineff=
       F       F
Bank Sta=4989.6,5010.3
Exp/Cntr=0.5,0.3

Type RM Length L Ch R = 3 ,38870   ,,,
BEGIN DESCRIPTION:
Hinton Creek Rd SR 1753
Structure ID: Hinton Creek Rd SR 1753
Approximate Survey Structure
END DESCRIPTION:
Bridge Culvert--1,0,-1,-1, 0
Deck Dist Width WeirC Skew NumUp NumDn MinLoCord MaxHiCord MaxSubmerge Is_Ogee
20.5,33,3,0, 60, 60, , , , 0, 1,1,,
    4574  4592.7  4600.9    4607  4632.5  4656.8  4689.2  4714.2    4719  4733.4
    4950    4950    5050    5050  5070.7  5072.6  5109.8  5112.9  5125.1  5141.1
  5143.2  5160.2  5164.5  5170.8  5174.8    5183    5194  5203.3  5211.2  5231.4
    5241  5254.3  5279.3  5306.2  5325.8  5333.5  5339.2  5351.5  5364.2  5367.3
  5376.2  5382.4  5396.8  5406.8  5416.4  5423.8  5442.2  5450.7  5463.4    5480
  5493.2  5496.6    5503  5511.6  5524.9  5537.5  5561.2  5572.7  5597.2    5608
 1061.42 1060.31 1059.71 1059.42 1057.82 1056.49 1055.14 1054.52  1054.3    1054
    1054    1054    1054    1054    1054 1054.09 1054.77 1054.75 1054.95 1055.61
 1055.76 1056.39 1056.64 1056.82 1057.27 1057.82 1058.69  1059.1 1059.67 1060.65
 1061.56 1062.45 1063.91 1065.17 1066.61 1066.95 1067.44 1068.08 1068.34 1068.64
 1069.29 1069.26 1070.16 1070.49 1071.32  1071.5 1072.39 1072.52 1073.44 1073.98
 1074.54 1074.92 1075.29 1075.53 1076.12  1076.5 1077.38 1077.53 1078.77 1079.16
    1021    1021    1021    1021    1021    1021    1021    1021    1021    1021
    1021    1052    1052    1021    1021    1021    1021    1021    1021    1021
    1021    1021    1021    1021    1021    1021    1021    1021    1021    1021
    1021    1021    1021    1021    1021    1021    1021    1021    1021    1021
    1021    1021    1021    1021    1021    1021    1021    1021    1021    1021
    1021    1021    1021    1021    1021    1021    1021    1021    1021    1021
    4574  4592.7  4600.9    4607  4632.5  4656.8  4689.2  4714.2    4719  4733.4
    4950    4950    5050    5050  5070.7  5072.6  5109.8  5112.9  5125.1  5141.1
  5143.2  5160.2  5164.5  5170.8  5174.8    5183    5194  5203.3  5211.2  5231.4
    5241  5254.3  5279.3  5306.2  5325.8  5333.5  5339.2  5351.5  5364.2  5367.3
  5376.2  5382.4  5396.8  5406.8  5416.4  5423.8  5442.2  5450.7  5463.4    5480
  5493.2  5496.6    5503  5511.6  5524.9  5537.5  5561.2  5572.7  5597.2    5608
 1061.42 1060.31 1059.71 1059.42 1057.82 1056.49 1055.14 1054.52  1054.3    1054
    1054    1054    1054    1054    1054 1054.09 1054.77 1054.75 1054.95 1055.61
 1055.76 1056.39 1056.64 1056.82 1057.27 1057.82 1058.69  1059.1 1059.67 1060.65
 1061.56 1062.45 1063.91 1065.17 1066.61 1066.95 1067.44 1068.08 1068.34 1068.64
 1069.29 1069.26 1070.16 1070.49 1071.32  1071.5 1072.39 1072.52 1073.44 1073.98
 1074.54 1074.92 1075.29 1075.53 1076.12  1076.5 1077.38 1077.53 1078.77 1079.16
    1021    1021    1021    1021    1021    1021    1021    1021    1021    1021
    1021    1052    1052    1021    1021    1021    1021    1021    1021    1021
    1021    1021    1021    1021    1021    1021    1021    1021    1021    1021
    1021    1021    1021    1021    1021    1021    1021    1021    1021    1021
    1021    1021    1021    1021    1021    1021    1021    1021    1021    1021
    1021    1021    1021    1021    1021    1021    1021    1021    1021    1021
Pier Skew, UpSta & Num, DnSta & Num=  ,4966.7, 2 ,4966.7, 2 , 0 , 0 , 0 ,0,0
       1       1
 1046.97    1052
       1       1
 1042.18    1052
Pier Skew, UpSta & Num, DnSta & Num=  ,5000, 2 ,5000, 2 , 0 , 0 , 0 ,0,0
       1       1
    1041    1052
       1       1
 1040.75    1052
Pier Skew, UpSta & Num, DnSta & Num=  ,5033.3, 2 ,5033.3, 2 , 0 , 0 , 0 ,0,0
       1       1
 1049.02    1052
       1       1
 1049.04    1052
Abutment Skew #Up #Dn= , 2 , 2
    4950    4960
    1052 1046.02
    4950    4960
    1052 1042.54
Abutment Skew #Up #Dn= , 2 , 2
    5040    5050
 1048.17    1052
    5040    5050
 1049.46    1052
BR Coef= 1 , 1 , 0 ,1.25, 0 ,,,0.8,0,2,0,
WSPro=,,,, 1 ,,,, 0 ,,,, 0 ,,,,-1 ,-1 ,-1 , 0 , 0 , 0 , 0 , 0
BC Design=,, 0 ,, 0 ,,,,,,
BC HTab HWMax=1076.64

Type RM Length L Ch R = 1 ,38838   ,70,70,70
BEGIN DESCRIPTION:
Hinton Creek Rd SR 1753 - DS
END DESCRIPTION:
XS GIS Cut Line= 5
      1192000.63       618589.11      1192100.16       618337.51
      1192146.24       618215.86      1192181.26       618125.55
      1192354.89       617860.36
#Sta/Elev= 30
  4717.9 1052.72  4741.6  1049.3  4760.5 1048.19  4778.4  1049.1  4877.2 1048.99
  4916.5 1051.49  4939.2 1048.92  4950.5 1044.69  4964.3 1041.68  4988.5  1046.1
    4991 1040.75    5009 1040.75    5010 1042.75  5011.4 1048.61    5060 1050.94
  5127.4 1049.05  5137.5 1050.74  5164.9 1050.48    5176 1052.11  5193.4 1051.92
  5214.6 1053.53  5260.4 1064.85  5265.8 1065.45  5282.7  1063.8  5292.2 1068.13
  5299.2 1073.46  5306.6 1077.22  5385.9  1088.3  5446.3 1093.78  5532.4 1094.95
#Mann= 3 ,-1 , 0
  4717.9     .08       0  4988.5     .05       0  5011.4     .08       0
#XS Ineff= 2 , 0
       0 4902.35  1052.5 5128.24       0  1052.5
Permanent Ineff=
       F       F
Bank Sta=4988.5,5011.4
Exp/Cntr=0.5,0.3

Type RM Length L Ch R = 1 ,38768   ,477,477,477
BEGIN DESCRIPTION:
XS 101
END DESCRIPTION:
XS GIS Cut Line= 2
      1191978.19       618749.52       1192351.6       617967.16
#Sta/Elev= 30
  4579.8 1059.22  4597.2  1056.6    4609 1056.03    4621 1053.82  4632.7 1054.58
  4667.4 1053.96  4690.4 1057.71  4703.3 1054.26    4714 1052.57  4748.6 1048.76
  4790.3 1047.93  4916.1 1048.51  4941.7 1047.57  4960.7 1042.86  4979.3 1041.43
  4984.6 1042.21 4990.59 1045.79  4990.6 1041.43  5009.8 1041.43  5013.5 1048.41
  5055.4 1047.68  5106.6 1048.45  5182.7 1053.82  5205.1 1057.33  5267.5 1063.92
  5296.4  1074.2  5305.3 1076.52  5359.8 1087.19  5410.1 1094.66  5446.7 1098.54
#Mann= 3 ,-1 , 0
  4579.8     .08       0 4990.59     .05       0  5013.5     .08       0
Bank Sta=4990.59,5013.5
Exp/Cntr=0.3,0.1

Type RM Length L Ch R = 1 ,38291   ,430,430,430
BEGIN DESCRIPTION:
Hinton Crk - 74.0
END DESCRIPTION:
XS GIS Cut Line= 6
      1192420.61       618863.45      1192479.42        618701.7
      1192538.24       618642.89      1192578.15       618592.47
       1192731.5       618403.41      1192790.32       618313.09
#Sta/Elev= 30
  4714.1 1060.26  4737.5 1057.59  4753.8 1055.19  4760.5 1053.86    4768 1053.06
  4785.6 1051.51  4806.1 1050.67  4864.7 1046.12  4933.5 1045.09  4968.5 1045.75
  4978.2 1046.63  4990.2  1039.9  5009.8  1039.9  5017.7 1043.63  5023.1  1044.4
  5031.4 1046.22  5038.5 1047.08  5048.3    1047  5092.1 1045.09  5110.3 1044.76
  5210.4 1045.14  5250.6 1045.92    5286 1047.35  5306.5 1049.89  5320.4 1052.13
  5335.1 1056.98  5346.5 1058.58  5356.5 1061.01  5372.1 1064.09  5384.9 1067.35
#Mann= 3 ,-1 , 0
  4714.1     .08       0  4978.2     .05       0  5017.7     .08       0
Bank Sta=4978.2,5017.7
Exp/Cntr=0.3,0.1

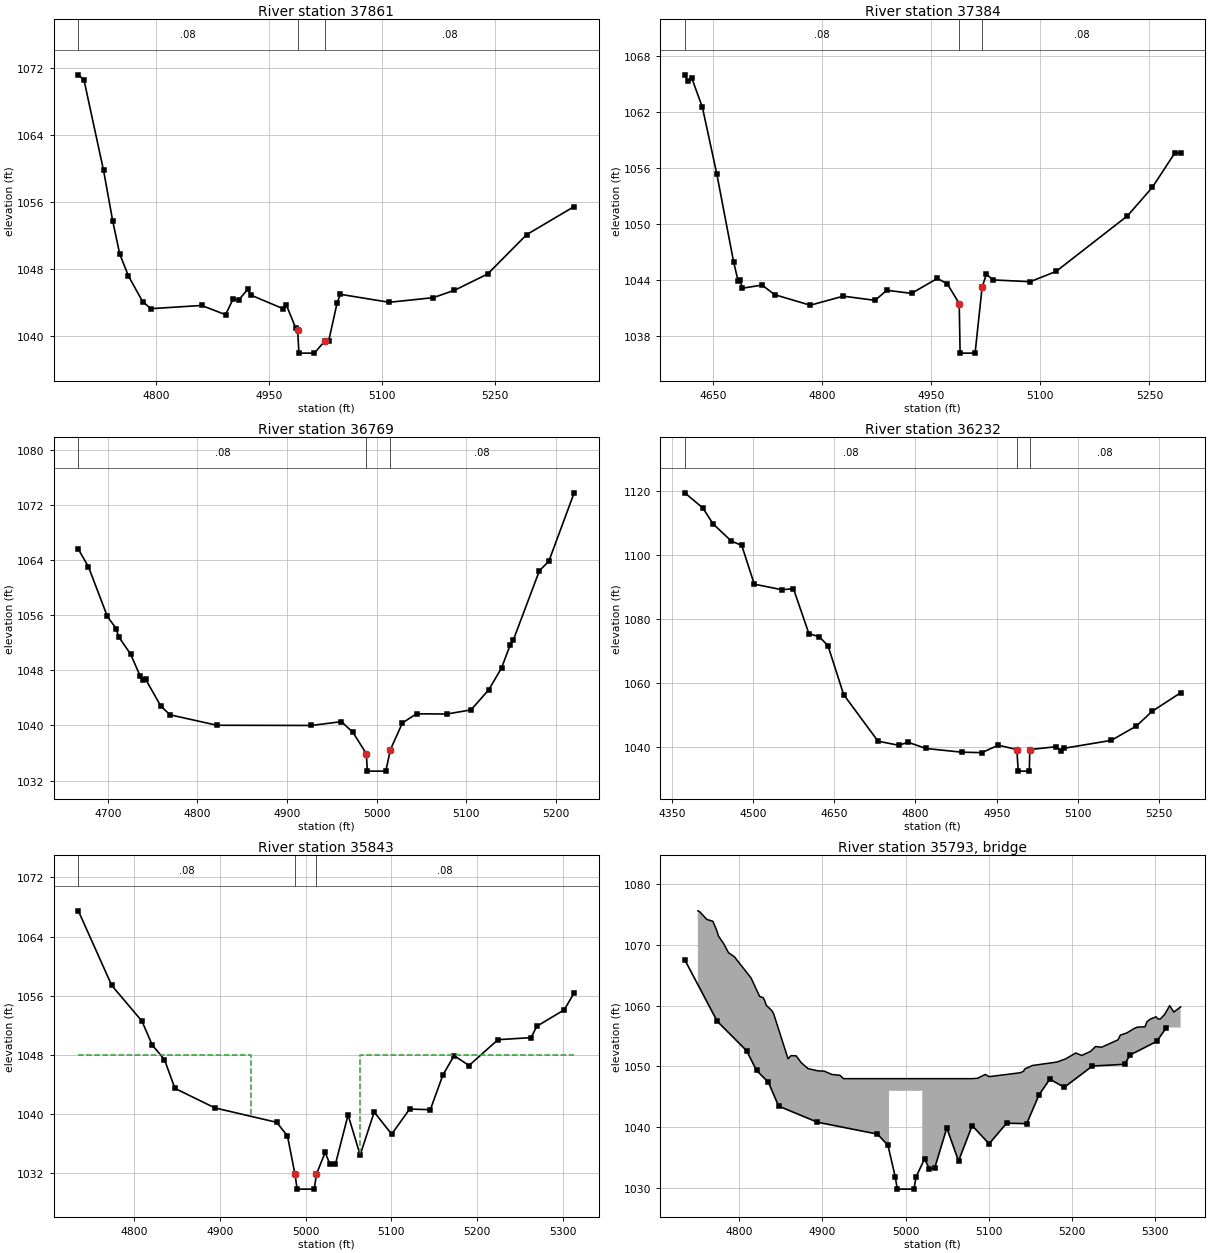
Type RM Length L Ch R = 1 ,37861   ,477,477,477
BEGIN DESCRIPTION:
Hinton Crk - 73.0
END DESCRIPTION:
XS GIS Cut Line= 5
      1192567.65       618936.97      1192815.52       618880.26
      1192914.25       618871.85       1193059.2       618865.55
      1193214.64       618827.74
#Sta/Elev= 30
  4696.8 1071.18  4704.3 1070.57  4730.3 1059.78  4742.4 1053.79  4751.7 1049.84
  4763.3 1047.21  4782.2 1044.15  4793.1 1043.31  4860.6 1043.69  4892.3 1042.59
  4902.2 1044.44  4909.9 1044.36  4921.6  1045.6  4925.5 1044.94  4968.9  1043.3
  4973.1 1043.72  4985.3 1041.05    4988 1040.81  4989.7 1038.01  5010.3 1038.01
  5024.1 1039.46  5029.3 1039.48  5040.3 1043.94  5044.6 1045.02  5109.6 1044.07
    5168 1044.62  5196.3  1045.5  5240.3 1047.44  5292.1 1052.13  5355.2 1055.48
#Mann= 3 ,-1 , 0
  4696.8     .08       0    4988     .05       0  5024.1     .08       0
Bank Sta=4988,5024.1
Exp/Cntr=0.3,0.1

Type RM Length L Ch R = 1 ,37384   ,615,615,615
BEGIN DESCRIPTION:
Hinton Crk - 72.0
END DESCRIPTION:
XS GIS Cut Line= 5
      1192670.58       619392.81      1193006.68       619260.47
       1193065.5       619210.06      1193136.92       619178.55
      1193292.37       619123.93
#Sta/Elev= 30
  4611.3 1065.99  4615.2 1065.36    4621 1065.62  4635.5  1062.5  4655.2 1055.39
  4678.3 1045.96  4684.6 1043.86  4687.4 1044.01  4690.3  1043.1  4717.5 1043.44
  4734.8 1042.41  4783.7 1041.28  4829.2 1042.25  4872.8  1041.8  4888.9 1042.88
  4922.9 1042.55  4958.6 1044.16  4972.2 1043.56  4988.5 1041.46  4989.7 1036.14
  5010.3 1036.14    5020 1043.24  5025.8 1044.59  5035.4 1043.99  5086.1  1043.8
  5121.7 1044.91  5219.7 1050.86  5253.8 1053.91  5284.6 1057.58  5292.8 1057.59
#Mann= 3 ,-1 , 0
  4611.3     .08       0  4988.5     .05       0    5020     .08       0
Bank Sta=4988.5,5020
Exp/Cntr=0.3,0.1

Type RM Length L Ch R = 1 ,36769   ,537,537,537
BEGIN DESCRIPTION:
Hinton Crk - 71.0
END DESCRIPTION:
XS GIS Cut Line= 4
      1192760.91       619857.05        1193055.       619852.85
      1193197.84       619819.24      1193302.87       619779.33
#Sta/Elev= 30
  4667.2 1065.56  4678.5    1063  4699.6 1055.81  4709.5 1054.03  4712.1 1052.88
  4725.5 1050.35  4736.2 1047.16    4739 1046.59  4742.2 1046.73  4759.3 1042.79
  4769.6 1041.54  4821.9 1040.03  4927.1    1040  4960.8 1040.55  4973.7 1038.99
  4988.6  1035.9  4989.7 1033.38  5010.3 1033.38  5015.5 1036.51  5028.9 1040.38
  5044.6 1041.69  5078.5 1041.66  5105.4 1042.26  5125.2 1045.17  5139.5 1048.35
  5149.1 1051.67  5152.7 1052.42  5181.7 1062.43  5192.3 1063.83  5220.5 1073.73
#Mann= 3 ,-1 , 0
  4667.2     .08       0  4988.6     .05       0  5015.5     .08       0
Bank Sta=4988.6,5015.5
Exp/Cntr=0.3,0.1

Type RM Length L Ch R = 1 ,36232   ,389,389,389
BEGIN DESCRIPTION:
Hinton Crk - 70.0
END DESCRIPTION:
XS GIS Cut Line= 6
      1192666.38        620547.8      1192956.27       620342.74
      1193026.25       620325.94      1193185.24       620329.69
      1193378.49       620312.89      1193504.53       620264.57
#Sta/Elev= 30
  4374.2 1119.46  4407.7 1114.69  4426.4 1109.74  4460.2 1104.36  4479.3 1103.04
  4502.5  1090.9  4553.3 1089.17  4574.8 1089.46  4603.3 1075.45  4622.6 1074.43
  4638.5 1071.68  4667.5 1056.36  4730.9 1041.81  4769.3 1040.51  4786.1 1041.49
  4819.5 1039.52  4885.2 1038.37  4922.5 1038.22    4953 1040.55 4987.34 1039.19
  4989.7 1032.44  5010.3 1032.44 5011.08 1039.19  5058.7 1040.06    5069 1038.79
  5074.1 1039.58  5161.6 1042.06  5207.7 1046.51  5236.7  1051.1  5289.6 1056.94
#Mann= 3 ,-1 , 0
  4374.2     .08       0 4987.34     .05       0 5011.08     .08       0
Bank Sta=4987.34,5011.08
Exp/Cntr=0.5,0.3

Type RM Length L Ch R = 1 ,35843   ,83,83,83
BEGIN DESCRIPTION:
John Stroud Rd SR 1755 - US
END DESCRIPTION:
XS GIS Cut Line= 6
      1193112.79       620574.78      1193221.24       620593.36
       1193375.4       620672.64      1193407.94       620654.49
      1193431.09       620655.12      1193585.04       620478.02
#Sta/Elev= 30
  4734.4 1067.49  4773.4 1057.41  4808.7 1052.58  4820.7 1049.35    4835 1047.39
  4847.2 1043.49  4893.9 1040.85  4966.1  1038.9  4978.7 1037.06  4987.5 1031.87
    4990 1029.87    5010 1029.87  5012.5 1031.87  5022.7 1034.83  5028.5  1033.2
  5034.8 1033.27  5049.5  1039.9  5063.6 1034.48    5080 1040.29  5100.4  1037.3
  5121.4 1040.69  5145.6 1040.61  5160.4 1045.34  5173.4 1047.91  5190.8 1046.58
  5224.6 1050.07  5263.3 1050.35  5269.9 1051.88    5302 1054.11  5313.6 1056.39
#Mann= 3 ,-1 , 0
  4734.4     .08       0  4987.5     .05       0  5012.5     .08       0
#XS Ineff= 2 , 0
       0    4936    1048    5064       0    1048
Permanent Ineff=
       F       F
Bank Sta=4987.5,5012.5
Exp/Cntr=0.5,0.3

Type RM Length L Ch R = 3 ,35793   ,,,
BEGIN DESCRIPTION:
John Stroud Rd SR 1755
Structure ID: John Stroud Rd SR 1755
Approximate Survey Structure
END DESCRIPTION:
Bridge Culvert--1,0,-1,-1, 0
Deck Dist Width WeirC Skew NumUp NumDn MinLoCord MaxHiCord MaxSubmerge Is_Ogee
44,12,3,0, 60, 60, , , , 0, 1,1,,
  4750.1  4752.1  4760.9  4768.2  4772.6    4775  4781.2    4787    4794  4814.1
  4824.4  4828.5  4830.4  4832.4  4839.4  4841.4  4858.6  4862.2  4868.4  4874.2
  4882.6  4894.5  4901.9  4911.5    4921  4925.2    4980    4980    5020    5020
  5080.1  5086.5  5095.7  5100.3    5138  5141.9  5143.2  5152.4  5181.8  5192.5
  5204.6  5211.7  5222.5  5228.3  5235.7  5255.4  5258.2  5266.1  5274.9  5278.9
  5287.9  5290.2  5294.4  5301.2  5303.6  5306.4  5311.7  5317.5  5322.4  5330.7
 1075.54 1075.42 1074.13 1073.82 1072.39 1071.38 1070.13 1068.66 1068.01 1064.52
  1061.5  1061.3 1060.84 1060.04 1059.11 1058.58 1051.26 1051.78 1051.74 1050.65
 1049.65 1049.28 1049.24 1048.68 1048.55    1048    1048    1048    1048    1048
    1048 1048.06 1048.69 1048.33 1048.97 1049.23 1049.59 1050.16 1050.72 1051.25
 1052.21 1051.81 1052.48 1053.27 1053.16 1054.37 1055.14 1055.51 1056.24 1056.46
 1056.51 1057.35 1057.78 1058.15 1057.78  1057.8 1058.58 1059.99 1058.93 1059.77
 1009.87 1009.87 1009.87 1009.87 1009.87 1009.87 1009.87 1009.87 1009.87 1009.87
 1009.87 1009.87 1009.87 1009.87 1009.87 1009.87 1009.87 1009.87 1009.87 1009.87
 1009.87 1009.87 1009.87 1009.87 1009.87 1009.87 1009.87    1046    1046 1009.87
 1009.87 1009.87 1009.87 1009.87 1009.87 1009.87 1009.87 1009.87 1009.87 1009.87
 1009.87 1009.87 1009.87 1009.87 1009.87 1009.87 1009.87 1009.87 1009.87 1009.87
 1009.87 1009.87 1009.87 1009.87 1009.87 1009.87 1009.87 1009.87 1009.87 1009.87
  4750.1  4752.1  4760.9  4768.2  4772.6    4775  4781.2    4787    4794  4814.1
  4824.4  4828.5  4830.4  4832.4  4839.4  4841.4  4858.6  4862.2  4868.4  4874.2
  4882.6  4894.5  4901.9  4911.5    4921  4925.2    4980    4980    5020    5020
  5080.1  5086.5  5095.7  5100.3    5138  5141.9  5143.2  5152.4  5181.8  5192.5
  5204.6  5211.7  5222.5  5228.3  5235.7  5255.4  5258.2  5266.1  5274.9  5278.9
  5287.9  5290.2  5294.4  5301.2  5303.6  5306.4  5311.7  5317.5  5322.4  5330.7
 1075.54 1075.42 1074.13 1073.82 1072.39 1071.38 1070.13 1068.66 1068.01 1064.52
  1061.5  1061.3 1060.84 1060.04 1059.11 1058.58 1051.26 1051.78 1051.74 1050.65
 1049.65 1049.28 1049.24 1048.68 1048.55    1048    1048    1048    1048    1048
    1048 1048.06 1048.69 1048.33 1048.97 1049.23 1049.59 1050.16 1050.72 1051.25
 1052.21 1051.81 1052.48 1053.27 1053.16 1054.37 1055.14 1055.51 1056.24 1056.46
 1056.51 1057.35 1057.78 1058.15 1057.78  1057.8 1058.58 1059.99 1058.93 1059.77
 1009.87 1009.87 1009.87 1009.87 1009.87 1009.87 1009.87 1009.87 1009.87 1009.87
 1009.87 1009.87 1009.87 1009.87 1009.87 1009.87 1009.87 1009.87 1009.87 1009.87
 1009.87 1009.87 1009.87 1009.87 1009.87 1009.87 1009.87    1046    1046 1009.87
 1009.87 1009.87 1009.87 1009.87 1009.87 1009.87 1009.87 1009.87 1009.87 1009.87
 1009.87 1009.87 1009.87 1009.87 1009.87 1009.87 1009.87 1009.87 1009.87 1009.87
 1009.87 1009.87 1009.87 1009.87 1009.87 1009.87 1009.87 1009.87 1009.87 1009.87
Abutment Skew #Up #Dn= , 2 , 2
    4980  4982.5
    1046 1035.31
    4980  4982.5
    1046 1038.93
Abutment Skew #Up #Dn= , 2 , 2
  5017.5    5020
 1033.87    1046
  5017.5    5020
 1038.34    1046
BR Coef= 1 , 1 , 0 ,1.25, 0 ,,,0.8,0,2,0,
WSPro=,,,, 1 ,,,, 0 ,,,, 0 ,,,,-1 ,-1 ,-1 , 0 , 0 , 0 , 0 , 0
BC Design=,, 0 ,, 0 ,,,,,,
BC HTab HWMax=1067.49

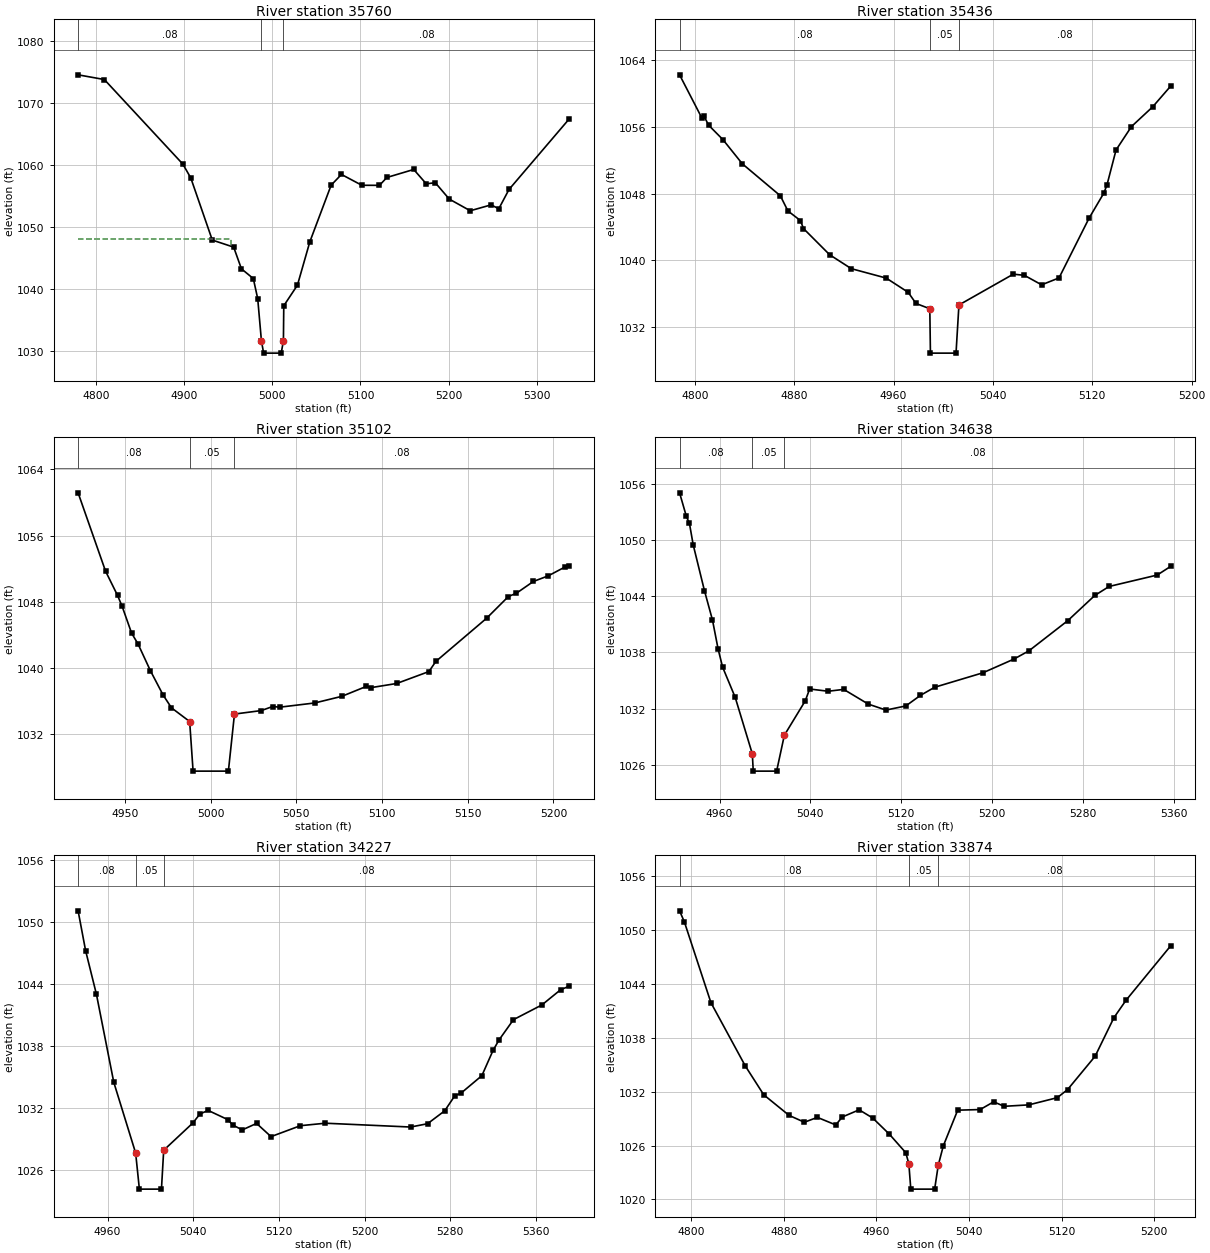
Type RM Length L Ch R = 1 ,35760   ,324,324,324
BEGIN DESCRIPTION:
John Stroud Rd SR 1755 - DS
END DESCRIPTION:
XS GIS Cut Line= 6
      1193113.97       620666.86      1193224.41       620686.44
      1193326.62       620740.77       1193405.8       620742.39
       1193476.9       620721.38      1193614.06       620609.89
#Sta/Elev= 30
  4779.3 1074.52  4809.1 1073.76  4898.3 1060.11  4907.3 1057.88  4931.7 1047.86
    4956 1046.72  4964.8 1043.22  4978.3 1041.65  4983.3 1038.41  4987.5 1031.62
    4990 1029.62    5010 1029.62  5012.5 1031.62  5012.9 1037.26  5028.4 1040.58
  5042.5 1047.58  5066.7 1056.72  5078.4 1058.45  5101.6  1056.7  5121.6 1056.69
    5130 1057.96  5160.5 1059.25  5174.7 1056.94    5185 1057.11  5200.9 1054.47
  5224.7 1052.59  5248.4 1053.54  5257.1 1052.91  5268.7 1056.02  5337.3 1067.44
#Mann= 3 ,-1 , 0
  4779.3     .08       0  4987.5     .05       0  5012.5     .08       0
#XS Ineff= 2 , 0
       0    4953    1048    5047       0    1048
Permanent Ineff=
       F       F
Bank Sta=4987.5,5012.5
Exp/Cntr=0.5,0.3

Type RM Length L Ch R = 1 ,35436   ,334,334,334
BEGIN DESCRIPTION:
Hinton Crk - 69.0
END DESCRIPTION:
XS GIS Cut Line= 4
      1193010.88       621102.73      1193191.54       621039.71
      1193281.86       621039.71       1193395.3        621031.3
#Sta/Elev= 30
  4787.8 1062.27  4805.9 1057.04  4807.6 1057.27  4811.2 1056.22  4822.7 1054.49
  4838.3 1051.59  4868.9 1047.75    4875 1045.93  4885.1 1044.77  4887.5 1043.82
  4908.6 1040.67    4926    1039  4954.1 1037.87  4971.8 1036.16  4978.1 1034.82
  4989.2 1034.19  4989.7 1028.86  5010.3 1028.86 5012.64 1034.64  5056.4 1038.34
  5065.3  1038.2  5079.2 1037.06  5093.2 1037.89  5117.4 1045.07  5129.3 1048.08
  5131.8 1049.06  5139.1 1053.25  5151.5 1056.06  5168.6 1058.43  5183.2 1060.94
#Mann= 3 ,-1 , 0
  4787.8     .08       0  4989.2     .05       0 5012.64     .08       0
Bank Sta=4989.2,5012.64
Exp/Cntr=0.3,0.1

Type RM Length L Ch R = 1 ,35102   ,464,464,464
BEGIN DESCRIPTION:
Hinton Crk - 68.0
END DESCRIPTION:
XS GIS Cut Line= 5
      1193145.32       621380.01      1193206.24       621367.41
      1193248.25        621350.6      1193304.97        621331.7
       1193403.7       621264.48
#Sta/Elev= 30
  4922.6 1061.16  4938.6 1051.71  4945.6 1048.78  4948.3 1047.45  4953.8 1044.23
  4957.6  1042.9  4964.8 1039.68  4972.2 1036.75  4977.1  1035.2  4987.7 1033.55
  4989.7 1027.56  5010.3 1027.56 5013.85 1034.45  5029.5 1034.87  5036.1 1035.36
  5040.3 1035.28  5060.7 1035.79  5076.5 1036.59  5090.8 1037.79  5093.8 1037.65
  5108.5 1038.14  5127.3 1039.58  5131.4 1040.81    5161 1046.02  5173.7 1048.64
  5178.4 1049.04  5188.3 1050.46    5197 1051.14  5206.5 1052.18  5209.3 1052.29
#Mann= 3 ,-1 , 0
  4922.6     .08       0  4987.7     .05       0 5013.85     .08       0
Bank Sta=4987.7,5013.85
Exp/Cntr=0.3,0.1

Type RM Length L Ch R = 1 ,34638   ,411,411,411
BEGIN DESCRIPTION:
Hinton Crk - 67.0
END DESCRIPTION:
XS GIS Cut Line= 6
      1193496.13       621739.22      1193529.74        621684.6
      1193557.05       621545.96      1193536.04       621436.73
      1193544.44       621367.41      1193531.84       621323.29
#Sta/Elev= 30
  4924.8 1055.04  4930.8 1052.52  4933.5 1051.77  4936.8 1049.49  4946.7  1044.6
  4953.8 1041.45  4958.7 1038.39  4962.7 1036.43  4973.8  1033.2  4988.9 1027.16
  4989.7 1025.32  5010.3 1025.32  5017.1 1029.15  5035.5 1032.82  5039.4 1034.09
  5055.7 1033.85  5069.4 1034.05    5091 1032.48  5106.6 1031.84  5124.1 1032.28
    5137 1033.41  5149.6 1034.28    5192 1035.82  5219.1 1037.27  5232.5 1038.16
  5266.9  1041.4  5290.6 1044.08  5303.2 1045.04  5345.6 1046.26  5357.6  1047.2
#Mann= 3 ,-1 , 0
  4924.8     .08       0  4988.9     .05       0  5017.1     .08       0
Bank Sta=4988.9,5017.1
Exp/Cntr=0.3,0.1

Type RM Length L Ch R = 1 ,34227   ,353,353,353
BEGIN DESCRIPTION:
Hinton Crk - 66.0
END DESCRIPTION:
XS GIS Cut Line= 4
      1193949.87       621816.94      1193903.65       621716.11
      1193821.73       621508.15      1193771.31       621394.71
#Sta/Elev= 30
  4932.5 1051.12  4939.5 1047.26  4949.6 1043.03  4965.8  1034.5 4986.21 1027.64
  4989.7 1024.14  5010.3 1024.14  5012.4 1027.91  5039.5 1030.54  5046.3 1031.43
  5053.9 1031.77    5072 1030.89  5077.2 1030.34  5085.7 1029.88  5099.1 1030.51
  5112.6 1029.23    5140 1030.29  5163.3 1030.53  5242.9 1030.16  5258.7 1030.48
  5274.7 1031.73  5284.2  1033.2  5289.9 1033.44  5309.4 1035.14  5319.8 1037.58
  5325.4  1038.6  5338.9 1040.57  5365.5    1042  5382.9 1043.47  5391.1 1043.82
#Mann= 3 ,-1 , 0
  4932.5     .08       0 4986.21     .05       0  5012.4     .08       0
Bank Sta=4986.21,5012.4
Exp/Cntr=0.3,0.1

Type RM Length L Ch R = 1 ,33874   ,517,517,517
BEGIN DESCRIPTION:
Hinton Crk - 65.0
END DESCRIPTION:
XS GIS Cut Line= 5
      1194201.94       621554.36       1194073.8       621455.63
      1193970.87       621411.52      1193922.56       621384.21
      1193857.44       621314.89
#Sta/Elev= 30
    4790  1052.1  4794.2 1050.85  4817.1 1041.88  4846.8 1034.84  4862.7 1031.64
  4884.6 1029.35  4897.8 1028.59    4909 1029.13  4924.9 1028.29  4930.5 1029.17
  4945.1 1029.97  4956.8 1029.06  4971.2 1027.26  4985.3 1025.21    4988 1023.99
  4989.7 1021.15  5010.3 1021.15  5013.4  1023.8  5017.8 1025.97  5030.2 1029.93
  5049.6    1030  5061.3 1030.86  5070.3 1030.36  5091.6 1030.52  5116.2 1031.32
  5125.1 1032.22  5148.9 1035.93  5165.1 1040.21  5175.5 1042.14  5214.3 1048.23
#Mann= 3 ,-1 , 0
    4790     .08       0    4988     .05       0  5013.4     .08       0
Bank Sta=4988,5013.4
Exp/Cntr=0.3,0.1