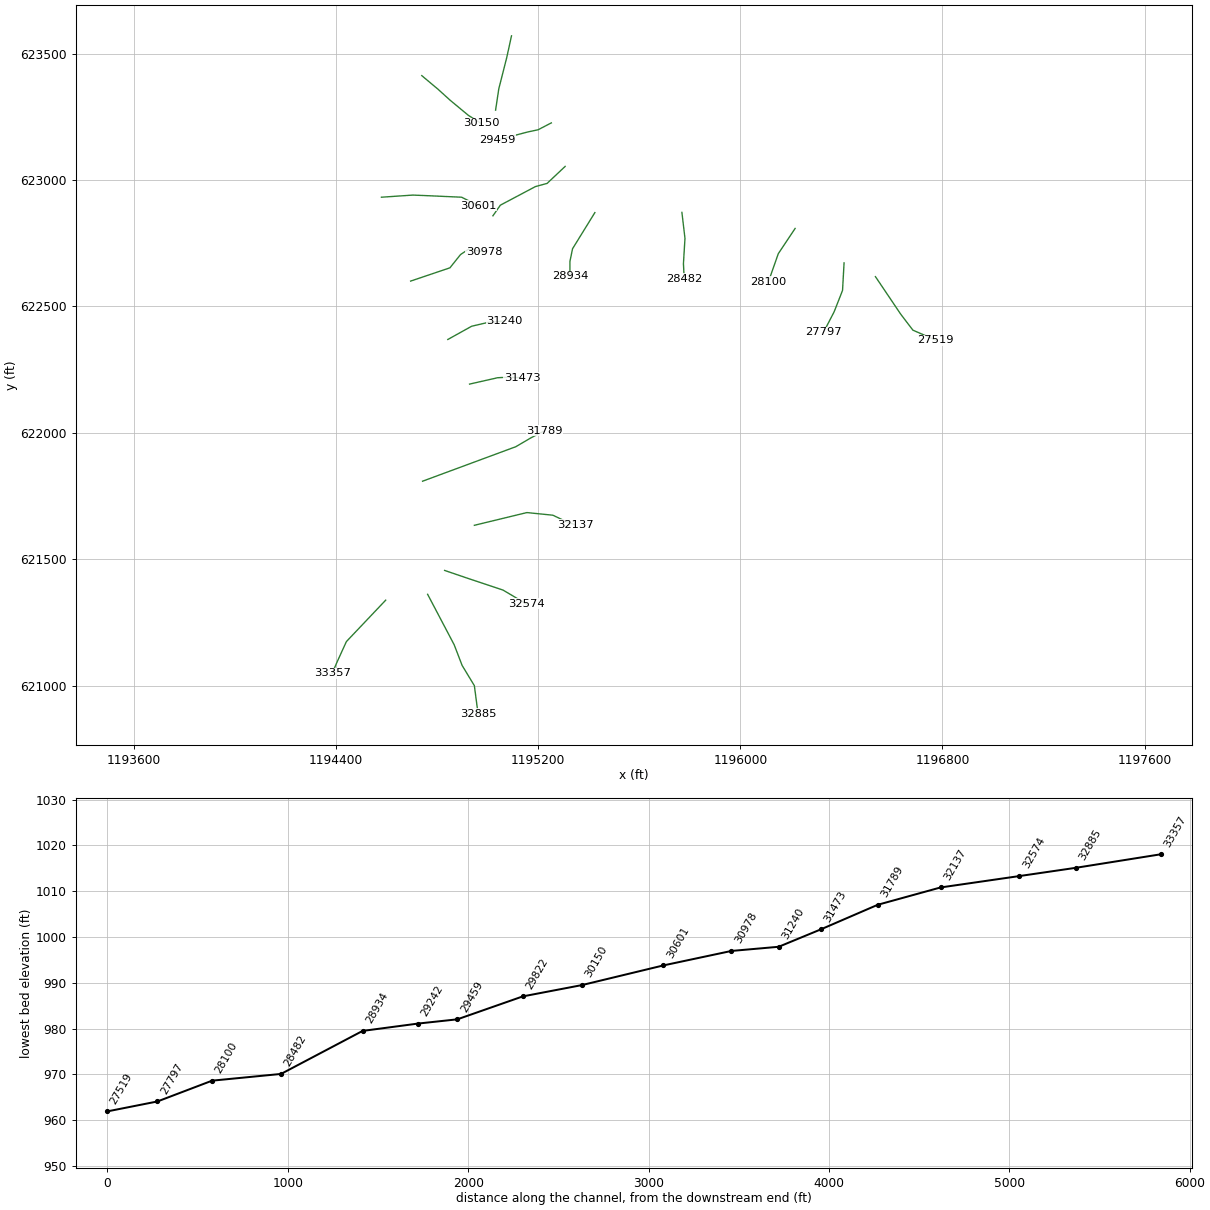
HEC-RAS study lds_hinton_crk.prj: Hinton Creek Limited Detail Study

--- lds_hinton_crk.g01 (geometry) --- (continued)

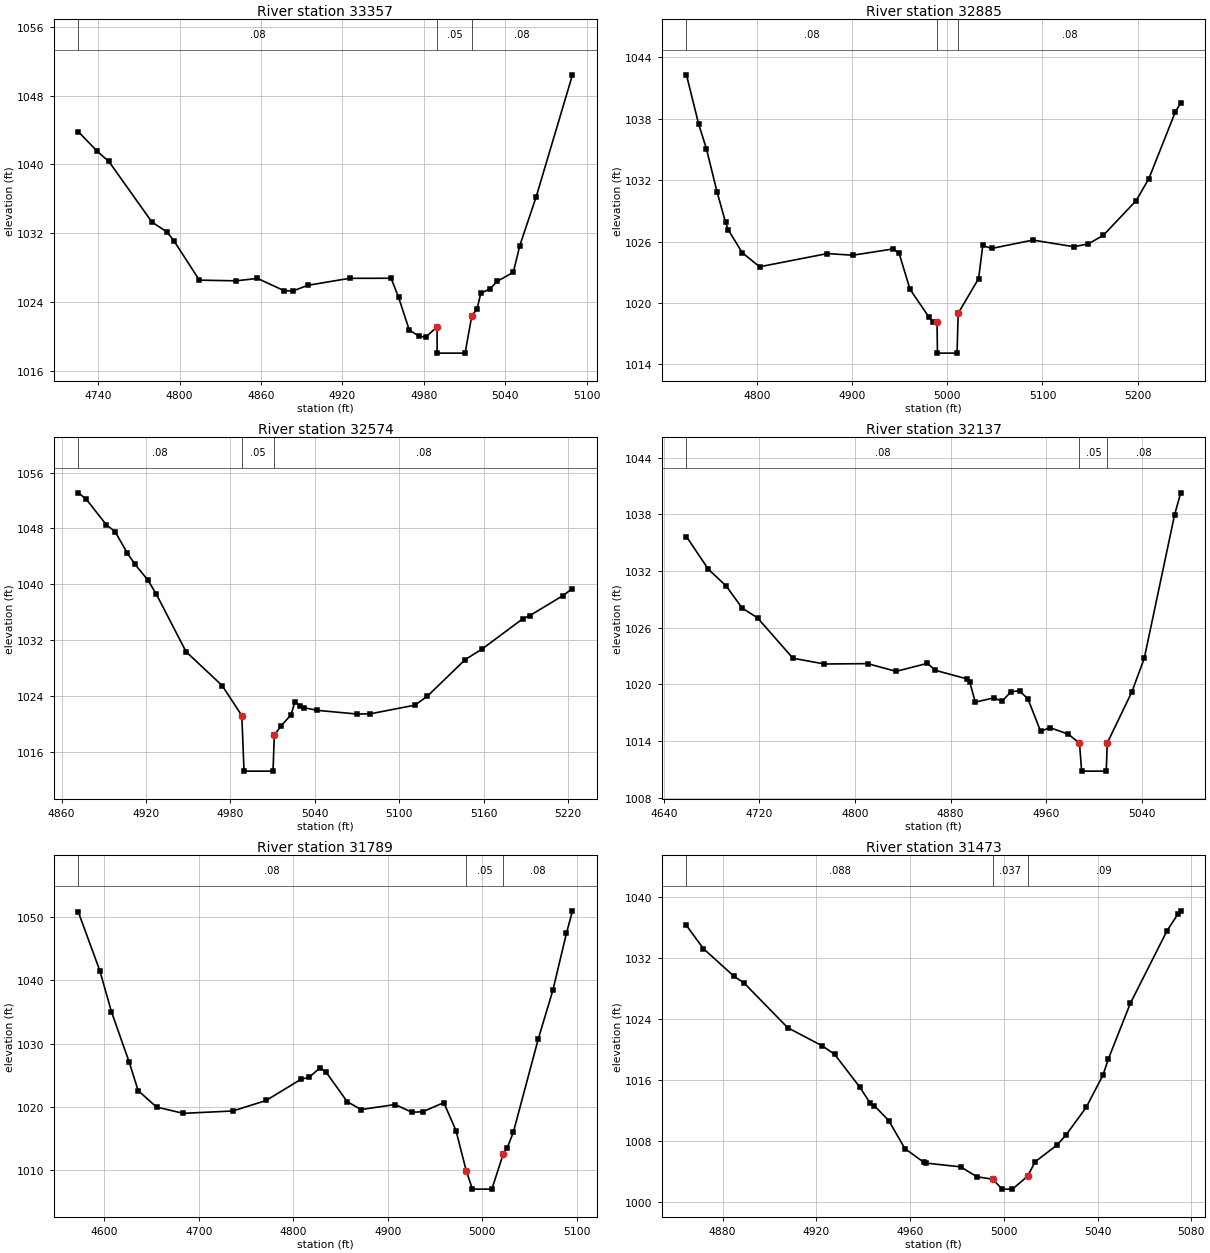
Type RM Length L Ch R = 1 ,33357   ,472,472,472
BEGIN DESCRIPTION:
Hinton Crk - 64.0
END DESCRIPTION:
XS GIS Cut Line= 4
      1194596.86         621338.      1194441.41       621174.15
       1194407.8       621100.63       1194384.7       621048.11
#Sta/Elev= 30
  4725.4 1043.82  4739.4 1041.52  4747.9 1040.35  4779.7 1033.29  4790.7 1032.15
  4796.1 1031.06  4814.6 1026.54  4841.7 1026.46  4857.4 1026.74  4876.9 1025.32
  4883.5 1025.28  4894.5 1025.94  4925.2 1026.75  4955.8 1026.76  4961.3 1024.55
  4969.2 1020.73  4976.3 1020.03  4981.2  1019.9 4989.68 1021.11  4989.7 1018.05
  5010.3 1018.05  5015.2 1022.37 5019.08 1023.18 5021.84    1025  5028.7 1025.54
    5034 1026.41  5045.8 1027.45  5050.6 1030.56  5062.7 1036.26  5089.4 1050.42
#Mann= 3 ,-1 , 0
  4725.4     .08       0 4989.68     .05       0  5015.2     .08       0
Bank Sta=4989.68,5015.2
Exp/Cntr=0.3,0.1

Type RM Length L Ch R = 1 ,32885   ,311,311,311
BEGIN DESCRIPTION:
Hinton Crk - 63.0
END DESCRIPTION:
XS GIS Cut Line= 5
      1194762.81        621361.1      1194867.84       621161.54
      1194899.35       621079.62      1194947.67        620999.8
      1194962.37       620888.46
#Sta/Elev= 30
  4726.2 1042.29  4738.9 1037.51  4747.1 1035.08  4758.4 1030.82  4767.2 1027.88
  4770.1 1027.14  4784.6 1024.92    4803 1023.53  4874.1 1024.82  4900.8 1024.66
    4943 1025.27  4949.3 1024.89  4960.9 1021.33  4980.6 1018.64  4984.8 1018.17
 4989.29 1018.11  4989.7 1015.09  5010.3 1015.09 5011.47 1018.98  5032.9 1022.37
  5037.3 1025.61  5046.6 1025.32  5089.9 1026.14  5132.8 1025.49  5147.9 1025.76
  5163.7 1026.59  5198.3 1029.99  5211.6 1032.13  5239.6  1038.7  5245.1 1039.54
#Mann= 3 ,-1 , 0
  4726.2     .08       0 4989.29     .05       0 5011.47     .08       0
Bank Sta=4989.29,5011.47
Exp/Cntr=0.3,0.1

Type RM Length L Ch R = 1 ,32574   ,437,437,437
BEGIN DESCRIPTION:
Hinton Crk - 62.0
END DESCRIPTION:
XS GIS Cut Line= 4
      1194830.03       621455.63      1194928.76       621422.02
       1195061.1       621377.91      1195153.53       621323.29
#Sta/Elev= 30
  4871.9  1053.1  4877.5 1052.21  4891.7 1048.57  4898.1 1047.53  4906.7 1044.51
    4912 1042.93  4921.5 1040.59  4927.4  1038.6  4948.5 1030.38  4974.2 1025.52
 4988.11 1021.25  4989.7  1013.3  5010.3  1013.3 5011.21 1018.44 5015.98 1019.77
  5023.1 1021.35  5025.9 1023.23  5029.3 1022.62  5032.1 1022.38  5041.9 1021.99
  5070.3 1021.46  5079.5  1021.5    5111 1022.73  5119.9    1024  5146.9 1029.26
  5158.7 1030.74  5187.8 1035.09  5192.6 1035.52  5216.3  1038.4  5223.1 1039.41
#Mann= 3 ,-1 , 0
  4871.9     .08       0 4988.11     .05       0 5011.21     .08       0
Bank Sta=4988.11,5011.21
Exp/Cntr=0.3,0.1

Type RM Length L Ch R = 1 ,32137   ,348,348,348
BEGIN DESCRIPTION:
Hinton Crk - 61.0
END DESCRIPTION:
XS GIS Cut Line= 5
      1194947.67       621634.19      1195155.63        621684.6
      1195258.56        621674.1      1195306.87       621650.99
      1195346.79       621636.29
#Sta/Elev= 30
    4659 1035.64  4677.3 1032.18  4692.3  1030.4  4705.6 1028.07  4718.5 1027.03
  4748.1 1022.76  4774.5 1022.15  4810.6 1022.19  4834.4 1021.37  4860.7 1022.22
  4867.1 1021.49  4893.8 1020.57  4896.1 1020.24  4900.7 1018.11  4916.4 1018.57
    4923  1018.2  4930.6 1019.21  4937.7 1019.32  4944.8 1018.44  4955.4 1015.01
    4963 1015.42  4978.6 1014.72  4987.9 1013.77  4989.7 1010.81  5010.3 1010.81
 5011.12 1013.78  5031.7 1019.19  5042.1 1022.75  5067.5 1037.95  5072.6 1040.27
#Mann= 3 ,-1 , 0
    4659     .08       0  4987.9     .05       0 5011.12     .08       0
Bank Sta=4987.9,5011.12
Exp/Cntr=0.3,0.1

Type RM Length L Ch R = 1 ,31789   ,316,316,316
BEGIN DESCRIPTION:
Hinton Crk - 60.0
END DESCRIPTION:
XS GIS Cut Line= 4
      1194742.77       621808.66      1195111.52       621945.08
      1195172.43       621980.79      1195225.32       622008.25
#Sta/Elev= 30
  4572.3 1050.82  4595.1 1041.54  4607.5 1035.02  4626.3 1027.07  4635.7 1022.59
  4655.2 1019.99  4683.6    1019  4735.9 1019.37  4771.3 1021.03  4808.4  1024.4
  4816.7 1024.68  4827.9 1026.13  4834.4 1025.58  4857.1 1020.84  4871.9  1019.6
  4907.8 1020.39  4925.8 1019.16  4937.2 1019.26  4959.4 1020.69  4972.3 1016.28
  4983.1 1009.97  4989.7 1007.03  5010.3 1007.03  5022.5 1012.65  5026.6 1013.56
    5033 1015.99  5059.5 1030.77  5074.9 1038.43  5089.3 1047.45  5095.7 1050.98
#Mann= 3 ,-1 , 0
  4572.3     .08       0  4983.1     .05       0  5022.5     .08       0
Bank Sta=4983.1,5022.5
Exp/Cntr=0.3,0.1

Type RM Length L Ch R = 1 ,31473   ,233,233,233
BEGIN DESCRIPTION:
Hinton Crk - 59.0
END DESCRIPTION:
XS GIS Cut Line= 4
      1194928.76       622192.95      1195040.09       622218.16
      1195084.21       622220.26      1195136.72       622218.16
#Sta/Elev= 30
  4864.6 1036.23  4871.8  1033.2  4884.9 1029.56  4889.1 1028.71  4907.8 1022.82
  4922.6 1020.43  4927.8 1019.34  4938.5 1015.05    4943 1012.94  4944.7 1012.61
  4950.9 1010.65  4957.8 1006.97  4965.8 1005.18  4966.7 1005.07  4981.6 1004.57
  4988.6 1003.27  4995.3 1002.95  4999.3 1001.65  5003.7 1001.65  5010.2 1003.35
 5013.36 1005.23  5022.9 1007.48  5026.7 1008.81  5035.2 1012.38  5042.4 1016.65
  5044.6  1018.7    5054 1026.01  5069.7 1035.56  5074.3 1037.72  5075.5 1038.15
#Mann= 3 ,-1 , 0
  4864.6    .088       0  4995.3    .037       0  5010.2     .09       0
Bank Sta=4995.3,5010.2
Exp/Cntr=0.3,0.1

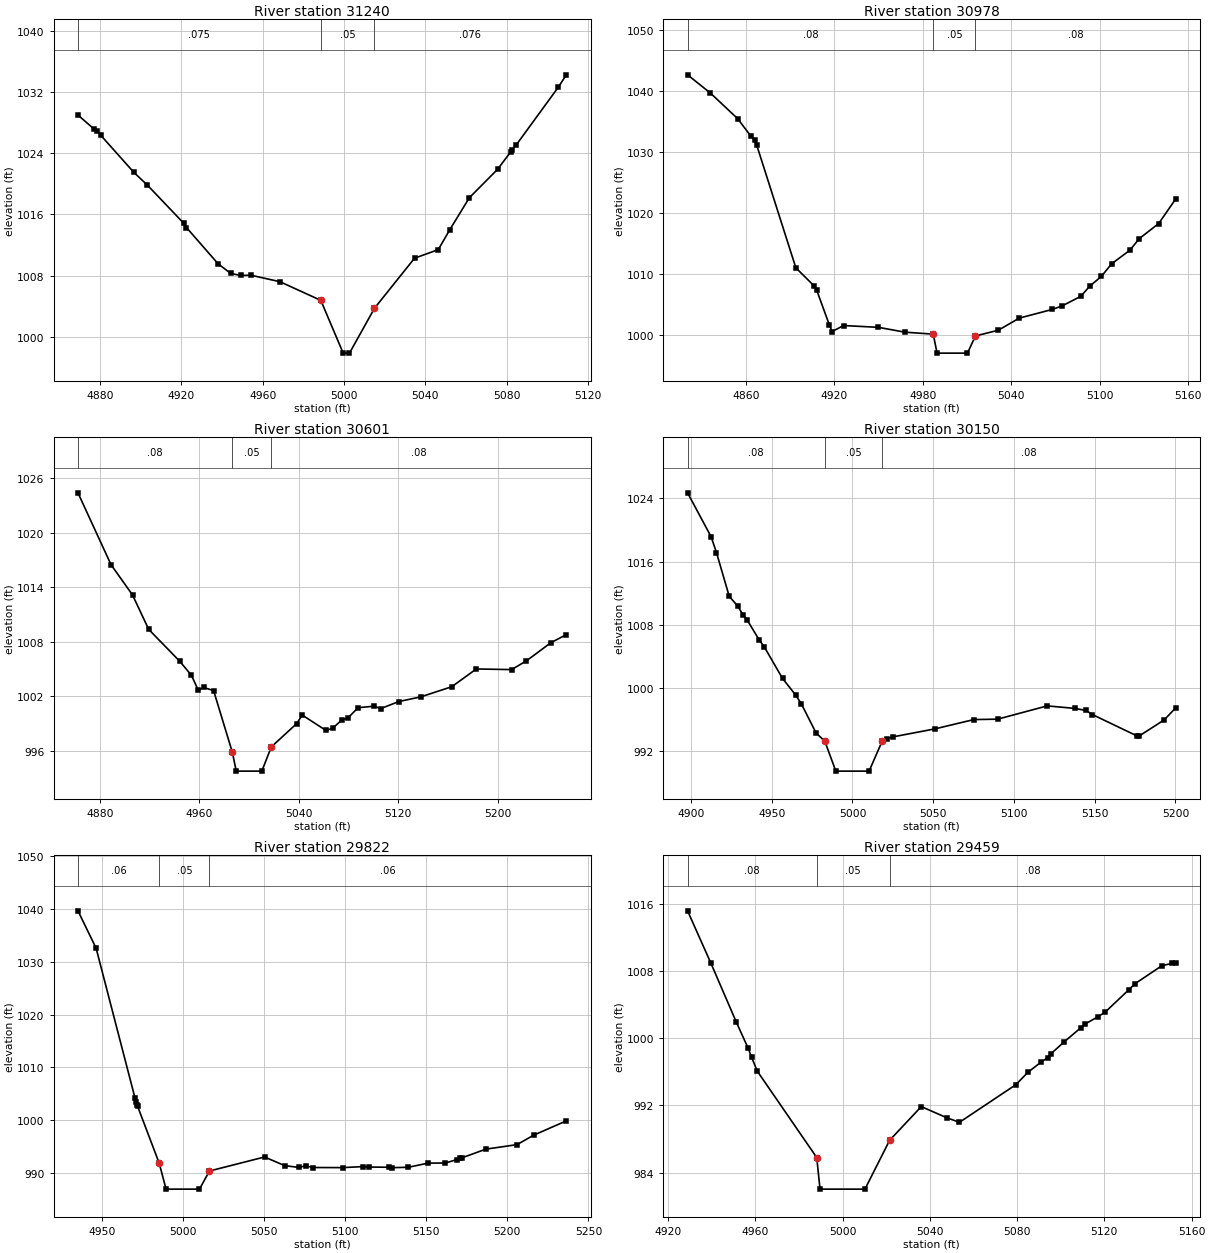
Type RM Length L Ch R = 1 ,31240   ,262,262,262
BEGIN DESCRIPTION:
Hinton Crk - 58.0
END DESCRIPTION:
XS GIS Cut Line= 4
      1194842.63       622369.41      1194937.16       622421.92
      1195000.18       622436.63       1195067.4       622442.93
#Sta/Elev= 27
  4869.1    1029  4877.1 1027.15  4878.7 1026.92  4880.2 1026.39  4896.6  1021.5
  4903.2 1019.85  4921.2 1014.83  4922.5 1014.28  4938.1 1009.53  4944.3 1008.28
  4949.2 1008.02  4954.2 1008.05  4968.5  1007.2  4988.6 1004.76  4999.6  997.86
  5002.7  997.86    5015 1003.73  5034.7 1010.27  5046.4  1011.4  5052.1 1014.02
  5061.7 1018.19  5075.6 1021.91    5082 1024.17  5082.7 1024.49  5084.7 1025.07
  5105.5 1032.66  5109.4 1034.26
#Mann= 3 ,-1 , 0
  4869.1    .075       0  4988.6     .05       0    5015    .076       0
Bank Sta=4988.6,5015
Exp/Cntr=0.3,0.1

Type RM Length L Ch R = 1 ,30978   ,377,377,377
BEGIN DESCRIPTION:
Hinton Crk - 57.0
END DESCRIPTION:
XS GIS Cut Line= 5
      1194695.59       622600.48      1194851.04       622652.99
      1194893.05       622705.51      1194924.56       622726.52
      1194985.48       622716.01
#Sta/Elev= 30
  4820.6 1042.67    4836 1039.69  4854.5 1035.48  4863.7 1032.54  4866.1    1032
  4867.5  1031.1    4894 1010.96  4906.5 1007.96    4908 1007.38  4916.7 1001.58
  4918.6  1000.5  4926.3 1001.48  4949.9 1001.19    4968 1000.39  4987.1 1000.07
  4989.7  996.95  5010.3  996.95 5015.69  999.77  5031.2 1000.71  5045.4  1002.7
  5067.8 1004.13  5074.5 1004.71  5087.1 1006.28  5093.3 1007.98    5101 1009.54
    5108 1011.62  5120.4 1013.86  5126.8 1015.77  5139.9 1018.24  5151.6 1022.33
#Mann= 3 ,-1 , 0
  4820.6     .08       0  4987.1     .05       0 5015.69     .08       0
Bank Sta=4987.1,5015.69
Exp/Cntr=0.3,0.1

Type RM Length L Ch R = 1 ,30601   ,451,451,451
BEGIN DESCRIPTION:
Hinton Crk - 56.0
END DESCRIPTION:
XS GIS Cut Line= 5
      1194580.06       622932.38      1194703.99       622940.78
      1194756.51       622938.68      1194897.25       622932.38
      1194964.47       622898.77
#Sta/Elev= 30
  4862.4 1024.38    4889 1016.48  4906.3 1013.15  4919.3 1009.37  4944.3 1005.86
  4953.7 1004.32  4959.2 1002.67  4963.4 1002.99  4971.5 1002.64  4986.6  995.85
  4989.7  993.79  5010.3  993.79  5017.9  996.45  5038.2     999  5042.8  999.95
  5061.9  998.26  5067.4  998.52  5074.9  999.45  5079.3   999.6  5087.7 1000.76
  5100.6 1000.93  5105.8 1000.66  5120.5 1001.44  5138.1 1001.95  5163.1 1003.07
  5182.8 1005.02  5211.2 1004.95  5223.1 1005.91  5242.8 1007.91  5255.2 1008.79
#Mann= 3 ,-1 , 0
  4862.4     .08       0  4986.6     .05       0  5017.9     .08       0
Bank Sta=4986.6,5017.9
Exp/Cntr=0.3,0.1

Type RM Length L Ch R = 1 ,30150   ,328,328,328
BEGIN DESCRIPTION:
Hinton Crk - 55.0
END DESCRIPTION:
XS GIS Cut Line= 5
       1194739.7       623413.42      1194804.82       623358.81
      1194851.04       623316.79      1194924.56       623255.87
      1194974.97       623224.37
#Sta/Elev= 30
  4897.9 1024.69  4912.5 1019.13  4915.8 1017.13  4923.7  1011.6  4928.9 1010.39
  4932.4  1009.2  4934.8 1008.61  4942.2 1006.11  4945.5 1005.18  4956.7 1001.22
  4964.8  999.13  4968.4  997.99  4977.5  994.32  4982.9  993.28  4989.7   989.5
  5010.3   989.5  5018.5  993.33  5021.3  993.62  5025.3  993.84    5051  994.84
  5075.2  996.02  5089.9  996.07  5120.6  997.75  5137.8  997.43  5144.6  997.17
  5148.6  996.65  5176.5  993.92  5177.5  993.94    5193  995.97  5200.3  997.53
#Mann= 3 ,-1 , 0
  4897.9     .08       0  4982.9     .05       0  5018.5     .08       0
Bank Sta=4982.9,5018.5
Exp/Cntr=0.3,0.1

Type RM Length L Ch R = 1 ,29822   ,363,363,363
BEGIN DESCRIPTION:
Hinton Crk - 54.0
END DESCRIPTION:
XS GIS Cut Line= 4
      1195094.71       623570.97       1195075.8       623484.84
       1195044.3       623360.91      1195031.69       623276.88
#Sta/Elev= 30
  4935.4 1039.58  4946.6 1032.51  4970.6 1004.18  4971.2 1003.42  4971.7 1002.94
  4972.1 1002.72  4985.5   991.9  4989.7  987.03  5010.3  987.03 5016.44  990.45
  5050.4   993.1  5062.8  991.47  5071.4  991.13  5075.7  991.43  5080.4  991.11
  5098.5  991.09  5110.8  991.28  5114.6   991.2  5127.1  991.16  5129.2  991.08
  5139.1  991.16  5151.2  991.94  5161.9  991.96    5169  992.62  5170.6  992.85
  5171.8  992.91  5186.8  994.58    5206  995.43  5216.3  997.22  5236.4  999.92
#Mann= 3 ,-1 , 0
  4935.4     .06       0  4985.5     .05       0 5016.44     .06       0
Bank Sta=4985.5,5016.44
Exp/Cntr=0.3,0.1

Type RM Length L Ch R = 1 ,29459   ,217,217,217
BEGIN DESCRIPTION:
Hinton Crk - 53.0
END DESCRIPTION:
XS GIS Cut Line= 4
      1195252.26       623226.47      1195199.74       623199.16
      1195159.83       623190.76      1195040.09       623159.25
#Sta/Elev= 28
    4929 1015.17  4939.6 1008.99  4951.4 1001.88  4956.8  998.78  4958.3  997.76
  4960.9  996.09  4988.2  985.78  4989.7  982.02  5010.3  982.02  5021.6  987.84
  5036.1  991.85    5048   990.5  5053.6  989.98  5079.5  994.47  5084.9  995.92
  5091.1  997.17    5094  997.67  5095.5  998.14  5101.5  999.54  5109.2 1001.24
    5111 1001.66  5116.9 1002.53  5120.3 1003.09  5131.3 1005.79    5134 1006.48
  5146.4 1008.64  5151.2 1008.92  5152.8 1008.98
#Mann= 3 ,-1 , 0
    4929     .08       0  4988.2     .05       0  5021.6     .08       0
Bank Sta=4988.2,5021.6
Exp/Cntr=0.3,0.1

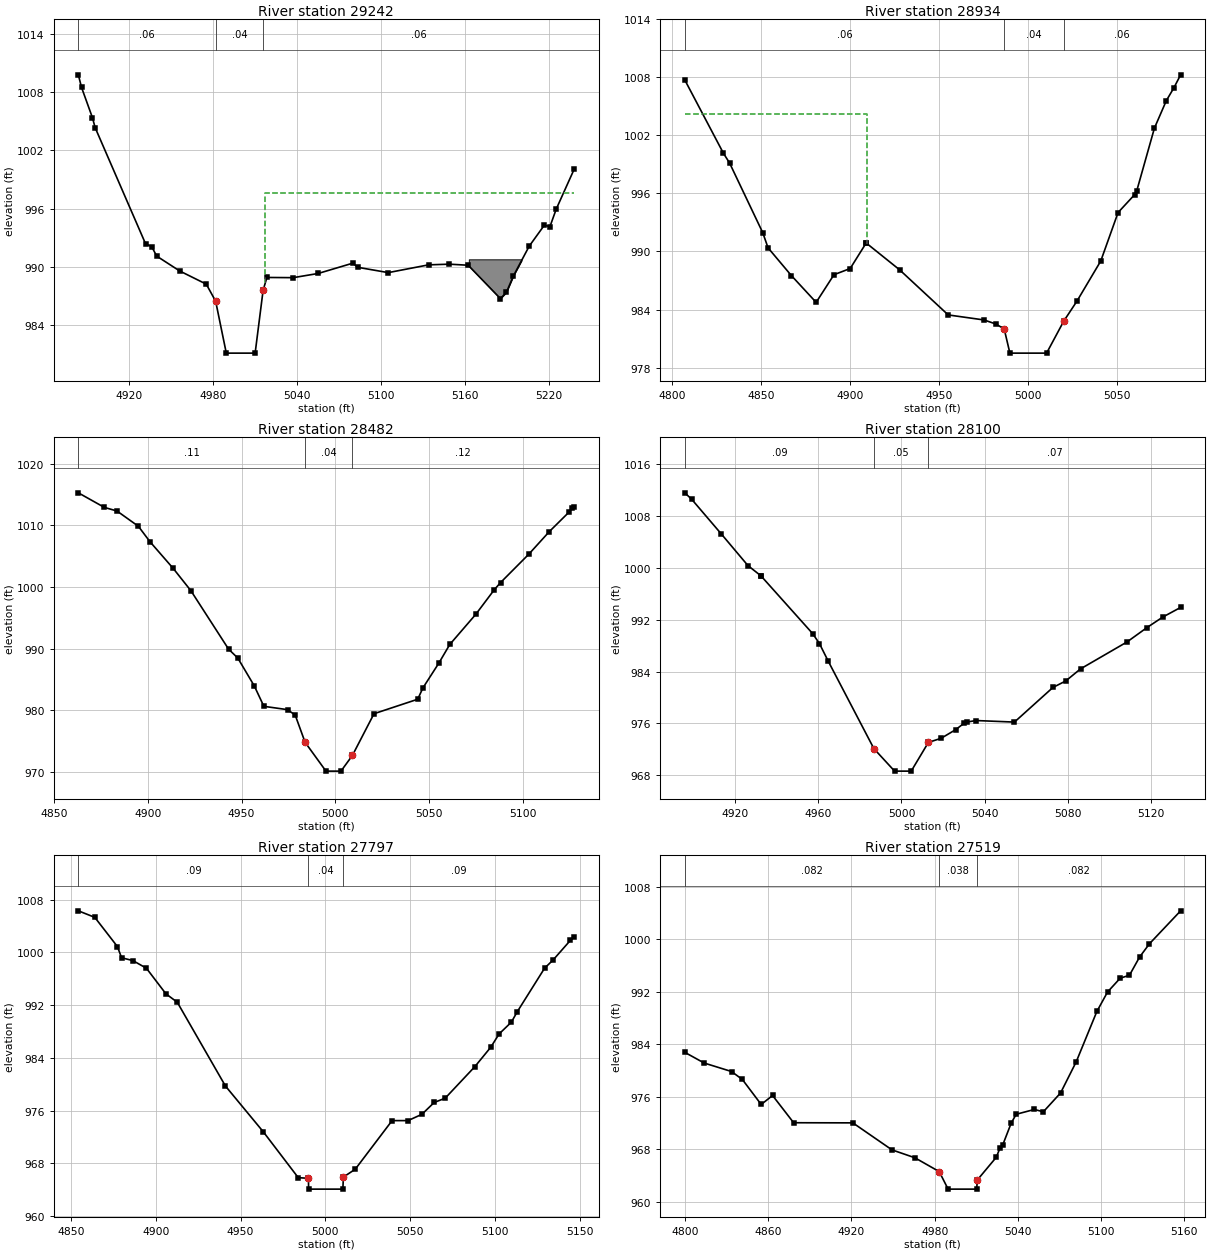
Type RM Length L Ch R = 1 ,29242   ,308,308,308
BEGIN DESCRIPTION:
Hinton Crk - 52.0
END DESCRIPTION:
XS GIS Cut Line= 5
      1195306.87       623054.21      1195235.45       622986.99
      1195189.24       622974.39       1195050.6       622900.87
      1195021.19       622858.86
#Sta/Elev= 30
    4884 1009.79  4886.3 1008.49  4894.1 1005.36    4896 1004.35    4932  992.38
  4936.4  992.08    4940   991.1  4956.4  989.57  4975.4  988.21  4982.1  986.45
  4989.7   981.1  5010.3   981.1    5016  987.58  5018.7   988.9  5037.5  988.88
  5055.3  989.31  5080.2  990.38  5083.5  989.95  5105.4   989.4  5134.2   990.2
  5149.1  990.27  5162.5  990.16  5185.5  986.72  5189.8  987.37  5194.8  989.06
  5206.1  992.13  5216.9  994.29  5220.9  994.14  5225.4  995.95  5238.2 1000.06
#Mann= 3 ,-1 , 0
    4884     .06       0  4982.1     .04       0    5016     .06       0
#XS Ineff= 2 , 0
                         5017.53          997.59
Permanent Ineff=
       F       F
#Block Obstruct= 1 ,-1
 5162.94 5200.59  990.77
Bank Sta=4982.1,5016
Exp/Cntr=0.3,0.1

Type RM Length L Ch R = 1 ,28934   ,452,452,452
BEGIN DESCRIPTION:
Hinton Crk - 51.0
END DESCRIPTION:
XS GIS Cut Line= 4
      1195424.51       622871.46      1195336.28       622728.62
      1195325.78        622678.2      1195325.78       622619.38
#Sta/Elev= 28
  4807.3 1007.74    4829 1000.15  4832.4  999.16  4851.1  991.92    4854  990.38
  4867.1  987.51    4881  984.74    4891   987.6  4900.1  988.24    4909  990.86
  4909.2  990.86  4927.8  988.11  4955.1  983.44  4975.2  982.92  4981.7  982.51
  4986.5     982  4989.7  979.49  5010.3  979.49  5019.9  982.79  5027.4  984.89
  5040.7  989.02  5050.4  994.03  5059.7  995.88  5060.8  996.22  5070.8 1002.76
  5077.5 1005.61  5081.7 1006.92  5085.5 1008.27
#Mann= 3 ,-1 , 0
  4807.3     .06       0  4986.5     .04       0  5019.9     .06       0
#XS Ineff= 2 , 0
         4909.76 1004.27
Permanent Ineff=
       F       F
Bank Sta=4986.5,5019.9
Exp/Cntr=0.3,0.1

Type RM Length L Ch R = 1 ,28482   ,382,382,382
BEGIN DESCRIPTION:
Hinton Crk - 50.0
END DESCRIPTION:
XS GIS Cut Line= 4
      1195768.92       622872.35      1195781.03       622769.44
      1195774.98       622669.57        1195778.       622609.03
#Sta/Elev= 30
    4863 1015.28  4876.9 1012.91  4883.6 1012.33    4895 1009.85  4901.2 1007.34
  4913.6    1003    4923  999.39  4943.1   989.9    4948  988.46  4956.8  983.93
  4961.9  980.62 4974.53  980.08 4978.61  979.19 4983.87  974.78    4995   970.1
    5003   970.1  5009.1  972.65 5020.61  979.42  5043.9  981.77  5046.7  983.62
  5055.1   987.6    5061  990.66  5074.9  995.57  5084.8  999.58  5088.1 1000.72
  5103.1 1005.31  5114.1    1009  5124.4  1012.1  5126.3 1012.84  5127.3 1013.04
#Mann= 3 ,-1 , 0
    4863     .11       0 4983.87     .04       0  5009.1     .12       0
Bank Sta=4983.87,5009.1
Exp/Cntr=0.3,0.1

Type RM Length L Ch R = 1 ,28100   ,303,303,303
BEGIN DESCRIPTION:
Hinton Crk - 49.0
END DESCRIPTION:
XS GIS Cut Line= 3
      1196216.86       622808.79      1196150.28       622708.91
      1196110.93       622596.93
#Sta/Elev= 26
  4895.7 1011.59    4899  1010.6  4913.2 1005.27  4926.1 1000.36  4932.3  998.79
  4932.6  998.69  4957.3  989.84  4960.5  988.33  4964.8  985.57 4986.74   972.1
  4996.7  968.63  5004.7  968.63 5012.96  973.06  5019.1   973.7  5026.2  975.05
  5030.2  976.04  5031.4   976.2  5035.9  976.44  5054.4   976.2  5072.9  981.54
  5079.1  982.55  5086.2  984.41  5108.6  988.57  5118.2  990.79  5125.8  992.41
  5134.4   993.9
#Mann= 3 ,-1 , 0
  4895.7     .09       0 4986.74     .05       0 5012.96     .07       0
Bank Sta=4986.74,5012.96
Exp/Cntr=0.3,0.1

Type RM Length L Ch R = 1 ,27797   ,278,278,278
BEGIN DESCRIPTION:
Hinton Crk - 48.0
END DESCRIPTION:
XS GIS Cut Line= 4
      1196410.56       622672.59      1196404.51       622563.63
      1196371.22       622478.89      1196328.85       622397.17
#Sta/Elev= 30
  4854.4 1006.29  4864.1  1005.3  4877.4 1000.88  4879.9  999.17  4886.5  998.75
  4894.5  997.59    4906  993.71  4912.7  992.43  4941.1  979.72  4963.5  972.75
    4984  965.83 4990.02  965.73  4990.1  964.09  5010.3  964.09  5010.6  965.92
  5017.6  967.11  5039.3  974.48  5048.7  974.48  5056.9  975.44  5064.1  977.23
  5070.6  977.88  5088.1  982.67  5097.4  985.59  5102.4  987.63  5109.6  989.41
    5113  990.96  5129.2   997.6  5134.2  998.84  5144.4 1001.82  5146.6 1002.31
#Mann= 3 ,-1 , 0
  4854.4     .09       0 4990.02     .04       0  5010.6     .09       0
Bank Sta=4990.02,5010.6
Exp/Cntr=0.3,0.1

Type RM Length L Ch R = 1 ,27519   ,372,372,372
BEGIN DESCRIPTION:
Hinton Crk - 47.0
END DESCRIPTION:
XS GIS Cut Line= 4
      1196534.65       622618.11      1196634.53       622469.81
      1196682.96       622406.25      1196773.76       622366.91
#Sta/Elev= 30
  4799.8  982.75  4813.8  981.12  4833.5  979.83  4841.3  978.62  4854.9  974.81
  4863.1  976.18  4878.3  972.03    4921  972.01  4949.2   967.9  4965.7   966.7
  4983.3  964.59  4989.7  961.92  5010.3  961.92  5010.8  963.32  5024.4  966.76
    5027  968.11  5029.2   968.7  5035.2  971.97  5038.8  973.32  5051.9  974.05
  5058.4   973.7  5070.8  976.56  5082.1  981.31    5097  988.98  5104.7  991.94
  5113.8  994.04  5120.5  994.49  5127.8  997.26  5134.9  999.28  5157.4  1004.3
#Mann= 3 ,-1 , 0
  4799.8    .082       0  4983.3    .038       0  5010.8    .082       0
Bank Sta=4983.3,5010.8
Exp/Cntr=0.3,0.1