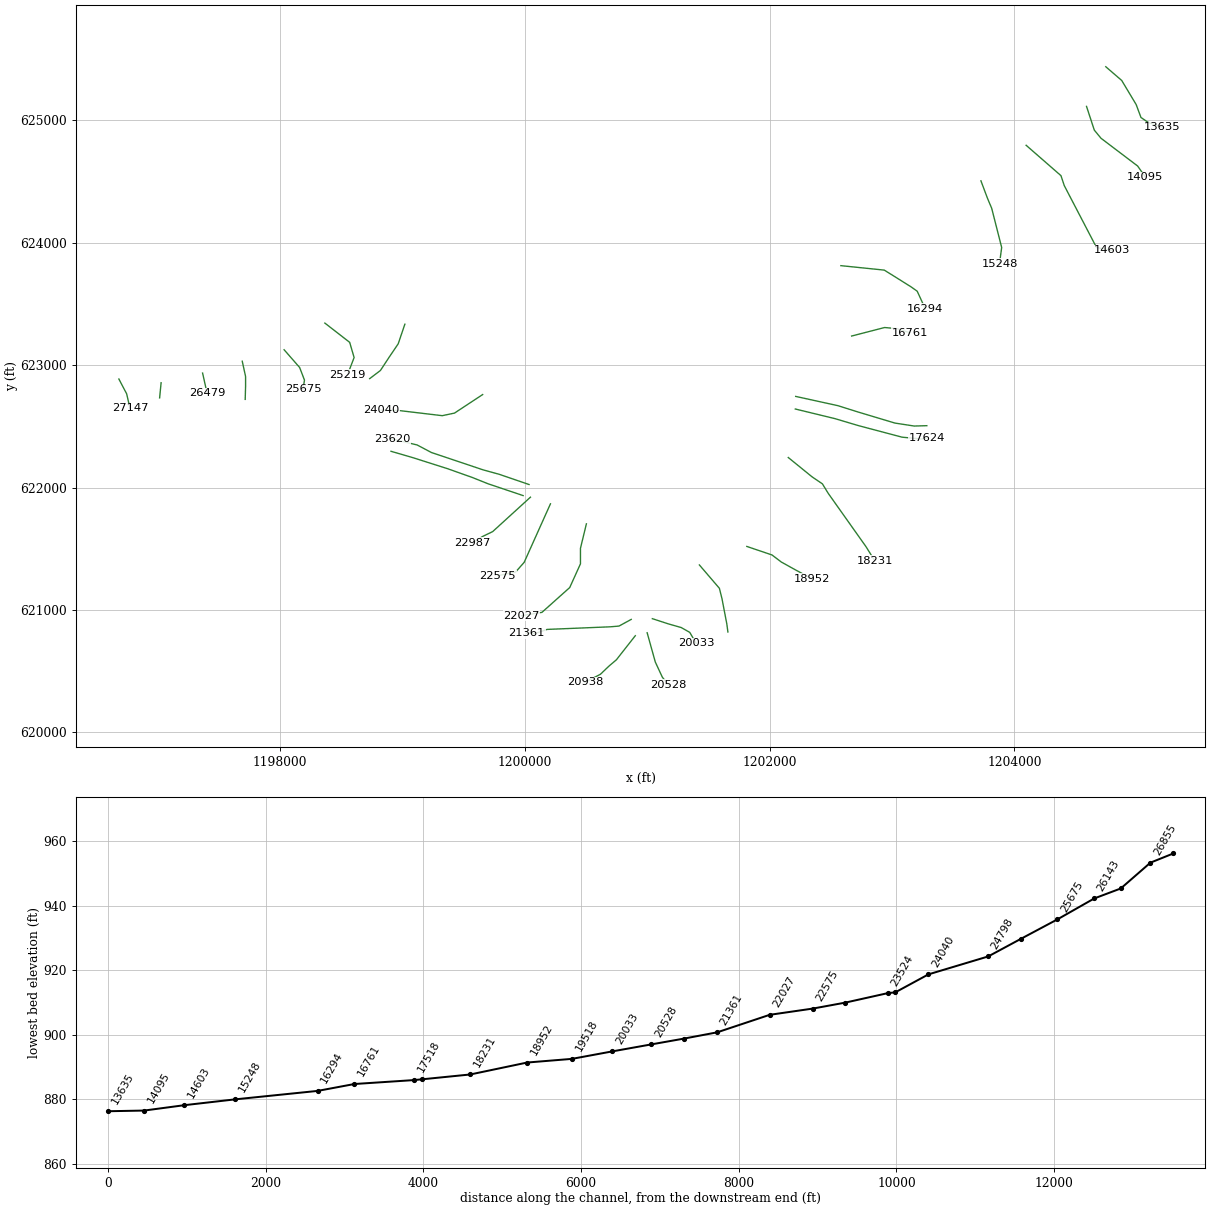
HEC-RAS study lds_hinton_crk.prj: Hinton Creek Limited Detail Study

--- lds_hinton_crk.g01 (geometry) --- (continued)

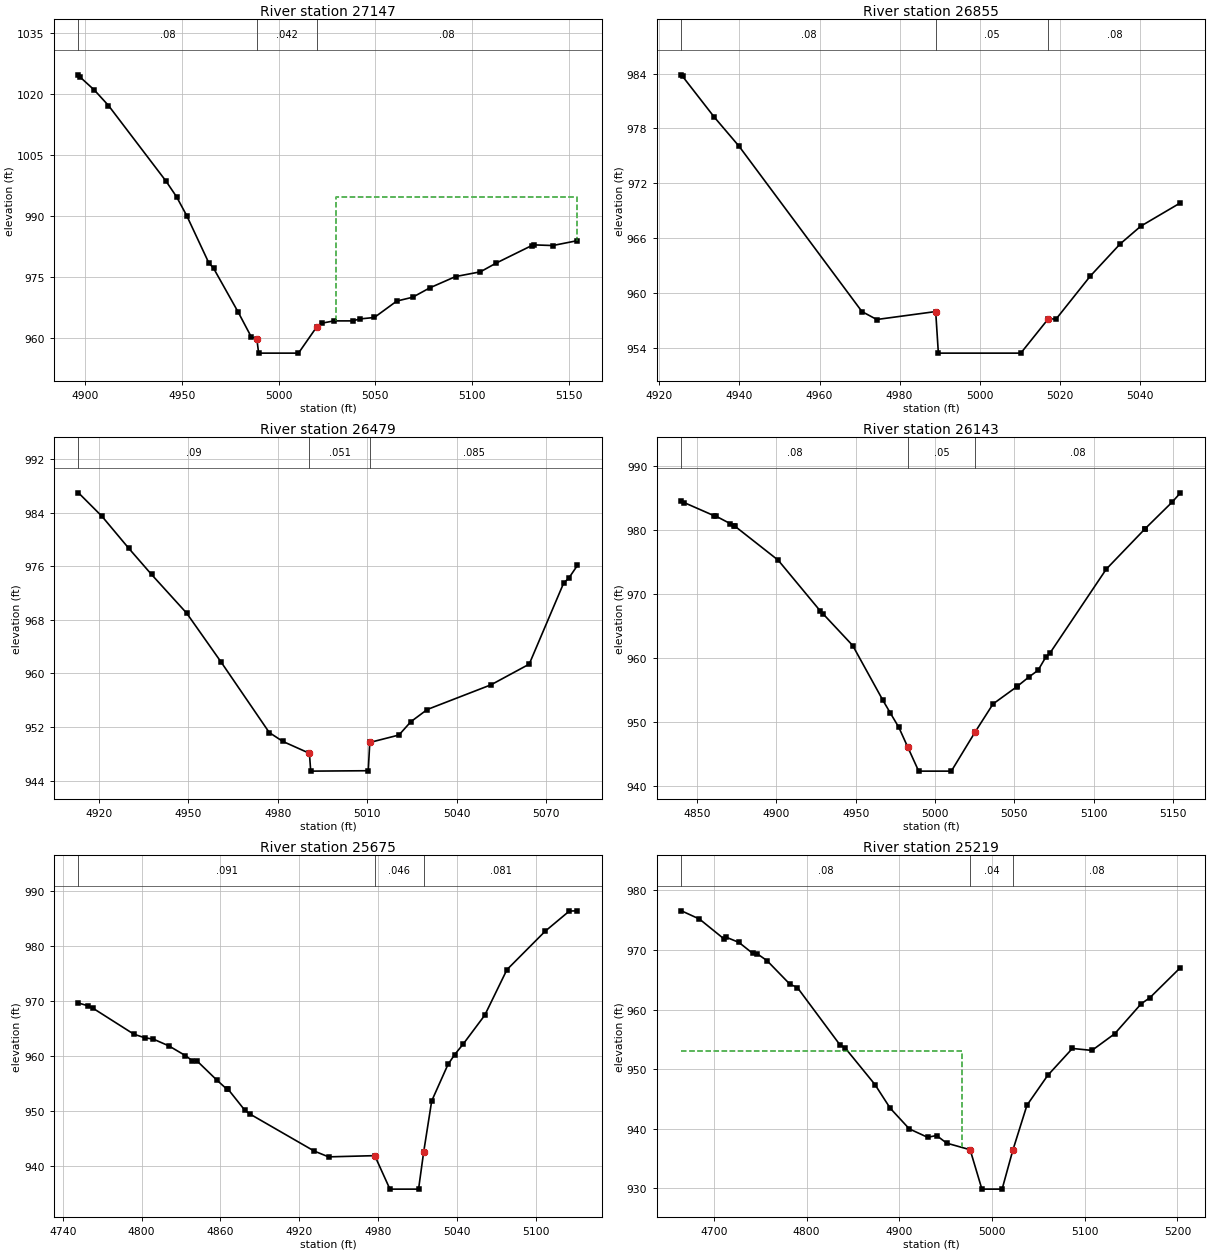
Type RM Length L Ch R = 1 ,27147   ,292,292,292
BEGIN DESCRIPTION:
Hinton Crk - 46.0
END DESCRIPTION:
XS GIS Cut Line= 3
      1196682.96       622887.48      1196746.52       622766.42
      1196773.76       622648.38
#Sta/Elev= 30
  4896.6 1024.74  4897.6 1024.11  4904.8 1020.99  4912.1 1017.19  4941.9  998.54
  4947.3  994.72  4952.5  990.13  4963.9  978.52  4966.4  977.16  4979.2   966.3
  4985.8  960.34  4988.8  959.69  4989.7  956.27  5010.3  956.27  5019.8  962.77
  5022.3  963.63  5028.6   964.2  5038.3   964.2    5042  964.68  5049.5  965.04
  5061.1  969.08  5069.3  970.02  5078.3  972.36  5091.5  975.11  5104.3  976.27
  5112.5  978.43  5130.8  982.72  5132.2   982.9  5141.7  982.74  5154.5  983.95
#Mann= 3 ,-1 , 0
  4896.6     .08       0  4988.8    .042       0  5019.8     .08       0
#XS Ineff= 2 , 0
                         5029.54          994.73
Permanent Ineff=
       F       F
Bank Sta=4988.8,5019.8
Exp/Cntr=0.3,0.1

Type RM Length L Ch R = 1 ,26855   ,376,376,376
BEGIN DESCRIPTION:
Hinton Crk - 45.0
END DESCRIPTION:
XS GIS Cut Line= 2
      1197027.99       622857.21      1197015.88       622733.12
#Sta/Elev= 15
  4925.5  983.86  4925.8  983.68  4933.7  979.23  4939.9  976.04  4970.6  957.95
  4974.3  957.08 4989.03  957.95  4989.7   953.4  5010.3   953.4  5017.2  957.17
  5019.1  957.12  5027.7  961.85  5035.1  965.34  5040.3   967.3  5050.2  969.85
#Mann= 3 ,-1 , 0
  4925.5     .08       0 4989.03     .05       0  5017.2     .08       0
Bank Sta=4989.03,5017.2
Exp/Cntr=0.3,0.1

Type RM Length L Ch R = 1 ,26479   ,336,336,336
BEGIN DESCRIPTION:
Hinton Crk - 44.0
END DESCRIPTION:
XS GIS Cut Line= 2
      1197366.97       622935.91      1197403.29       622772.47
#Sta/Elev= 20
  4913.1  986.95    4921  983.43  4929.9   978.7  4937.6  974.76  4949.4  968.98
  4960.9  961.71  4977.1  951.16 4981.63  949.84 4990.57  948.06    4991   945.4
  5010.3  945.46 5010.82  949.68  5020.6  950.79  5024.6  952.78  5030.1   954.6
  5051.5  958.29  5064.3  961.37  5075.9  973.52  5077.5  974.16  5080.5  976.13
#Mann= 3 ,-1 , 0
  4913.1     .09       0 4990.57    .051       0 5010.82    .085       0
Bank Sta=4990.57,5010.82
Exp/Cntr=0.3,0.1

Type RM Length L Ch R = 1 ,26143   ,468,468,468
BEGIN DESCRIPTION:
Hinton Crk - 43.0
END DESCRIPTION:
XS GIS Cut Line= 4
      1197690.82       623032.76      1197718.06       622908.67
      1197718.06       622823.92      1197715.03       622721.02
#Sta/Elev= 30
  4840.1   984.5  4841.9  984.31  4860.4   982.3  4861.7  982.22  4870.8  981.04
  4873.4  980.72  4873.6  980.67  4901.1  975.31  4927.4  967.44  4929.5  966.89
  4948.1  961.96  4967.1  953.41  4971.8  951.41  4977.2  949.15  4982.7  946.13
  4989.7  942.31  5010.3  942.31 5025.45  948.49  5036.6  952.82  5051.5   955.5
  5051.9  955.58  5059.2  957.03    5065  958.09  5069.8  960.12  5072.7  960.85
    5108  973.91  5132.3  980.18  5132.4  980.21  5149.4  984.36  5154.8  985.85
#Mann= 3 ,-1 , 0
  4840.1     .08       0  4982.7     .05       0 5025.45     .08       0
Bank Sta=4982.7,5025.45
Exp/Cntr=0.3,0.1

Type RM Length L Ch R = 1 ,25675   ,456,456,456
BEGIN DESCRIPTION:
Hinton Crk - 42.0
END DESCRIPTION:
XS GIS Cut Line= 4
      1198032.82       623126.58      1198159.94       622981.31
      1198199.29        622878.4      1198187.18       622802.74
#Sta/Elev= 30
    4752  969.66  4759.2  969.17  4762.7  968.77  4794.2  963.99  4802.7  963.33
  4808.9  963.11  4820.8  961.87  4833.4   960.1  4838.5   959.2  4842.5  959.07
  4857.4  955.63    4865  953.99  4865.8  954.01  4878.5   950.2  4882.9  949.42
  4931.4  942.74  4942.4  941.68 4977.56   941.9  4989.1  935.81  5010.9  935.81
  5014.8  942.58  5020.9  951.85  5033.3  958.49  5038.3  960.25    5045  962.24
  5061.3  967.45  5078.2  975.74  5107.3  982.73  5125.7   986.4  5131.9  986.44
#Mann= 3 ,-1 , 0
    4752    .091       0 4977.56    .046       0  5014.8    .081       0
Bank Sta=4977.56,5014.8
Exp/Cntr=0.3,0.1

Type RM Length L Ch R = 1 ,25219   ,421,421,421
BEGIN DESCRIPTION:
Hinton Crk - 41.0
END DESCRIPTION:
XS GIS Cut Line= 4
      1198365.75        623344.5      1198568.53       623187.11
      1198604.85       623063.02      1198550.37       622920.77
#Sta/Elev= 30
    4665  976.58  4684.4   975.2  4710.4  971.93  4713.1  972.16    4727  971.28
    4742  969.42  4746.7  969.37  4757.3  968.22    4782  964.26    4790  963.71
  4835.8  954.12  4841.6  953.56  4873.7  947.43  4890.2  943.45  4910.8  939.98
  4930.5  938.57  4940.2  938.87  4951.1  937.59  4976.4  936.48  4989.1  929.87
  5010.9  929.87 5022.41  936.37  5037.7  943.95  5060.1  948.96  5086.7  953.48
  5107.8  953.15  5132.3  955.94    5161  960.99  5170.2  961.98  5203.3  967.06
#Mann= 3 ,-1 , 0
    4665     .08       0  4976.4     .04       0 5022.41     .08       0
#XS Ineff= 2 , 0
         4967.33     953
Permanent Ineff=
       F       F
Bank Sta=4976.4,5022.41
Exp/Cntr=0.3,0.1

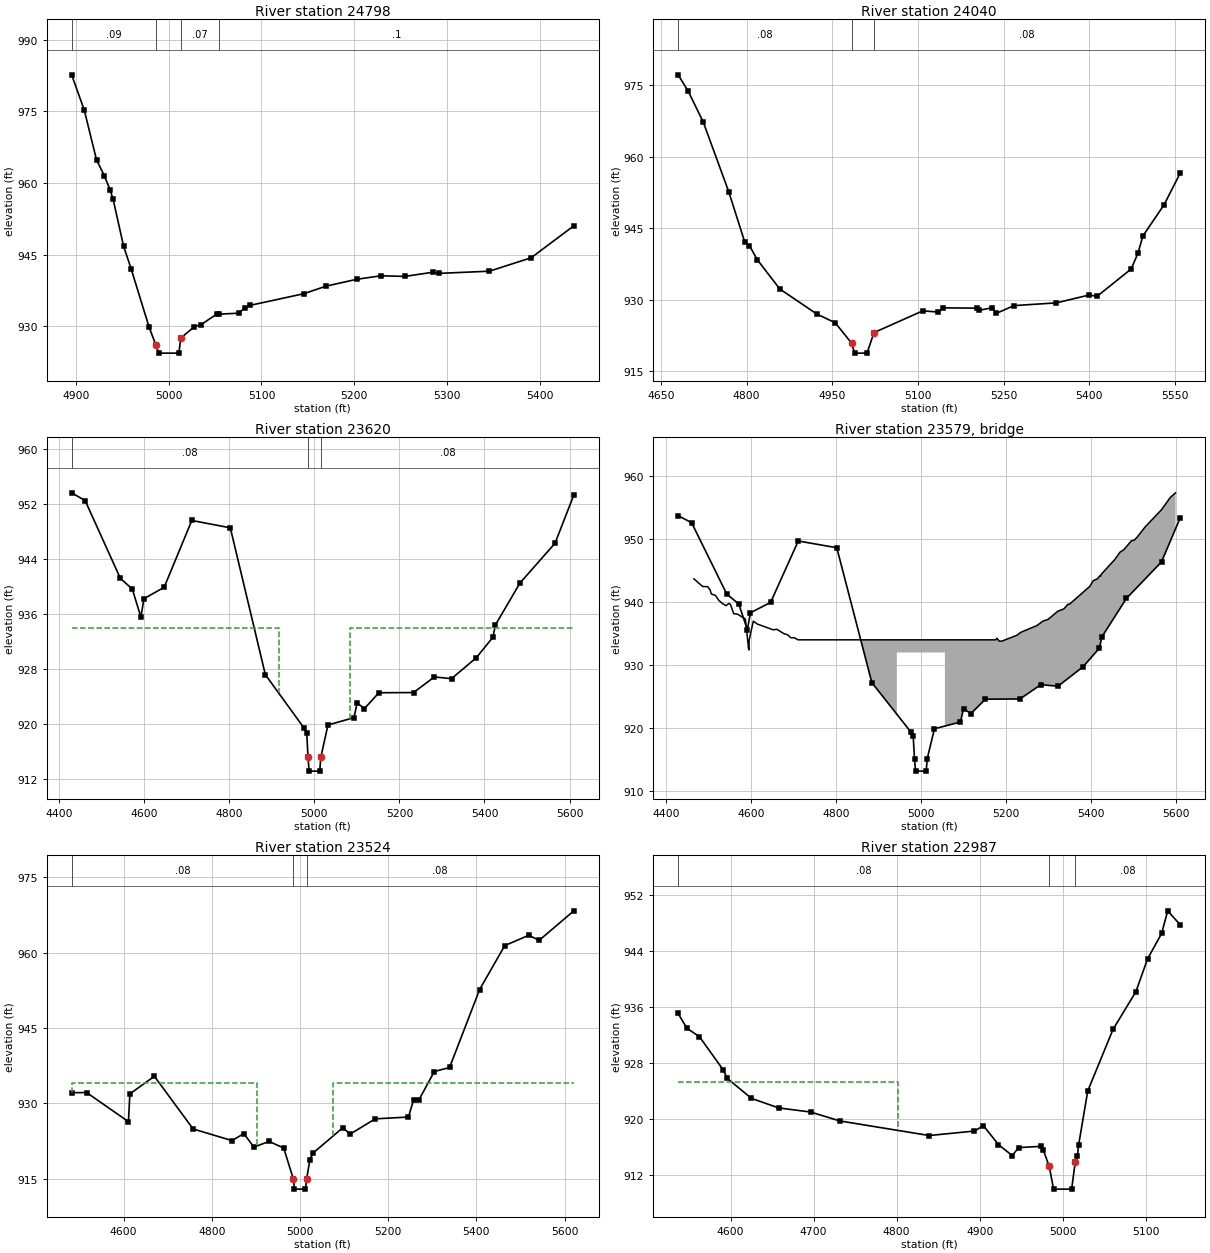
Type RM Length L Ch R = 1 ,24798   ,758,758,758
BEGIN DESCRIPTION:
Hinton Crk - 40.0
END DESCRIPTION:
XS GIS Cut Line= 5
       1199019.5       623335.42      1198965.02       623175.01
      1198889.35       623063.02      1198819.74       622957.09
      1198731.97       622890.51
#Sta/Elev= 30
  4895.3  982.69  4908.9  975.29  4922.1  964.87  4930.5  961.55  4936.7   958.6
    4940  956.59  4951.3  946.77  4959.6  941.91  4978.8  929.79    4986  926.08
  4989.1  924.33  5010.9  924.33    5013  927.49  5027.6  929.87    5035  930.32
  5051.7  932.51  5053.9   932.5  5075.6  932.71  5081.7  933.81  5087.5  934.34
  5145.6  936.79  5169.8  938.39  5202.7  939.81  5228.6  940.55  5254.7  940.42
  5284.7  941.29    5291  941.05  5345.7  941.51  5390.8  944.33  5436.8  951.03
#Mann= 4 ,-1 , 0
  4895.3     .09       0    4986    .042       0    5013     .07       0
  5053.9      .1       0
Bank Sta=4986,5013
Exp/Cntr=0.3,0.1

Type RM Length L Ch R = 1 ,24040   ,420,420,420
BEGIN DESCRIPTION:
Hinton Crk - 39.0
END DESCRIPTION:
XS GIS Cut Line= 5
      1199655.08       622760.36      1199425.06       622609.03
      1199325.18       622587.85      1198968.04       622630.22
      1198825.79       622633.25
#Sta/Elev= 30
  4680.1  977.24  4697.9  973.77  4724.1  967.32  4768.7  952.69  4796.7  942.14
    4805  941.38  4818.5  938.42  4858.2  932.24    4923  926.98  4955.3  925.14
  4984.1  920.82  4989.1  918.77  5010.9  918.77    5023  923.08  5108.5  927.65
    5136   927.4    5144  928.28  5203.1  928.22  5206.5  927.75    5230  928.31
  5237.1  927.11    5268  928.75  5342.4  929.33  5400.2  930.99  5413.5  930.69
  5473.3  936.44  5485.3  939.78  5493.9  943.38  5531.1  949.97  5559.4  956.63
#Mann= 3 ,-1 , 0
  4680.1     .08       0  4984.1     .05       0    5023     .08       0
Bank Sta=4984.1,5023
Exp/Cntr=0.5,0.3

Type RM Length L Ch R = 1 ,23620   ,96,96,96
BEGIN DESCRIPTION:
Stroud Rd SR 1357 - US
END DESCRIPTION:
XS GIS Cut Line= 6
      1200034.11       622025.39      1199788.49       622109.41
      1199659.22       622144.96      1199235.87       622287.16
      1199119.52       622348.56      1198915.92       622397.04
#Sta/Elev= 30
    4429  953.68  4460.8  952.55  4543.6  941.23  4571.6  939.69  4591.9   935.6
    4599  938.28  4646.6  939.94  4711.6  949.66  4802.2  948.59  4884.6  927.23
  4976.1  919.43  4981.9  918.73    4985   915.2  4987.5   913.2  5012.5   913.2
    5015   915.2  5031.9  919.91    5093  920.98  5100.5  923.11  5117.6   922.3
  5151.7   924.6  5233.1  924.63  5282.2   926.9  5322.5  926.65  5381.1  929.71
  5419.8  932.67  5425.8  934.47  5483.6  940.57    5566  946.35  5610.2  953.37
#Mann= 3 ,-1 , 0
    4429     .08       0    4985     .05       0    5015     .08       0
#XS Ineff= 2 , 0
       0  4916.5     934  5083.5       0     934
Permanent Ineff=
       F       F
Bank Sta=4985,5015
Exp/Cntr=0.5,0.3

Type RM Length L Ch R = 3 ,23579   ,,,
BEGIN DESCRIPTION:
Stroud Rd SR 1357
Structure ID: Stroud Rd SR 1357
Approximate Survey Structure
END DESCRIPTION:
Bridge Culvert--1,0,-1,-1, 0
Deck Dist Width WeirC Skew NumUp NumDn MinLoCord MaxHiCord MaxSubmerge Is_Ogee
27,28,3,0, 60, 60, , , , 0, 1,1,,
  4466.2  4486.7  4498.6  4504.2  4507.1    4517  4524.3  4533.1  4541.8  4548.1
  4552.1  4559.8  4568.4  4587.1  4593.5  4594.5  4595.7    4596  4605.8  4615.4
  4652.5  4661.3  4677.5  4686.8  4694.4  4702.5    4711  4943.5  4943.5  5056.5
  5056.5  5176.1    5179  5184.2  5190.2  5226.4  5234.6  5273.1  5287.1  5298.7
  5322.2  5336.4  5345.8    5350  5397.4  5405.3  5415.4  5420.9  5422.6  5424.1
  5456.1  5468.2  5477.4    5495    5502  5508.5    5528  5565.9  5586.5    5599
  943.66  942.45  942.42   941.9  941.27  941.03  940.29  939.75  939.41  939.77
   939.6  938.14  938.08   937.3  933.44  932.63   932.4   933.9  936.96   936.5
  935.59  935.67  934.99  934.79  934.32  934.33     934     934     934     934
     934     934  934.26  933.79  933.79  934.74  935.18  936.27  936.97  937.22
  938.54  938.91  939.63  939.67  942.48  943.36  943.68  944.15  944.08  944.37
  946.73  947.88  948.28  949.68   949.8  950.26  951.93  954.61  956.55  957.29
   893.2   893.2   893.2   893.2   893.2   893.2   893.2   893.2   893.2   893.2
   893.2   893.2   893.2   893.2   893.2   893.2   893.2   893.2   893.2   893.2
   893.2   893.2   893.2   893.2   893.2   893.2   893.2   893.2     932     932
   893.2   893.2   893.2   893.2   893.2   893.2   893.2   893.2   893.2   893.2
   893.2   893.2   893.2   893.2   893.2   893.2   893.2   893.2   893.2   893.2
   893.2   893.2   893.2   893.2   893.2   893.2   893.2   893.2   893.2   893.2
  4466.2  4486.7  4498.6  4504.2  4507.1    4517  4524.3  4533.1  4541.8  4548.1
  4552.1  4559.8  4568.4  4587.1  4593.5  4594.5  4595.7    4596  4605.8  4615.4
  4652.5  4661.3  4677.5  4686.8  4694.4  4702.5    4711  4943.5  4943.5  5056.5
  5056.5  5176.1    5179  5184.2  5190.2  5226.4  5234.6  5273.1  5287.1  5298.7
  5322.2  5336.4  5345.8    5350  5397.4  5405.3  5415.4  5420.9  5422.6  5424.1
  5456.1  5468.2  5477.4    5495    5502  5508.5    5528  5565.9  5586.5    5599
  943.66  942.45  942.42   941.9  941.27  941.03  940.29  939.75  939.41  939.77
   939.6  938.14  938.08   937.3  933.44  932.63   932.4   933.9  936.96   936.5
  935.59  935.67  934.99  934.79  934.32  934.33     934     934     934     934
     934     934  934.26  933.79  933.79  934.74  935.18  936.27  936.97  937.22
  938.54  938.91  939.63  939.67  942.48  943.36  943.68  944.15  944.08  944.37
  946.73  947.88  948.28  949.68   949.8  950.26  951.93  954.61  956.55  957.29
   893.2   893.2   893.2   893.2   893.2   893.2   893.2   893.2   893.2   893.2
   893.2   893.2   893.2   893.2   893.2   893.2   893.2   893.2   893.2   893.2
   893.2   893.2   893.2   893.2   893.2   893.2   893.2   893.2     932     932
   893.2   893.2   893.2   893.2   893.2   893.2   893.2   893.2   893.2   893.2
   893.2   893.2   893.2   893.2   893.2   893.2   893.2   893.2   893.2   893.2
   893.2   893.2   893.2   893.2   893.2   893.2   893.2   893.2   893.2   893.2
Abutment Skew #Up #Dn= , 2 , 2
  4943.5  4948.5
     932   921.9
  4943.5  4948.5
     932  921.31
Abutment Skew #Up #Dn= , 2 , 2
  5051.5  5056.5
  920.53     932
  5051.5  5056.5
  921.96     932
BR Coef= 1 , 1 , 0 ,1.25, 0 ,,,0.8,0,2,0,
WSPro=,,,, 1 ,,,, 0 ,,,, 0 ,,,,-1 ,-1 ,-1 , 0 , 0 , 0 , 0 , 0
BC Design=,, 0 ,, 0 ,,,,,,
BC HTab HWMax=953.68

Type RM Length L Ch R = 1 ,23524   ,537,537,537
BEGIN DESCRIPTION:
Stroud Rd SR 1357 - DS
END DESCRIPTION:
XS GIS Cut Line= 6
      1199985.63        621934.9        1199698.       622031.85
      1199568.73       622083.56      1199368.37       622154.66
      1199083.97       622245.15      1198906.23       622296.86
#Sta/Elev= 30
  4482.2  932.13  4516.1  932.17    4611  926.37  4614.2   931.9  4669.8   935.4
  4757.7  924.92  4845.7  922.61  4872.8  923.99  4895.4  921.31  4930.2  922.44
  4963.2  921.11    4985  914.95  4987.5  912.95  5012.5  912.95    5015  914.95
  5022.6  918.81  5029.4  920.11  5096.7  925.13  5114.2  923.92  5170.7  926.93
    5246  927.29  5257.9  930.78  5269.3  930.64  5304.7  936.35  5339.3  937.15
  5407.4  952.66  5464.4   961.4  5518.8  963.45  5542.6  962.46  5621.1  968.32
#Mann= 3 ,-1 , 0
  4482.2     .08       0    4985     .05       0    5015     .08       0
#XS Ineff= 2 , 0
       0  4902.5     934  5075.8       0  934.12
Permanent Ineff=
       F       F
Bank Sta=4985,5015
Exp/Cntr=0.5,0.3

Type RM Length L Ch R = 1 ,22987   ,412,412,412
BEGIN DESCRIPTION:
Hinton Crk - 38.0
END DESCRIPTION:
XS GIS Cut Line= 4
      1200045.51       621921.99       1199736.8       621640.52
      1199655.08       621601.17      1199573.36       621549.72
#Sta/Elev= 30
  4536.7  935.09  4547.3  932.97  4562.3  931.79  4591.1  927.03  4595.8  925.84
  4625.1  922.97  4657.9  921.61  4696.5  921.02  4731.2  919.76  4839.2  917.67
  4893.8  918.31  4904.6  919.08  4922.7  916.37  4939.3  914.81    4947  915.95
  4973.4  916.12  4976.6  915.65  4983.9  913.25  4989.1  910.02  5010.9  910.02
  5015.2  913.94  5017.9   914.7  5019.2  916.27  5030.3  924.04  5060.7  932.81
  5088.3   938.2  5102.4   942.9  5119.3  946.51  5126.6  949.74  5141.8  947.73
#Mann= 3 ,-1 , 0
  4536.7     .08       0  4983.9     .05       0  5015.2     .08       0
#XS Ineff= 2 , 0
          4801.3  925.34
Permanent Ineff=
       F       F
Bank Sta=4983.9,5015.2
Exp/Cntr=0.3,0.1

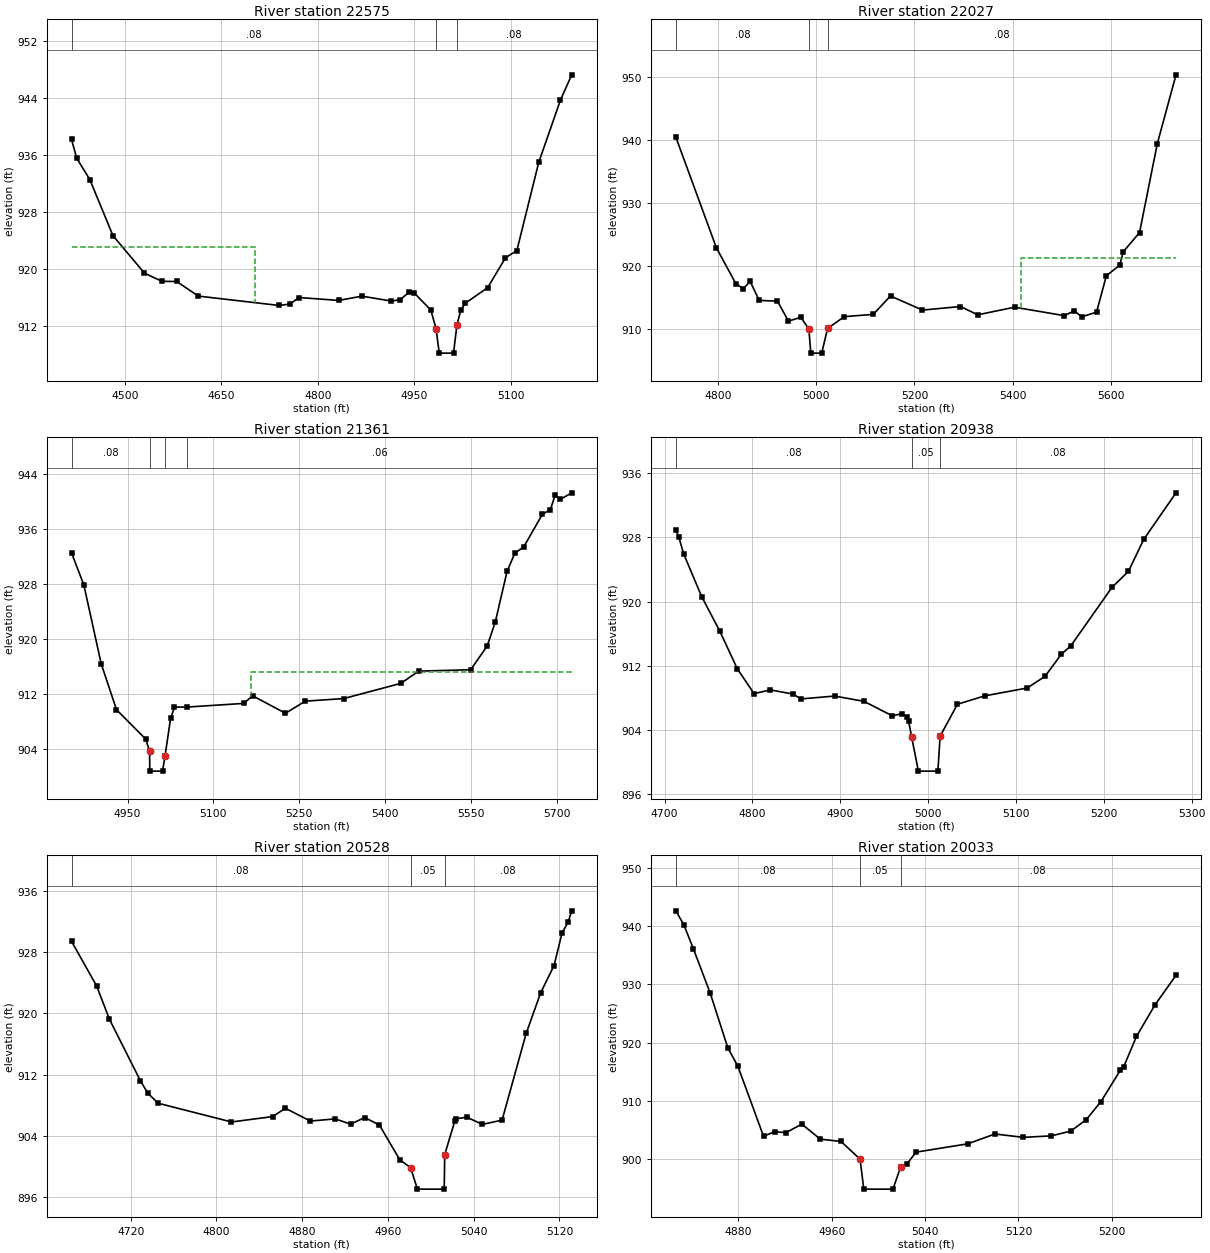
Type RM Length L Ch R = 1 ,22575   ,548,548,548
BEGIN DESCRIPTION:
Hinton Crk - 37.0
END DESCRIPTION:
XS GIS Cut Line= 4
      1200208.95       621867.52      1199994.06       621389.31
      1199924.45       621310.62      1199779.17       621280.35
#Sta/Elev= 30
  4417.2  938.18  4425.2  935.54  4445.6  932.55  4481.6  924.66  4530.6   919.4
  4557.8  918.25  4580.7  918.23  4614.2  916.18  4739.3  914.87  4756.6  915.05
  4770.9  915.98  4832.3  915.57  4868.7  916.17  4914.5  915.48  4928.3  915.68
  4942.3  916.75  4949.9  916.63  4975.8  914.22 4983.91  911.61  4988.9  908.17
  5011.1  908.17  5016.3  912.06  5022.3  914.21  5029.4  915.18  5064.1  917.36
  5091.9  921.56  5109.6  922.58  5143.6  934.96  5177.4  943.72  5194.9  947.25
#Mann= 3 ,-1 , 0
  4417.2     .08       0 4983.91     .05       0  5016.3     .08       0
#XS Ineff= 2 , 0
         4701.65  923.06
Permanent Ineff=
       F       F
Bank Sta=4983.91,5016.3
Exp/Cntr=0.3,0.1

Type RM Length L Ch R = 1 ,22027   ,666,666,666
BEGIN DESCRIPTION:
Hinton Crk - 36.0
END DESCRIPTION:
XS GIS Cut Line= 6
      1200502.53       621704.08      1200454.11       621504.32
      1200454.11       621377.21      1200366.33        621183.5
      1200139.34       620980.72      1199972.88       620953.48
#Sta/Elev= 30
  4714.1  940.52  4796.6  922.97  4836.5  917.23  4851.4  916.46  4865.5   917.6
  4883.8   914.6  4921.1  914.47  4943.4  911.31  4968.7  911.92    4985  910.04
  4988.9  906.23  5011.1  906.23  5023.1  910.15  5057.1  912.02    5116  912.38
  5151.2   915.3  5216.3  913.06  5293.7  913.63  5328.8  912.31  5403.8  913.52
  5504.8  912.18  5525.6  912.94  5540.4  911.99  5570.7  912.73  5590.7  918.51
  5617.8  920.19  5625.2  922.33  5658.2  925.35  5694.4  939.47  5732.5   950.4
#Mann= 3 ,-1 , 0
  4714.1     .08       0    4985     .05       0  5023.1     .08       0
#XS Ineff= 2 , 0
                         5417.02          921.37
Permanent Ineff=
       F       F
Bank Sta=4985,5023.1
Exp/Cntr=0.3,0.1

Type RM Length L Ch R = 1 ,21361   ,423,423,423
BEGIN DESCRIPTION:
Hinton Crk - 35.0
END DESCRIPTION:
XS GIS Cut Line= 6
      1200868.75       620923.22      1200768.87       620868.74
      1200696.23       620862.68      1200181.71        620841.5
      1200084.86        620808.2      1200015.25       620811.23
#Sta/Elev= 30
  4852.2  932.48  4873.7  927.82    4904  916.38  4930.7  909.72  4981.6  905.46
  4988.5   903.7  4988.9   900.8  5011.1   900.8  5015.4  902.94  5025.2  908.45
    5032   910.1  5053.7   910.1    5153  910.63  5168.4  911.74  5225.9   909.2
  5260.4  910.96  5327.4  911.33  5427.4  913.54  5458.3  915.31  5549.4  915.52
  5578.1  918.95  5592.3  922.43    5613  929.83  5626.6  932.44  5642.1  933.36
  5674.7  938.09  5688.6  938.76  5696.7  940.82  5706.1  940.26  5725.9   941.2
#Mann= 4 ,-1 , 0
  4852.2     .08       0  4988.5     .05       0  5015.4     .08       0
  5053.7     .06       0
#XS Ineff= 2 , 0
                         5165.11          915.24
Permanent Ineff=
       F       F
Bank Sta=4988.5,5015.4
Exp/Cntr=0.3,0.1

Type RM Length L Ch R = 1 ,20938   ,410,410,410
BEGIN DESCRIPTION:
Hinton Crk - 34.0
END DESCRIPTION:
XS GIS Cut Line= 5
      1200902.04       620790.04      1200747.69       620593.32
      1200687.15       620541.86      1200617.54       620475.28
      1200490.43       620408.69
#Sta/Elev= 30
  4712.8  928.87  4716.1  928.07  4721.8  925.92  4742.2  920.62  4762.8  916.32
  4782.7  911.63  4801.9  908.51  4820.4  908.98  4846.6  908.45  4854.9  907.85
  4893.6  908.21    4927  907.55  4959.3  905.74  4970.5  906.02  4975.4  905.65
  4977.7  905.12 4981.23  903.13  4988.9  898.85  5011.1  898.85  5013.7  903.21
  5033.4  907.19  5064.6  908.24  5112.7  909.21    5133  910.66  5151.8  913.44
  5162.5  914.48  5209.3  921.76    5228  923.75  5245.5  927.75  5282.2  933.55
#Mann= 3 ,-1 , 0
  4712.8     .08       0 4981.23     .05       0  5013.7     .08       0
Bank Sta=4981.23,5013.7
Exp/Cntr=0.3,0.1

Type RM Length L Ch R = 1 ,20528   ,495,495,495
BEGIN DESCRIPTION:
Hinton Crk - 33.0
END DESCRIPTION:
XS GIS Cut Line= 4
       1200998.9       620814.26      1201065.48       620575.16
      1201122.99       620451.06      1201174.44       620387.51
#Sta/Elev= 30
  4664.8  929.39  4688.2  923.57  4700.1  919.24    4729  911.22  4736.1  909.55
  4745.7  908.27    4814  905.83  4852.4  906.53  4864.3  907.62  4887.5  905.95
  4910.8  906.23  4925.2  905.55  4938.4  906.41  4952.1  905.42  4971.1  900.88
  4981.1  899.88  4987.5  897.07  5012.5  897.07    5013  901.58  5022.5  906.01
  5023.9  906.25  5033.7  906.45  5048.1  905.51  5066.5  906.07    5089  917.39
  5102.6  922.71    5115  926.23  5122.4  930.45  5128.2  931.95  5131.5  933.37
#Mann= 3 ,-1 , 0
  4664.8     .08       0  4981.1     .05       0    5013     .08       0
Bank Sta=4981.1,5013
Exp/Cntr=0.3,0.1

Type RM Length L Ch R = 1 ,20033   ,515,515,515
BEGIN DESCRIPTION:
Hinton Crk - 32.0
END DESCRIPTION:
XS GIS Cut Line= 5
      1201041.27       620929.27      1201171.41        620886.9
      1201277.34       620856.63      1201346.95       620817.28
      1201398.41       620729.51
#Sta/Elev= 30
  4826.4  942.61  4833.3   940.2  4841.4  936.14  4855.9  928.48    4871   919.1
  4879.5  916.01  4901.6  903.96    4911  904.74  4920.8  904.59  4934.4  906.04
  4950.2  903.47    4968  903.07  4984.3  900.04  4987.5   894.9  5012.5   894.9
    5019  898.64  5024.3  899.17  5032.3  901.24  5076.5  902.66  5099.9  904.35
  5124.2  903.78  5148.2  904.03  5164.8  904.85  5177.9  906.75  5190.8  909.91
  5207.4  915.29  5210.3  915.89  5221.2  921.07  5237.1  926.49  5255.1  931.56
#Mann= 3 ,-1 , 0
  4826.4     .08       0  4984.3     .05       0    5019     .08       0
Bank Sta=4984.3,5019
Exp/Cntr=0.3,0.1

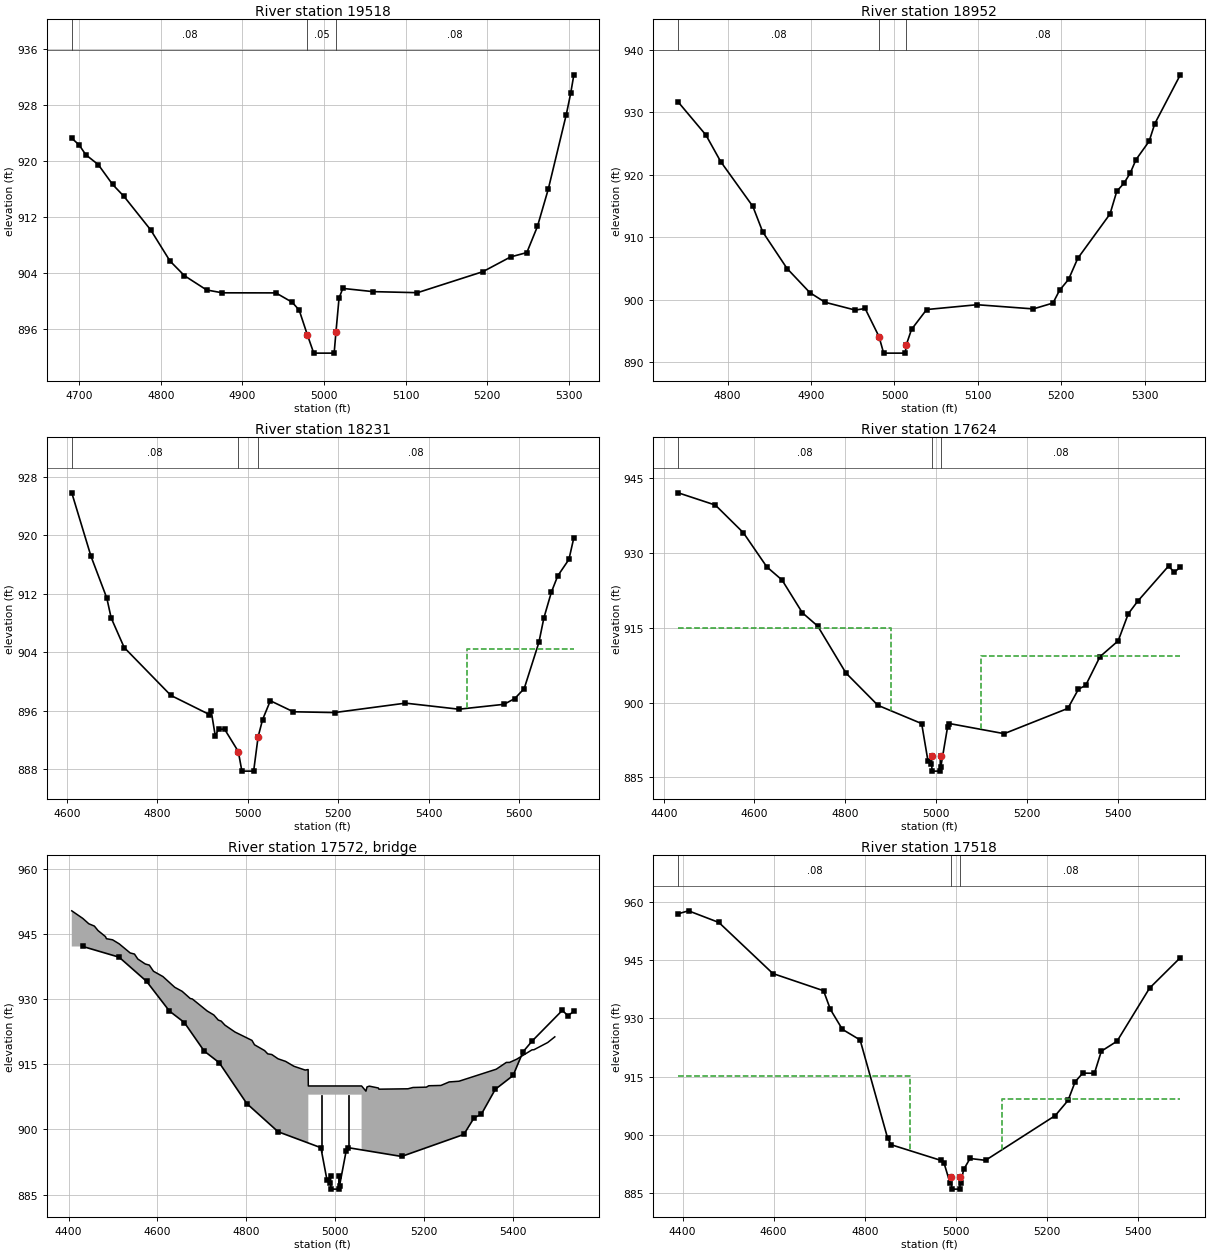
Type RM Length L Ch R = 1 ,19518   ,566,566,566
BEGIN DESCRIPTION:
Hinton Crk - 31.0
END DESCRIPTION:
XS GIS Cut Line= 5
      1201425.65       621368.13      1201589.08       621177.45
      1201610.27        621092.7      1201649.62        620886.9
      1201658.69       620820.31
#Sta/Elev= 30
    4691  923.22    4700  922.26  4708.2  920.86  4723.5  919.45    4741  916.63
    4755  914.92  4787.7  910.14  4811.4   905.7  4829.1  903.61  4856.2  901.58
  4875.5  901.17  4941.1  901.16    4961  899.83  4969.6  898.72  4979.8  895.13
  4987.5  892.57  5012.5  892.57  5014.7  895.56  5018.5  900.42  5023.1   901.8
  5060.2  901.34  5114.6  901.19  5194.8  904.19  5228.7  906.29  5248.6  906.91
  5261.6  910.64  5274.9  915.97  5296.9  926.58  5302.3   929.6  5306.2  932.26
#Mann= 3 ,-1 , 0
    4691     .08       0  4979.8     .05       0  5014.7     .08       0
Bank Sta=4979.8,5014.7
Exp/Cntr=0.3,0.1

Type RM Length L Ch R = 1 ,18952   ,721,721,721
BEGIN DESCRIPTION:
Hinton Crk - 30.0
END DESCRIPTION:
XS GIS Cut Line= 5
      1201813.05       621519.46      1202018.86       621449.84
      1202094.53       621392.34      1202203.48       621331.81
      1202348.76       621253.11
#Sta/Elev= 30
  4740.7  931.64  4773.9  926.36  4791.6  922.11  4830.2  914.93    4842  910.85
  4871.2  904.99  4898.6  901.12  4916.8  899.58  4953.1  898.33  4964.8  898.59
  4981.5  894.08    4987  891.44    5013  891.44    5014  892.69 5020.46  895.24
  5038.6  898.42  5099.1  899.19  5166.5  898.52  5190.1  899.46    5198   901.5
  5208.8  903.25  5219.8  906.61  5258.5  913.72  5266.6  917.35  5275.2  918.64
  5282.8  920.28  5289.7  922.43  5305.4  925.36  5312.2  928.18  5342.8     936
#Mann= 3 ,-1 , 0
  4740.7     .08       0  4981.5     .05       0    5014     .08       0
Bank Sta=4981.5,5014
Exp/Cntr=0.3,0.1

Type RM Length L Ch R = 1 ,18231   ,607,607,607
BEGIN DESCRIPTION:
Hinton Crk - 29.0
END DESCRIPTION:
XS GIS Cut Line= 6
      1202152.03       622245.84      1202345.73       622088.46
      1202430.48       622030.95       1202478.9       621952.26
      1202787.62       621516.43      1202857.23       621404.45
#Sta/Elev= 30
  4610.8  925.81  4653.3  917.13  4688.3  911.41  4697.9   908.7  4726.7  904.65
  4829.9   898.1  4915.2  895.48  4919.2  895.94  4928.1  892.57  4935.5  893.47
  4948.7  893.48  4979.1  890.42    4987  887.74    5013  887.74  5022.9  892.44
  5032.8  894.79  5049.9  897.37  5100.7  895.86  5191.9  895.75  5348.8  897.04
    5467  896.21  5566.7  896.88  5590.5  897.67  5611.3  899.03  5643.8  905.35
  5654.9  908.71  5671.5  912.24  5685.5  914.45  5710.2   916.7  5721.1  919.67
#Mann= 3 ,-1 , 0
  4610.8     .08       0  4979.1     .05       0  5022.9     .08       0
#XS Ineff= 2 , 0
                         5485.85          904.43
Permanent Ineff=
       F       F
Bank Sta=4979.1,5022.9
Exp/Cntr=0.5,0.3

Type RM Length L Ch R = 1 ,17624   ,106,106,106
BEGIN DESCRIPTION:
Hollis Rd SR 1376 - US
END DESCRIPTION:
XS GIS Cut Line= 6
      1202209.54       622642.33      1202533.38       622563.63
      1202727.09       622506.13       1203081.2        622412.3
      1203238.58       622397.17      1203283.98       622406.25
#Sta/Elev= 30
    4432  942.11  4513.8  939.65  4575.6  934.09  4627.2  927.24  4660.7  924.61
  4705.4  918.04  4739.3  915.36  4801.4  905.95  4871.9  899.46  4968.3  895.79
  4982.2  888.27  4988.3  887.67    4990  889.25    4991  886.25    5009  886.25
    5010  889.25  5010.4  887.05  5025.3  895.07  5029.4   895.8  5150.1  893.77
  5290.3  898.84  5313.8  902.72  5329.5  903.44  5361.2  909.23  5401.3  912.41
  5423.5  917.84  5444.2  920.35  5512.1   927.4  5524.8  926.18  5538.1  927.18
#Mann= 3 ,-1 , 0
    4432     .08       0    4990     .05       0    5010     .08       0
#XS Ineff= 2 , 0
       0  4900.5     915  5099.5       0  909.27
Permanent Ineff=
       F       F
Bank Sta=4990,5010
Exp/Cntr=0.5,0.3

Type RM Length L Ch R = 3 ,17572   ,,,
BEGIN DESCRIPTION:
Hollis Rd SR 1376
Structure ID: Hollis Rd SR 1376
Approximate Survey Structure
END DESCRIPTION:
Bridge Culvert--1,0,-1,-1, 0
Deck Dist Width WeirC Skew NumUp NumDn MinLoCord MaxHiCord MaxSubmerge Is_Ogee
39.5,25,3,0, 60, 60, , , , 0, 1,1,,
  4407.2  4432.1  4445.6  4458.1  4466.3  4483.1  4485.3  4499.1  4513.9  4538.8
  4548.4  4555.9  4572.8  4581.9  4591.2  4612.5  4639.1  4655.8  4674.1  4678.9
  4712.1  4727.2  4737.2  4743.8  4752.1  4774.8  4813.1  4818.8  4841.6  4848.6
  4857.7  4871.9  4888.6  4907.7  4932.9  4939.6    4940    4940    5060    5060
  5069.8  5072.2  5077.4  5097.9  5099.1  5164.4  5175.7    5206  5211.3  5238.6
  5257.3  5279.3  5363.3    5386  5393.5  5409.5  5443.8  5448.4  5479.2  5495.2
  950.32  948.57  947.34  946.81  945.78  944.39   943.9  943.65  942.73  940.62
  940.37  939.23  938.08  937.82  936.41  935.19  932.72  931.79  930.13  930.02
  927.27  926.34  925.17  924.93  924.01  922.42  920.49  919.48  918.14  917.39
  917.24  916.25  915.67  914.53  913.66  913.78     910     910     910     910
  908.81  909.78  909.96  909.53  909.26  909.35  909.65  909.73  910.05  910.12
  910.93  911.09  913.86  915.42  915.43  916.17  918.31  918.35     920  921.31
  866.25  866.25  866.25  866.25  866.25  866.25  866.25  866.25  866.25  866.25
  866.25  866.25  866.25  866.25  866.25  866.25  866.25  866.25  866.25  866.25
  866.25  866.25  866.25  866.25  866.25  866.25  866.25  866.25  866.25  866.25
  866.25  866.25  866.25  866.25  866.25  866.25  866.25     908     908  866.25
  866.25  866.25  866.25  866.25  866.25  866.25  866.25  866.25  866.25  866.25
  866.25  866.25  866.25  866.25  866.25  866.25  866.25  866.25  866.25  866.25
  4407.2  4432.1  4445.6  4458.1  4466.3  4483.1  4485.3  4499.1  4513.9  4538.8
  4548.4  4555.9  4572.8  4581.9  4591.2  4612.5  4639.1  4655.8  4674.1  4678.9
  4712.1  4727.2  4737.2  4743.8  4752.1  4774.8  4813.1  4818.8  4841.6  4848.6
  4857.7  4871.9  4888.6  4907.7  4932.9  4939.6    4940    4940    5060    5060
  5069.8  5072.2  5077.4  5097.9  5099.1  5164.4  5175.7    5206  5211.3  5238.6
  5257.3  5279.3  5363.3    5386  5393.5  5409.5  5443.8  5448.4  5479.2  5495.2
  950.32  948.57  947.34  946.81  945.78  944.39   943.9  943.65  942.73  940.62
  940.37  939.23  938.08  937.82  936.41  935.19  932.72  931.79  930.13  930.02
  927.27  926.34  925.17  924.93  924.01  922.42  920.49  919.48  918.14  917.39
  917.24  916.25  915.67  914.53  913.66  913.78     910     910     910     910
  908.81  909.78  909.96  909.53  909.26  909.35  909.65  909.73  910.05  910.12
  910.93  911.09  913.86  915.42  915.43  916.17  918.31  918.35     920  921.31
  866.25  866.25  866.25  866.25  866.25  866.25  866.25  866.25  866.25  866.25
  866.25  866.25  866.25  866.25  866.25  866.25  866.25  866.25  866.25  866.25
  866.25  866.25  866.25  866.25  866.25  866.25  866.25  866.25  866.25  866.25
  866.25  866.25  866.25  866.25  866.25  866.25  866.25     908     908  866.25
  866.25  866.25  866.25  866.25  866.25  866.25  866.25  866.25  866.25  866.25
  866.25  866.25  866.25  866.25  866.25  866.25  866.25  866.25  866.25  866.25
Pier Skew, UpSta & Num, DnSta & Num=  ,4970, 2 ,4970, 2 , 0 , 0 , 0 ,0,0
     1.5     1.5
  894.81     908
     1.5     1.5
  893.16     908
Pier Skew, UpSta & Num, DnSta & Num=  ,5030, 2 ,5030, 2 , 0 , 0 , 0 ,0,0
     1.5     1.5
  895.78     908
     1.5     1.5
  893.73     908
Abutment Skew #Up #Dn= , 2 , 2
    4940    4945
     908   896.5
    4940    4945
     908  894.22
Abutment Skew #Up #Dn= , 2 , 2
    5055    5060
  894.96     908
    5055    5060
  894.01     908
BR Coef= 1 , 1 , 0 ,1.25, 0 ,,,0.8,0,2,0,
WSPro=,,,, 1 ,,,, 0 ,,,, 0 ,,,,-1 ,-1 ,-1 , 0 , 0 , 0 , 0 , 0
BC Design=,, 0 ,, 0 ,,,,,,
BC HTab HWMax=942.28

Type RM Length L Ch R = 1 ,17518   ,757,757,757
BEGIN DESCRIPTION:
Hollis Rd SR 1376 - DS
END DESCRIPTION:
XS GIS Cut Line= 6
      1202212.56       622745.23       1202557.6       622669.57
      1202721.03       622618.11      1203023.69       622527.32
      1203181.08        622503.1      1203283.98       622506.13
#Sta/Elev= 30
  4390.4  956.93    4413  957.68  4479.7  954.68  4598.2  941.53  4709.6   937.1
  4724.6  932.29  4750.9  927.16  4789.9  924.42  4850.2  899.17    4858  897.44
  4967.9  893.38  4974.2  892.73  4987.5  887.53    4990     889    4991     886
    5009     886    5010     889  5010.7  887.49  5017.4  891.06  5031.3  893.89
  5065.4  893.42  5218.6  904.95  5246.6  908.85  5262.3  913.67  5278.9  915.88
  5304.6  915.84  5319.7  921.53  5354.3  924.11  5425.6  937.76  5493.2  945.61
#Mann= 3 ,-1 , 0
  4390.4     .08       0    4990     .05       0    5010     .08       0
#XS Ineff= 2 , 0
       0  4898.5  915.09  5101.5       0  909.31
Permanent Ineff=
       F       F
Bank Sta=4990,5010
Exp/Cntr=0.5,0.3

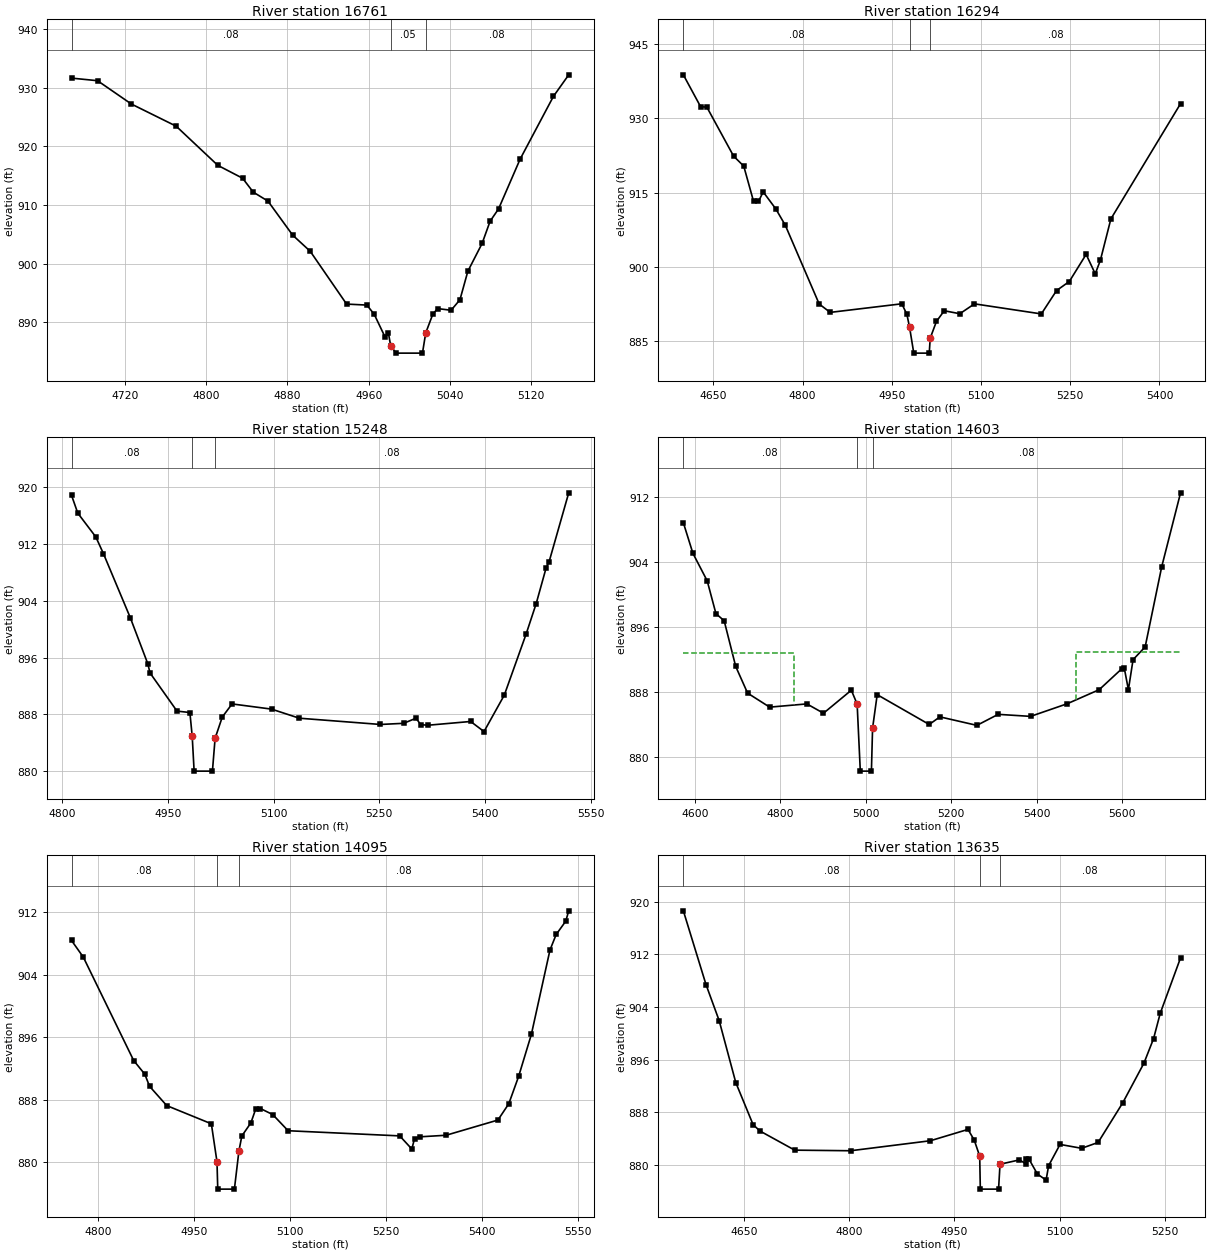
Type RM Length L Ch R = 1 ,16761   ,467,467,467
BEGIN DESCRIPTION:
Hinton Crk - 28.0
END DESCRIPTION:
XS GIS Cut Line= 4
      1202669.58       623238.57      1202938.95       623308.18
      1203038.83        623299.1      1203144.76       623265.81
#Sta/Elev= 30
  4667.5   931.6  4693.1  931.16  4726.4  927.19  4770.5  923.42  4811.5  916.75
  4835.9  914.56  4846.4  912.19  4860.9  910.66  4885.2  904.87  4902.5  902.12
  4938.3  893.13  4958.3  892.96  4965.5  891.39  4976.1  887.55 4979.54  888.13
  4981.7  886.05    4987  884.78    5013  884.78  5016.2  888.21  5023.3  891.46
    5028  892.36  5041.2  892.08  5049.9  893.87  5057.7  898.73  5071.7  903.45
  5079.6  907.24  5087.9  909.33  5109.1  917.79    5142  928.51    5157  932.16
#Mann= 3 ,-1 , 0
  4667.5     .08       0  4981.7     .05       0  5016.2     .08       0
Bank Sta=4981.7,5016.2
Exp/Cntr=0.3,0.1

Type RM Length L Ch R = 1 ,16294   ,1046,1046,1046
BEGIN DESCRIPTION:
Hinton Crk - 27.0
END DESCRIPTION:
XS GIS Cut Line= 6
      1202581.81       623813.62      1202935.92        623777.3
      1203023.69       623722.82      1203153.84       623641.11
      1203205.29       623604.79      1203271.87       623459.51
#Sta/Elev= 30
  4599.7  938.72  4628.7   932.3  4639.2  932.21  4684.2  922.33  4701.2  920.33
  4717.7  913.22    4726  913.21  4733.9  915.13  4755.1   911.7    4771  908.42
    4828  892.54  4846.5  890.85  4966.9  892.58  4975.4  890.46  4979.9  887.87
    4987  882.64    5013  882.64  5014.6  885.65  5025.1  889.03  5038.2  891.18
  5064.4  890.58    5089  892.57  5201.4  890.54    5227  895.25  5248.4  897.07
  5276.7  902.54    5292  898.62  5300.6  901.34  5318.3  909.69  5435.4  932.91
#Mann= 3 ,-1 , 0
  4599.7     .08       0  4979.9     .05       0  5014.6     .08       0
Bank Sta=4979.9,5014.6
Exp/Cntr=0.3,0.1

Type RM Length L Ch R = 1 ,15248   ,645,645,645
BEGIN DESCRIPTION:
Hinton Crk - 26.0
END DESCRIPTION:
XS GIS Cut Line= 5
      1203725.87       624506.71      1203780.34       624361.44
      1203813.64       624282.75      1203895.36       623961.93
       1203877.2       623828.75
#Sta/Elev= 30
  4812.9  918.85  4821.8  916.34  4847.4  912.99  4858.3  910.62  4896.4  901.61
  4921.2  895.14  4924.4  893.84  4962.7  888.47    4981  888.27 4984.31   884.9
    4987  880.02    5013  880.02  5016.8  884.64    5027  887.64  5040.9  889.48
    5097  888.75  5136.4  887.47  5251.6  886.59  5284.5  886.75  5302.1  887.47
  5308.9  886.56    5319  886.48  5379.7  887.01  5398.7  885.59  5427.5  890.72
  5458.6  899.35  5472.8  903.61    5487  908.67  5491.1  909.49    5519   919.2
#Mann= 3 ,-1 , 0
  4812.9     .08       0 4984.31     .05       0  5016.8     .08       0
Bank Sta=4984.31,5016.8
Exp/Cntr=0.3,0.1

Type RM Length L Ch R = 1 ,14603   ,508,508,508
BEGIN DESCRIPTION:
Hinton Crk - 25.0
END DESCRIPTION:
XS GIS Cut Line= 5
      1204095.11       624797.27      1204379.61       624549.09
      1204406.85       624467.37      1204670.17       623961.93
      1204797.28       623937.71
#Sta/Elev= 30
  4573.1  908.88  4595.4  905.11  4628.9   901.7  4649.3  897.66  4668.6  896.77
  4695.6  891.13  4723.4  887.84    4775  886.11    4862  886.51  4900.9  885.36
    4966   888.2  4979.6  886.49    4987  878.21    5013  878.21  5015.7  883.51
  5026.5  887.65  5148.2  883.97  5173.2  884.91  5259.7  883.86  5309.5  885.22
  5385.3  884.97    5471  886.53  5545.9  888.27  5598.1  890.82  5604.6   890.9
  5614.1  888.26    5625  891.97  5653.3  893.55    5692  903.44  5736.1  912.57
#Mann= 3 ,-1 , 0
  4573.1     .08       0  4979.6     .05       0  5015.7     .08       0
#XS Ineff= 2 , 0
         4833.06  892.74 5491.27           892.9
Permanent Ineff=
       F       F
Bank Sta=4979.6,5015.7
Exp/Cntr=0.3,0.1

Type RM Length L Ch R = 1 ,14095   ,460,460,460
BEGIN DESCRIPTION:
Hinton Crk - 24.0
END DESCRIPTION:
XS GIS Cut Line= 5
      1204588.45       625115.06      1204652.01       624921.36
      1204706.48       624854.77      1205006.12       624627.78
      1205069.68       624536.98
#Sta/Elev= 30
  4758.6   908.4    4777  906.27  4855.7  893.02    4873  891.28  4880.5  889.72
  4907.3  887.25    4977  884.92  4985.8  880.06    4987  876.55    5013  876.55
    5020   881.4  5024.6  883.36  5038.7  885.03  5046.2  886.79  5053.7  886.87
  5072.9   886.1  5096.9  884.03  5271.2  883.37  5290.1  881.69  5294.4  883.02
  5302.6  883.25  5343.6  883.45  5424.6   885.4  5441.6  887.49  5456.9  890.98
  5476.8  896.36  5505.9  907.18  5515.6  909.17  5530.5  910.87  5535.2   912.2
#Mann= 3 ,-1 , 0
  4758.6     .08       0  4985.8     .05       0    5020     .08       0
Bank Sta=4985.8,5020
Exp/Cntr=0.3,0.1

Type RM Length L Ch R = 1 ,13635   ,534,534,534
BEGIN DESCRIPTION:
Hinton Crk - 23.0
END DESCRIPTION:
XS GIS Cut Line= 6
      1204745.83       625438.91      1204875.97       625326.92
      1204994.01       625130.19      1205033.36       625024.26
      1205090.86       624984.92       1205208.9       624942.54
#Sta/Elev= 30
  4563.4  918.61  4595.7  907.41  4614.5  901.93  4638.2  892.52  4662.9  886.13
  4672.8  885.16  4722.3  882.26    4802  882.17  4915.8  883.69  4969.4  885.41
  4978.3  883.79  4986.1  881.35    4987  876.34    5013  876.34  5015.1  880.12
  5042.7  880.78    5052  880.19  5052.4  880.93  5056.4   880.9  5068.4  878.63
  5080.8  877.71  5084.4   879.9  5100.7  883.13  5131.5  882.54    5155  883.43
  5190.2  889.46  5220.4  895.48  5234.1   899.2  5243.6  903.04  5272.6  911.47
#Mann= 3 ,-1 , 0
  4563.4     .08       0  4986.1     .05       0  5015.1     .08       0
Bank Sta=4986.1,5015.1
Exp/Cntr=0.5,0.3