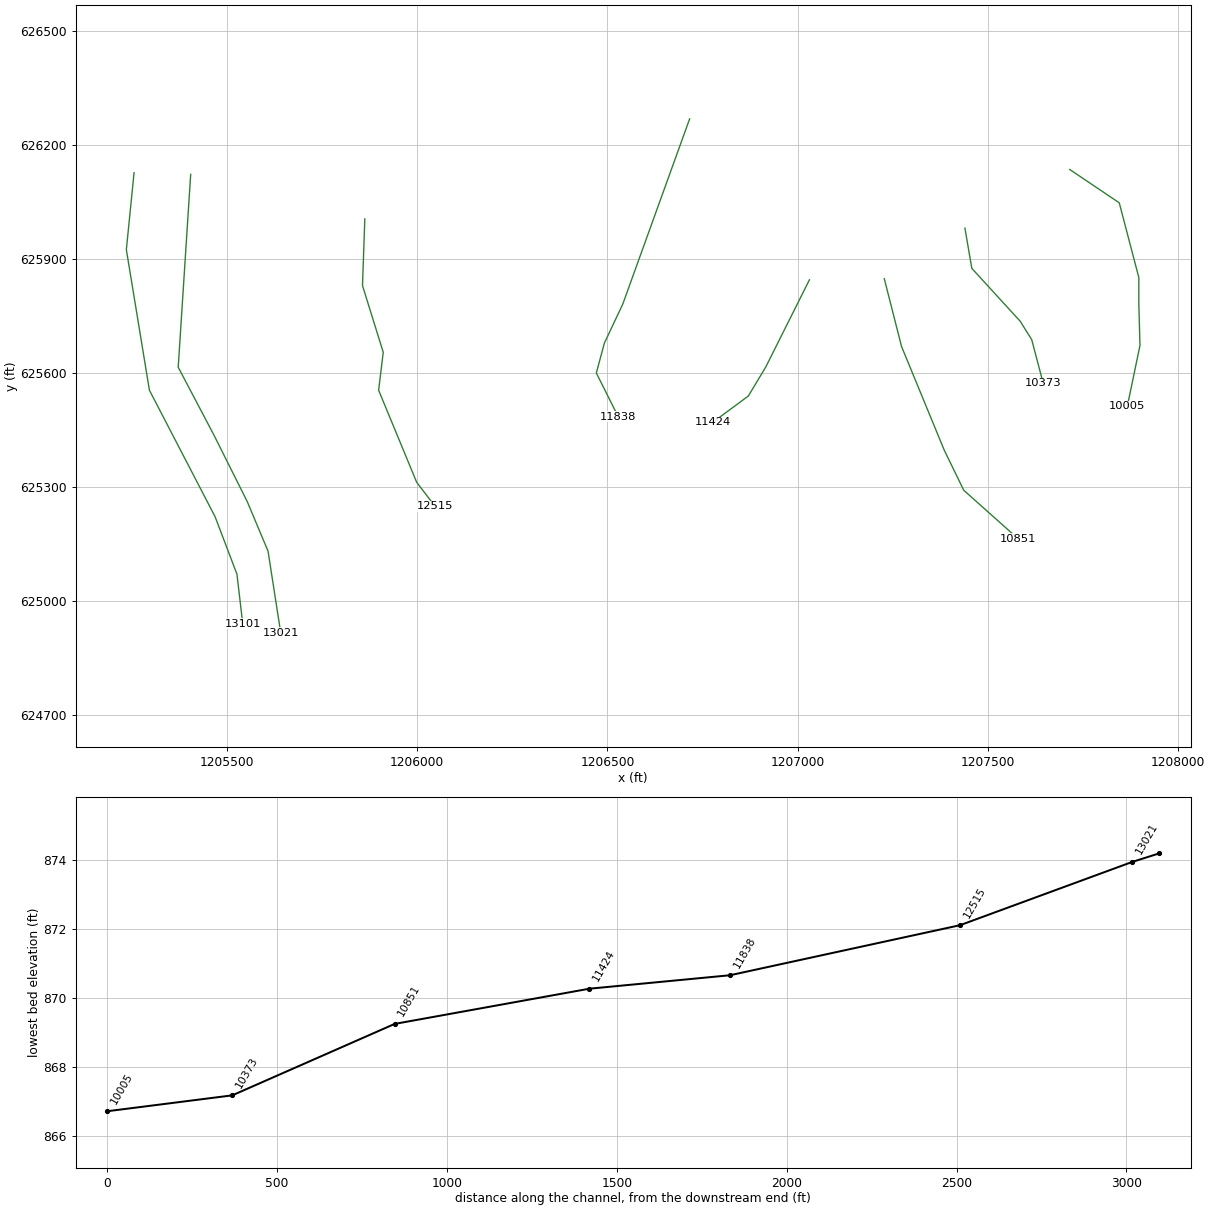
HEC-RAS study lds_hinton_crk.prj: Hinton Creek Limited Detail Study

--- lds_hinton_crk.g01 (geometry) --- (continued)

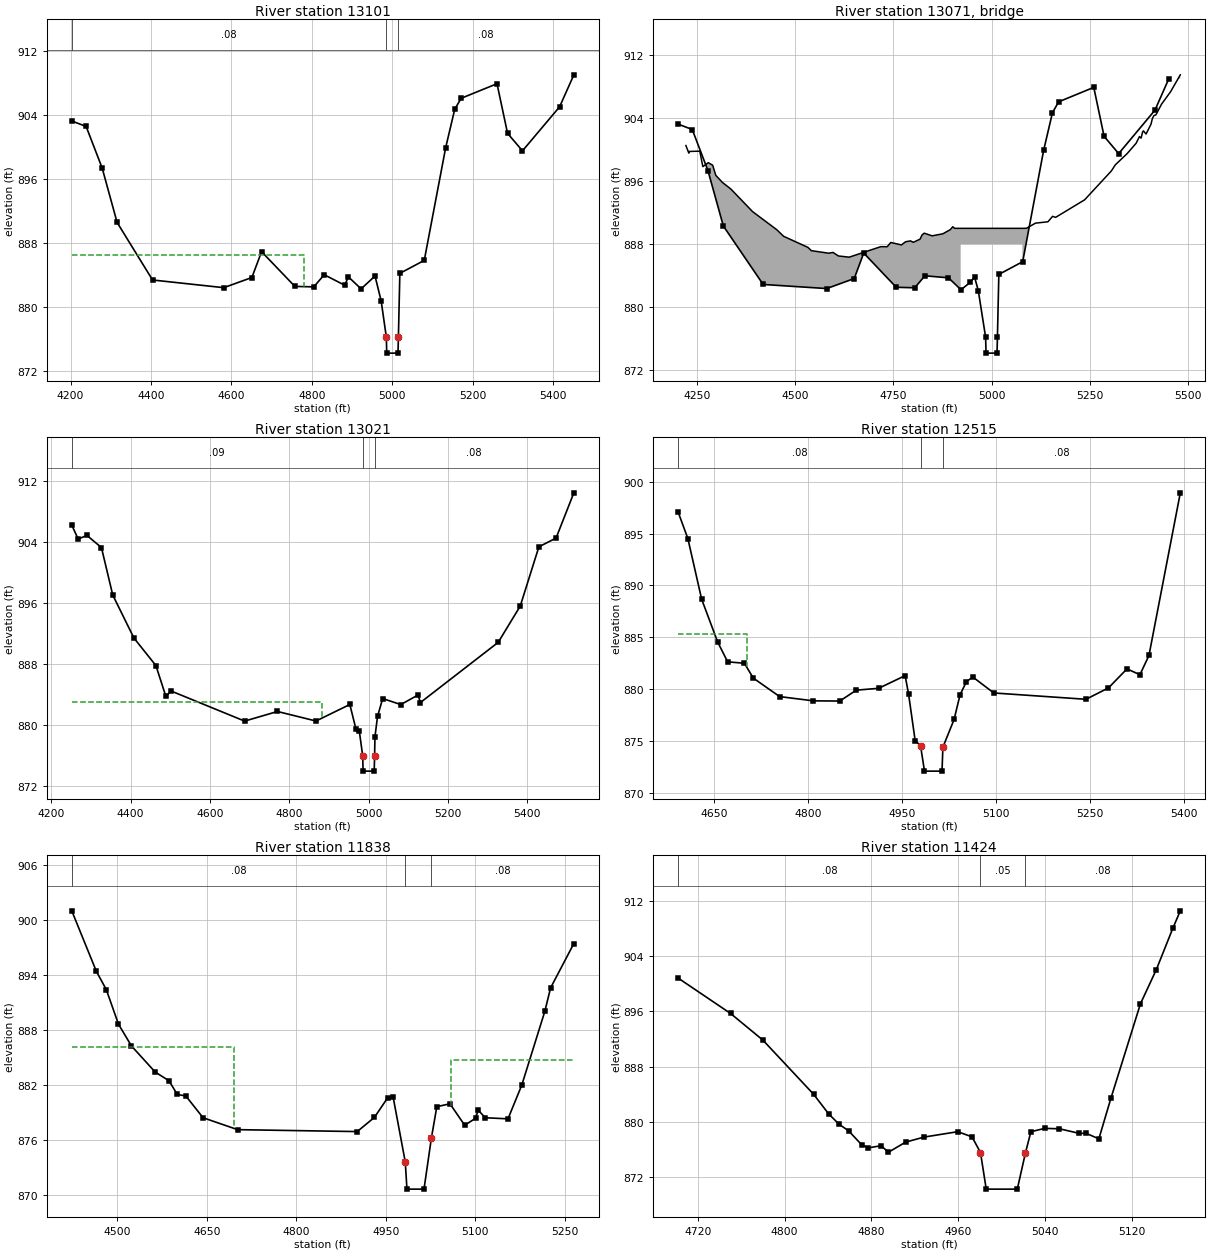
Type RM Length L Ch R = 1 ,13101   ,80,80,80
BEGIN DESCRIPTION:
Five Points Rd SR 1373 - US
END DESCRIPTION:
XS GIS Cut Line= 6
      1205256.29       626126.43      1205236.04       625923.93
      1205296.67       625553.92      1205469.19       625220.99
      1205526.69       625069.66      1205541.83       624939.52
#Sta/Elev= 30
  4203.1   903.2  4238.8  902.52  4278.7  897.31  4315.8  890.52  4403.9  883.33
  4580.8  882.37  4650.8  883.64  4674.9  886.87  4757.6  882.53  4804.7  882.47
  4830.6  883.99  4881.7  882.67  4890.5  883.73  4922.3  882.22  4956.9  883.83
  4972.2   880.7    4985  876.19    4986  874.19    5014  874.19    5015  876.19
  5018.6  884.16  5079.3  885.78  5132.5  899.87  5154.9  904.64  5170.7  906.03
  5260.1  907.86  5286.3  901.66  5323.4  899.47  5415.8  904.98  5451.1  908.97
#Mann= 3 ,-1 , 0
  4203.1     .08       0    4985     .05       0    5015     .08       0
#XS Ineff= 2 , 0
       0    4780   886.5               0
Permanent Ineff=
       F       F
Bank Sta=4985,5015
Exp/Cntr=0.5,0.3

Type RM Length L Ch R = 3 ,13071   ,,,
BEGIN DESCRIPTION:
Five Points Rd SR 1373
Structure ID: Five Points Rd SR 1373
Approximate Survey Structure
END DESCRIPTION:
Bridge Culvert--1,0,-1,-1, 0
Deck Dist Width WeirC Skew NumUp NumDn MinLoCord MaxHiCord MaxSubmerge Is_Ogee
18,24,3,0, 60, 60, , , , 0, 1,1,,
  4222.6    4230  4230.4  4257.9  4265.7  4279.4  4290.7  4298.7  4315.4    4337
  4392.2  4453.4  4471.2  4532.9  4541.8  4585.8  4596.7  4610.5    4638  4718.3
  4734.5  4743.8  4770.8  4781.4    4794    4801  4818.2  4823.3  4828.8  4848.8
  4876.2  4895.3  4901.4  4906.3  4921.5  4921.5  5078.5  5078.5    5089  5111.8
  5143.5  5155.3    5163  5236.7  5304.8  5314.9    5345  5367.8  5376.3  5380.5
  5384.2  5386.3  5393.1  5405.7  5409.1  5412.9  5418.2  5432.5  5455.2  5480.2
  900.49  899.53  899.74  899.78  897.82  898.32     898  896.71  895.82  894.98
  892.12  889.84  888.99  887.59  887.17  886.85  886.95   886.5  886.35  887.68
  887.67  888.21   887.9   888.3  888.41  888.23  888.63  889.16  889.39  889.05
  889.31  889.84   890.2     890     890     890     890     890  890.01  890.66
  890.83  891.52  891.39  893.61  897.27  898.05  899.47  900.78  901.63  901.43
   902.2  902.35  901.95   903.2  903.91  904.27  904.39  905.74  907.29  909.45
  854.19  854.19  854.19  854.19  854.19  854.19  854.19  854.19  854.19  854.19
  854.19  854.19  854.19  854.19  854.19  854.19  854.19  854.19  854.19  854.19
  854.19  854.19  854.19  854.19  854.19  854.19  854.19  854.19  854.19  854.19
  854.19  854.19  854.19  854.19  854.19     888     888  854.19  854.19  854.19
  854.19  854.19  854.19  854.19  854.19  854.19  854.19  854.19  854.19  854.19
  854.19  854.19  854.19  854.19  854.19  854.19  854.19  854.19  854.19  854.19
  4222.6    4230  4230.4  4257.9  4265.7  4279.4  4290.7  4298.7  4315.4    4337
  4392.2  4453.4  4471.2  4532.9  4541.8  4585.8  4596.7  4610.5    4638  4718.3
  4734.5  4743.8  4770.8  4781.4    4794    4801  4818.2  4823.3  4828.8  4848.8
  4876.2  4895.3  4901.4  4906.3  4921.5  4921.5  5078.5  5078.5    5089  5111.8
  5143.5  5155.3    5163  5236.7  5304.8  5314.9    5345  5367.8  5376.3  5380.5
  5384.2  5386.3  5393.1  5405.7  5409.1  5412.9  5418.2  5432.5  5455.2  5480.2
  900.49  899.53  899.74  899.78  897.82  898.32     898  896.71  895.82  894.98
  892.12  889.84  888.99  887.59  887.17  886.85  886.95   886.5  886.35  887.68
  887.67  888.21   887.9   888.3  888.41  888.23  888.63  889.16  889.39  889.05
  889.31  889.84   890.2     890     890     890     890     890  890.01  890.66
  890.83  891.52  891.39  893.61  897.27  898.05  899.47  900.78  901.63  901.43
   902.2  902.35  901.95   903.2  903.91  904.27  904.39  905.74  907.29  909.45
  854.19  854.19  854.19  854.19  854.19  854.19  854.19  854.19  854.19  854.19
  854.19  854.19  854.19  854.19  854.19  854.19  854.19  854.19  854.19  854.19
  854.19  854.19  854.19  854.19  854.19  854.19  854.19  854.19  854.19  854.19
  854.19  854.19  854.19  854.19  854.19     888     888  854.19  854.19  854.19
  854.19  854.19  854.19  854.19  854.19  854.19  854.19  854.19  854.19  854.19
  854.19  854.19  854.19  854.19  854.19  854.19  854.19  854.19  854.19  854.19
Abutment Skew #Up #Dn= , 2 , 2
  4921.5    4925
     888  882.44
  4921.5    4925
     888  882.03
Abutment Skew #Up #Dn= , 2 , 2
    5075  5078.5
  885.73     888
    5075  5078.5
  883.11     888
BR Coef= 1 , 1 , 0 ,1.25, 0 ,,,0.8,0,2,0,
WSPro=,,,, 1 ,,,, 0 ,,,, 0 ,,,,-1 ,-1 ,-1 , 0 , 0 , 0 , 0 , 0
BR U #Sta/Elev= 30
  4203.1   903.2  4238.8  902.52  4278.7  897.31  4317.8   890.3  4419.1  882.89
  4580.8  882.37  4650.8  883.64  4674.9  886.87  4757.6  882.53  4804.7  882.47
  4830.6  883.99  4890.5  883.73  4922.3  882.22  4945.4  883.14  4956.9  883.83
  4966.4  882.09    4985  876.19    4986  874.19    5014  874.19    5015  876.19
  5018.6  884.16  5079.3  885.78  5132.5  899.87  5154.9  904.64  5170.7  906.03
  5260.1  907.86  5286.3  901.66  5323.4  899.47  5415.8  904.98  5451.1  908.97
BR U #Mann= 4
  4203.1     .08  4945.4     .05    5015     .08  5079.3     .08
BC Design=,, 0 ,, 0 ,,,,,,
BC HTab HWMax=908.97

Type RM Length L Ch R = 1 ,13021   ,506,506,506
BEGIN DESCRIPTION:
Five Points Rd SR 1373 - DS
END DESCRIPTION:
XS GIS Cut Line= 6
       1205405.1       626122.16      1205372.34       625614.45
      1205466.16       625435.88      1205553.93       625260.34
      1205608.41       625130.19      1205641.71       624915.31
#Sta/Elev= 30
  4251.9  906.24  4268.1  904.41  4290.1  904.89  4326.7  903.29  4355.1  897.07
  4408.5  891.42    4464  887.79    4489  883.75  4502.1  884.46  4687.5  880.51
  4770.2  881.77  4867.4  880.52  4952.6  882.69  4968.1  879.44  4976.5   879.2
    4985  875.94    4986  873.94    5014  873.94    5015  875.94  5015.9  878.44
  5022.4  881.13  5035.4  883.47    5081  882.68  5124.3  883.93  5130.6  882.95
  5326.5  890.85    5382  895.61    5429  903.39  5472.3  904.54  5517.1  910.48
#Mann= 3 ,-1 , 0
  4251.9     .09       0    4985    .052       0    5015     .08       0
#XS Ineff= 2 , 0
       0  4883.5     883               0
Permanent Ineff=
       F       F
Bank Sta=4985,5015
Exp/Cntr=0.5,0.3

Type RM Length L Ch R = 1 ,12515   ,677,677,677
BEGIN DESCRIPTION:
Hinton Crk - 22.0
END DESCRIPTION:
XS GIS Cut Line= 6
      1205862.65       626004.88      1205856.59       625829.34
      1205911.07        625653.8      1205898.97       625553.92
      1205998.84       625311.79      1206047.27       625248.23
#Sta/Elev= 30
  4592.7  897.04  4608.1  894.51  4630.1  888.67  4655.6  884.56  4671.6  882.64
  4698.4   882.5  4712.6  881.07  4754.7  879.29  4808.7  878.88  4850.7  878.86
  4877.1  879.91  4912.9  880.09  4955.1  881.31  4960.6  879.53  4971.1  875.05
  4979.7  874.56    4986  872.11    5014  872.11  5015.4  874.41  5033.3  877.09
  5042.8  879.46  5052.8  880.71  5063.1  881.18  5096.7  879.64  5243.9  879.03
  5279.9  880.13  5309.4  881.96  5330.1   881.4  5344.5  883.25  5394.6  898.92
#Mann= 3 ,-1 , 0
  4592.7     .08       0  4979.7     .05       0  5015.4     .08       0
#XS Ineff= 2 , 0
         4702.23  885.29
Permanent Ineff=
       F       F
Bank Sta=4979.7,5015.4
Exp/Cntr=0.3,0.1

Type RM Length L Ch R = 1 ,11838   ,414,414,414
BEGIN DESCRIPTION:
Hinton Crk - 21.0
END DESCRIPTION:
XS GIS Cut Line= 5
      1206716.15        626268.2      1206540.61       625780.91
      1206492.18       625678.01      1206470.99       625599.32
       1206528.5       625484.31
#Sta/Elev= 30
  4423.8  901.03    4465  894.43  4481.7  892.43  4502.1  888.66  4523.9  886.28
  4563.6  883.44  4586.7  882.49  4600.7  880.99    4615  880.83  4643.9  878.45
  4701.9  877.15  4902.3  876.94  4931.2  878.49  4953.2  880.61  4962.6  880.69
  4982.9  873.62  4985.7  870.66  5014.3  870.66  5026.7  876.24  5035.8  879.66
  5057.9  879.97  5082.5  877.63  5100.7  878.39  5105.1  879.28    5117  878.45
  5155.1  878.33  5178.2  882.01  5216.8  890.05  5226.5  892.62  5265.5  897.46
#Mann= 3 ,-1 , 0
  4423.8     .08       0  4982.9     .05       0  5026.7     .08       0
#XS Ineff= 2 , 0
         4695.99  886.14 5060.24          884.73
Permanent Ineff=
       F       F
Bank Sta=4982.9,5026.7
Exp/Cntr=0.3,0.1

Type RM Length L Ch R = 1 ,11424   ,573,573,573
BEGIN DESCRIPTION:
Hinton Crk - 20.0
END DESCRIPTION:
XS GIS Cut Line= 4
      1207030.92       625844.47      1206915.91       625614.45
      1206870.51       625538.79      1206776.68       625469.17
#Sta/Elev= 30
  4702.1  900.83  4750.3  895.71    4780  891.86  4826.8     884  4840.5  881.19
  4850.1  879.68    4859  878.71  4870.9  876.71  4877.1  876.24  4888.8  876.56
  4895.7  875.62  4911.5  877.08  4928.5  877.81  4959.5  878.59  4972.6  877.84
  4980.4  875.57  4985.7  870.27  5014.3  870.27 5021.75  875.48  5026.8  878.58
  5039.5  879.07  5053.1  879.01    5071  878.36  5077.8  878.35  5089.4  877.55
  5100.5  883.43  5127.7  897.12  5142.3  902.06  5157.6  908.09  5164.4  910.58
#Mann= 3 ,-1 , 0
  4702.1     .08       0  4980.4     .05       0 5021.75     .08       0
Bank Sta=4980.4,5021.75
Exp/Cntr=0.3,0.1

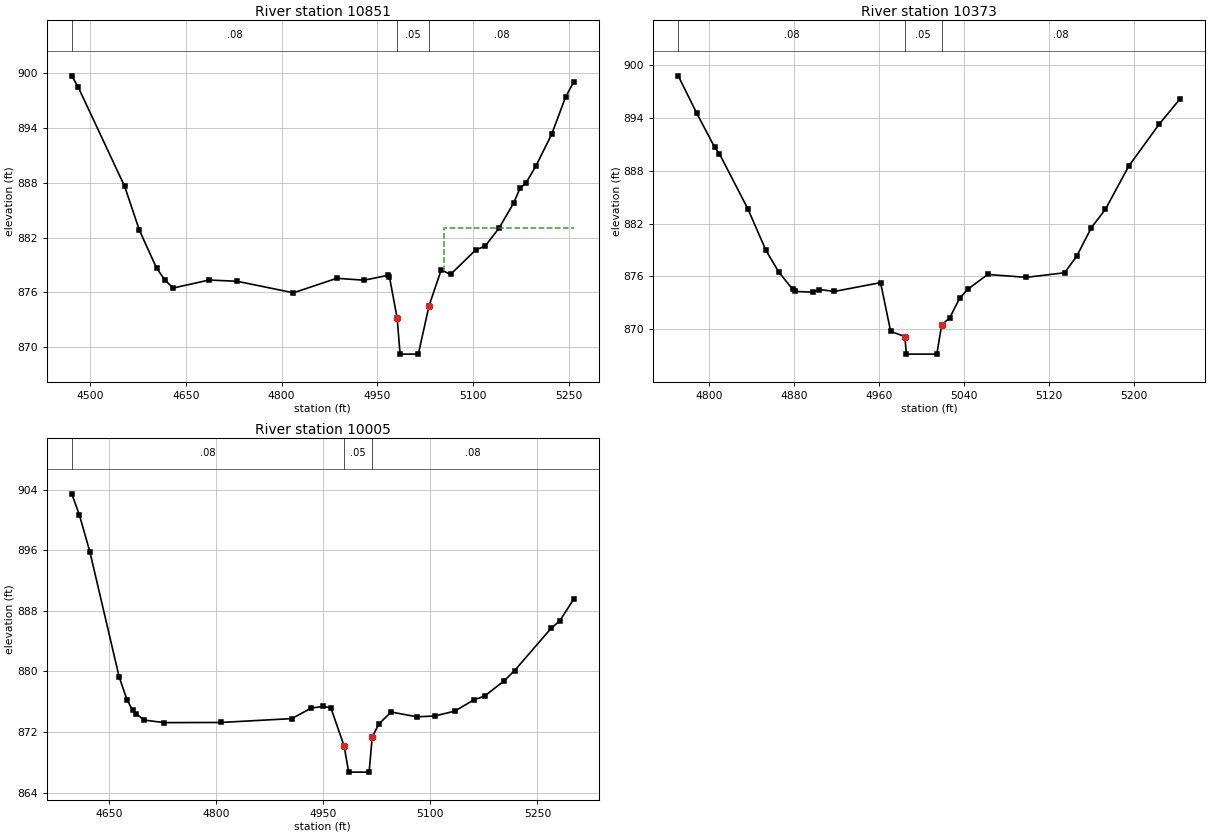
Type RM Length L Ch R = 1 ,10851   ,478,478,478
BEGIN DESCRIPTION:
Hinton Crk - 19.0
END DESCRIPTION:
XS GIS Cut Line= 5
      1207227.65        625847.5      1207273.04       625668.93
      1207385.03       625396.54      1207436.48        625290.6
      1207578.73       625163.49
#Sta/Elev= 30
  4470.9  899.71    4481  898.47  4553.9   887.6  4576.9  882.81  4603.8  878.68
  4617.2  877.33  4630.2  876.49  4686.2  877.36  4730.5  877.22  4818.5  875.96
  4886.4  877.55  4929.4  877.34    4967  877.88    4969  877.73  4981.2  873.16
  4985.7  869.25  5014.3  869.25  5031.2  874.56  5050.2  878.46  5064.9  877.98
  5104.9  880.69  5118.7  881.04  5140.6  883.01  5163.6  885.76    5174  887.44
  5182.7  887.93    5199  889.88  5223.3  893.29  5245.2  897.38  5258.2  899.07
#Mann= 3 ,-1 , 0
  4470.9     .08       0  4981.2     .05       0  5031.2     .08       0
#XS Ineff= 2 , 0
                         5054.85          883.06
Permanent Ineff=
       F       F
Bank Sta=4981.2,5031.2
Exp/Cntr=0.3,0.1

Type RM Length L Ch R = 1 ,10373   ,368,368,368
BEGIN DESCRIPTION:
Hinton Crk - 18.0
END DESCRIPTION:
XS GIS Cut Line= 5
      1207439.51       625980.67      1207457.67       625874.74
      1207584.79       625735.52      1207615.05       625687.09
      1207645.32       625572.08
#Sta/Elev= 30
  4771.2  898.79  4788.6  894.54  4805.5  890.66  4809.8  889.96  4836.7  883.67
  4853.6  878.98  4865.5  876.54  4878.7  874.55  4880.7   874.3  4897.8  874.22
    4904  874.52    4918   874.3  4961.4   875.3  4970.9  869.76 4984.21  869.18
  4985.7  867.18  5014.3  867.18  5018.9  870.53  5026.3  871.27  5035.7  873.52
  5043.6  874.57  5062.2  876.23  5098.3   875.9  5134.4  876.42  5145.8   878.3
  5159.6  881.55  5172.8  883.63  5194.8  888.55  5223.3  893.29  5243.2  896.21
#Mann= 3 ,-1 , 0
  4771.2     .08       0 4984.21     .05       0  5018.9     .08       0
Bank Sta=4984.21,5018.9
Exp/Cntr=0.3,0.1

Type RM Length L Ch R = 1 ,10005   ,521,521,521
BEGIN DESCRIPTION:
Hinton Crk - 17.0
END DESCRIPTION:
XS GIS Cut Line= 6
      1207714.93       626135.03      1207845.07       626047.26
      1207896.53       625850.53      1207896.53       625780.91
      1207899.55       625671.96      1207866.26       625511.55
#Sta/Elev= 30
  4598.1  903.43  4608.8  900.63  4623.5  895.76  4664.4  879.29  4675.4  876.26
  4683.3  874.88  4688.3  874.38  4699.9  873.58  4727.6  873.25  4806.4  873.27
  4906.1  873.78  4933.1  875.16  4949.1  875.38  4960.7  875.23  4979.3  870.17
  4985.7  866.72  5014.3  866.72  5018.7  871.35  5027.7  873.03    5045  874.65
  5081.2  874.02  5106.1  874.12  5134.3  874.77  5160.9  876.25  5176.1  876.76
  5203.4  878.77  5217.9  880.11    5269  885.68    5281  886.66  5300.9  889.55
#Mann= 3 ,-1 , 0
  4598.1     .08       0  4979.3     .05       0  5018.7     .08       0
Bank Sta=4979.3,5018.7
Exp/Cntr=0.3,0.1