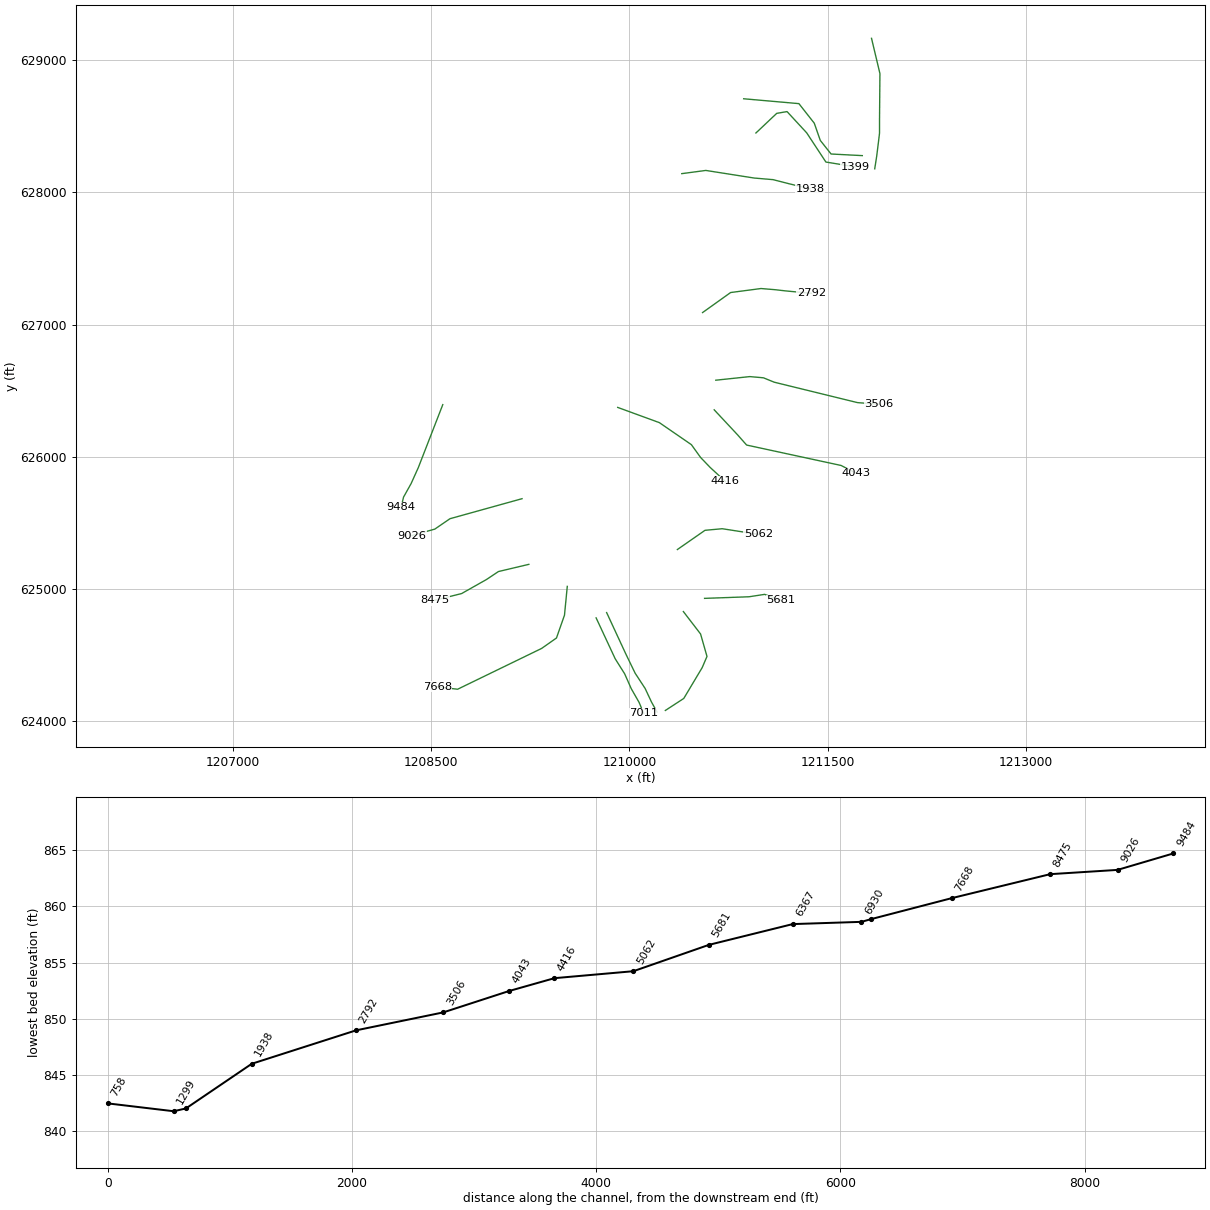
HEC-RAS study lds_hinton_crk.prj: Hinton Creek Limited Detail Study

--- lds_hinton_crk.g01 (geometry) --- (continued)

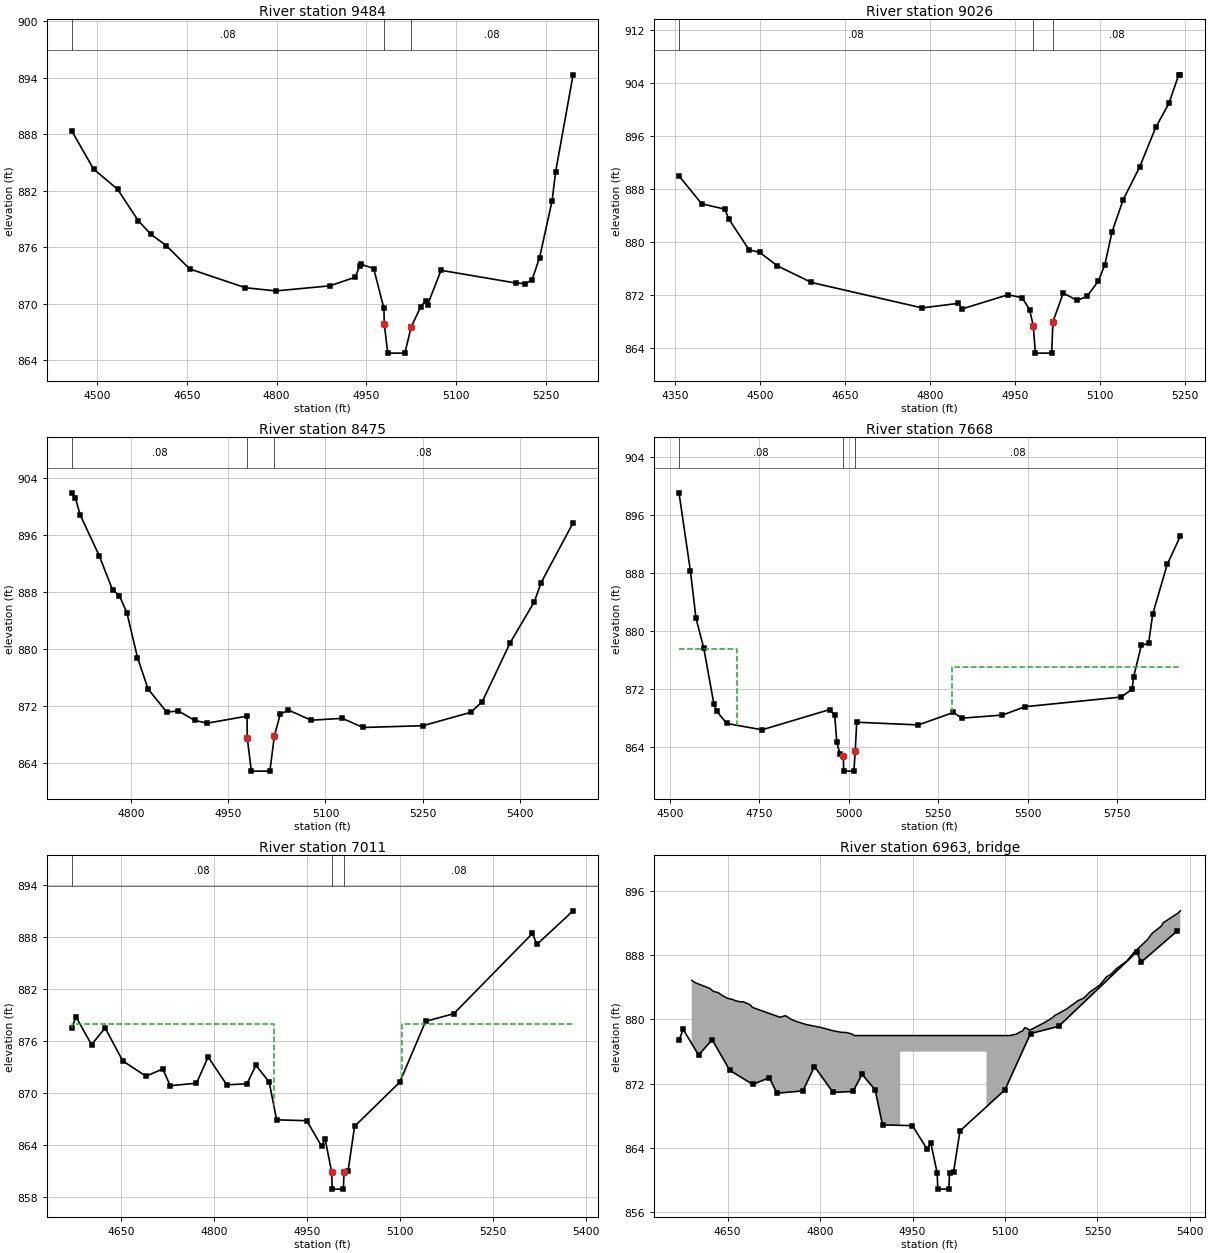
Type RM Length L Ch R = 1 ,9484    ,458,458,458
BEGIN DESCRIPTION:
Hinton Crk - 16.0
END DESCRIPTION:
XS GIS Cut Line= 5
      1208589.62       626395.31      1208404.99       625920.14
      1208350.52       625799.07      1208293.01       625696.17
      1208274.85        625620.5
#Sta/Elev= 30
  4457.4  888.34  4494.1  884.27    4534  882.15  4568.4  878.82  4589.8  877.35
  4615.8  876.14  4654.5  873.68  4747.7  871.68  4798.7  871.34    4889  871.88
  4931.6   872.8  4938.5  873.98  4941.8  874.16  4962.2  873.72  4979.3  869.48
 4979.94  867.85  4985.7  864.73  5014.3  864.73  5024.8  867.49  5040.8  869.65
  5049.1   870.3  5052.3  869.86  5074.8  873.53  5199.8  872.18    5216  872.12
    5227  872.52  5239.6  874.89  5260.5  880.92  5266.4     884  5295.6   894.3
#Mann= 3 ,-1 , 0
  4457.4     .08       0 4979.94     .05       0  5024.8     .08       0
Bank Sta=4979.94,5024.8
Exp/Cntr=0.3,0.1

Type RM Length L Ch R = 1 ,9026    ,551,551,551
BEGIN DESCRIPTION:
Hinton Crk - 15.0
END DESCRIPTION:
XS GIS Cut Line= 4
      1209188.89       625684.06       1208644.1       625532.73
      1208529.09       625454.04      1208356.57       625405.62
#Sta/Elev= 30
  4357.3  890.03  4397.4   885.8  4438.2  885.01  4444.8  883.56  4480.9  878.85
  4499.5  878.49  4530.5  876.45  4590.9  873.93  4785.9  870.09  4849.3  870.77
  4856.9  869.95  4937.4  872.08  4962.2  871.63  4975.4  869.83  4981.8  867.42
  4985.7  863.26  5014.3  863.26  5016.6  868.02  5034.8  872.34  5059.2  871.21
  5076.8  871.86  5096.9  874.18  5108.1  876.62  5120.8  881.58  5140.5  886.45
  5169.3  891.34  5197.9  897.37  5221.2     901  5238.3  905.29  5241.2  905.26
#Mann= 3 ,-1 , 0
  4357.3     .08       0  4981.8     .05       0  5016.6     .08       0
Bank Sta=4981.8,5016.6
Exp/Cntr=0.3,0.1

Type RM Length L Ch R = 1 ,8475    ,807,807,807
BEGIN DESCRIPTION:
Hinton Crk - 14.0
END DESCRIPTION:
XS GIS Cut Line= 5
      1209240.34        625187.7      1209010.32       625133.22
      1208919.52       625072.69      1208731.87       624966.76
      1208526.06       624915.31
#Sta/Elev= 30
  4708.7   901.9  4714.3  901.18  4721.9  898.76    4751   893.1  4771.6  888.31
  4782.3  887.47  4793.8  885.07  4810.1  878.81  4826.4   874.4    4855  871.17
  4873.3  871.31  4898.1     870  4917.4   869.6  4979.1  870.59 4979.34  867.58
  4985.7  862.88  5014.3  862.88  5021.2   867.8  5030.2  870.85  5042.7  871.45
  5077.9  870.02  5125.9  870.28  5158.1     869  5250.3  869.25  5324.3  871.13
  5341.9  872.64  5384.8  880.87  5422.1  886.62  5432.4  889.27  5481.9   897.7
#Mann= 3 ,-1 , 0
  4708.7     .08       0 4979.34     .05       0  5021.2     .08       0
Bank Sta=4979.34,5021.2
Exp/Cntr=0.3,0.1

Type RM Length L Ch R = 1 ,7668    ,657,657,657
BEGIN DESCRIPTION:
Hinton Crk - 13.0
END DESCRIPTION:
XS GIS Cut Line= 6
      1209530.89       625021.24      1209509.71       624803.32
      1209449.17        624630.8      1209337.19       624552.11
       1208701.6        624243.4      1208547.25       624261.56
#Sta/Elev= 30
  4525.7  899.11  4557.7   888.3  4573.1  881.85  4595.1  877.66  4623.3  869.97
    4631     869  4659.3  867.31  4757.9  866.44  4946.4  869.22  4960.8  868.45
  4966.5   864.8  4975.4  863.06    4985  862.89  4985.7  860.74  5014.3  860.74
 5018.07  863.55  5022.3  867.48  5194.6  867.11  5292.4  868.83  5315.9  868.04
  5429.5  868.47  5492.4  869.62  5761.3  870.96  5791.6  872.04  5795.9  873.74
  5817.4  878.09  5837.7  878.35  5849.1  882.36  5889.6  889.23  5926.4  893.15
#Mann= 3 ,-1 , 0
  4525.7     .08       0    4985     .05       0 5018.07     .08       0
#XS Ineff= 2 , 0
         4686.79  877.53 5287.63          875.03
Permanent Ineff=
       F       F
Bank Sta=4985,5018.07
Exp/Cntr=0.5,0.3

Type RM Length L Ch R = 1 ,7011    ,81,81,81
BEGIN DESCRIPTION:
Polkville Rd - US
END DESCRIPTION:
XS GIS Cut Line= 6
      1209748.88       624783.17      1209893.33       624473.34
      1209964.51        624360.3      1210014.75       624247.25
      1210073.37       624144.67      1210108.96       624060.93
#Sta/Elev= 30
    4571  877.44  4577.9  878.76  4602.9  875.56  4624.8  877.49  4653.3  873.68
  4690.6  871.92  4717.8  872.75  4729.8  870.82  4772.1  871.11  4790.9  874.14
    4821  870.92  4853.4  871.04    4868  873.17  4889.3  871.25  4901.3  866.88
  4949.9  866.78  4973.8  863.84  4979.6  864.64    4990  860.88    4991  858.88
    5009  858.88    5010  860.88  5016.6  861.01    5027  866.13  5099.9  871.23
  5141.5  878.25  5187.1  879.14  5313.8   888.4  5320.9  887.13  5379.3  891.01
#Mann= 3 ,-1 , 0
    4571     .08       0    4990     .05       0    5010     .08       0
#XS Ineff= 2 , 0
       0    4897     878    5103       0     878
Permanent Ineff=
       F       F
Bank Sta=4990,5010
Exp/Cntr=0.5,0.3

Type RM Length L Ch R = 3 ,6963    ,,,
BEGIN DESCRIPTION:
Polkville Rd
Structure ID: Polkville Rd
Approximate Survey Structure
END DESCRIPTION:
Bridge Culvert--1,0,-1,-1, 0
Deck Dist Width WeirC Skew NumUp NumDn MinLoCord MaxHiCord MaxSubmerge Is_Ogee
33,30,3,0, 53, 53, , , , 0, 1,1,,
  4591.6  4598.5  4621.1    4627  4634.6  4641.3  4650.4  4658.2  4662.4  4671.6
  4674.8  4685.8  4690.4  4734.6    4744  4753.4  4759.7  4777.6  4800.6  4820.6
  4834.5  4841.8  4851.5  4855.6    4930    4930    5070    5070  5108.1  5118.6
  5124.7  5128.1  5132.3  5140.6  5164.2  5176.7  5181.2  5199.8  5218.4  5228.2
  5237.8  5253.3  5265.1    5271  5280.2    5298    5308  5330.9  5338.8  5353.7
  5356.6  5381.2  5384.6
  884.87  884.55  883.87  883.49  883.35  882.98  882.62  882.49  882.34  882.19
  882.22  881.87   881.5  880.29  880.47  880.01   879.8  879.37  879.02  878.61
   878.4  878.39   878.2     878     878     878     878     878     878  878.18
  878.47  878.54     879  878.68  879.62  880.21  880.51   881.3  882.34  882.68
  883.43  884.24  885.34  885.56  886.29   887.3  888.25  889.92  890.73  891.63
  892.03  893.27  893.53
  838.88  838.88  838.88  838.88  838.88  838.88  838.88  838.88  838.88  838.88
  838.88  838.88  838.88  838.88  838.88  838.88  838.88  838.88  838.88  838.88
  838.88  838.88  838.88  838.88  838.88     876     876  838.88  838.88  838.88
  838.88  838.88  838.88  838.88  838.88  838.88  838.88  838.88  838.88  838.88
  838.88  838.88  838.88  838.88  838.88  838.88  838.88  838.88  838.88  838.88
  838.88  838.88  838.88
  4591.6  4598.5  4621.1    4627  4634.6  4641.3  4650.4  4658.2  4662.4  4671.6
  4674.8  4685.8  4690.4  4734.6    4744  4753.4  4759.7  4777.6  4800.6  4820.6
  4834.5  4841.8  4851.5  4855.6    4930    4930    5070    5070  5108.1  5118.6
  5124.7  5128.1  5132.3  5140.6  5164.2  5176.7  5181.2  5199.8  5218.4  5228.2
  5237.8  5253.3  5265.1    5271  5280.2    5298    5308  5330.9  5338.8  5353.7
  5356.6  5381.2  5384.6
  884.87  884.55  883.87  883.49  883.35  882.98  882.62  882.49  882.34  882.19
  882.22  881.87   881.5  880.29  880.47  880.01   879.8  879.37  879.02  878.61
   878.4  878.39   878.2     878     878     878     878     878     878  878.18
  878.47  878.54     879  878.68  879.62  880.21  880.51   881.3  882.34  882.68
  883.43  884.24  885.34  885.56  886.29   887.3  888.25  889.92  890.73  891.63
  892.03  893.27  893.53
  838.88  838.88  838.88  838.88  838.88  838.88  838.88  838.88  838.88  838.88
  838.88  838.88  838.88  838.88  838.88  838.88  838.88  838.88  838.88  838.88
  838.88  838.88  838.88  838.88  838.88     876     876  838.88  838.88  838.88
  838.88  838.88  838.88  838.88  838.88  838.88  838.88  838.88  838.88  838.88
  838.88  838.88  838.88  838.88  838.88  838.88  838.88  838.88  838.88  838.88
  838.88  838.88  838.88
Abutment Skew #Up #Dn= , 2 , 2
    4930    4935
     876   866.6
    4930    4935
     876  867.48
Abutment Skew #Up #Dn= , 2 , 2
    5065    5070
  868.91     876
    5065    5070
  870.99     876
BR Coef= 1 , 1 , 0 ,1.25, 0 ,,,0.8,0,2,0,
WSPro=,,,, 1 ,,,, 0 ,,,, 0 ,,,,-1 ,-1 ,-1 , 0 , 0 , 0 , 0 , 0
BC Design=,, 0 ,, 0 ,,,,,,
BC HTab HWMax=891.01

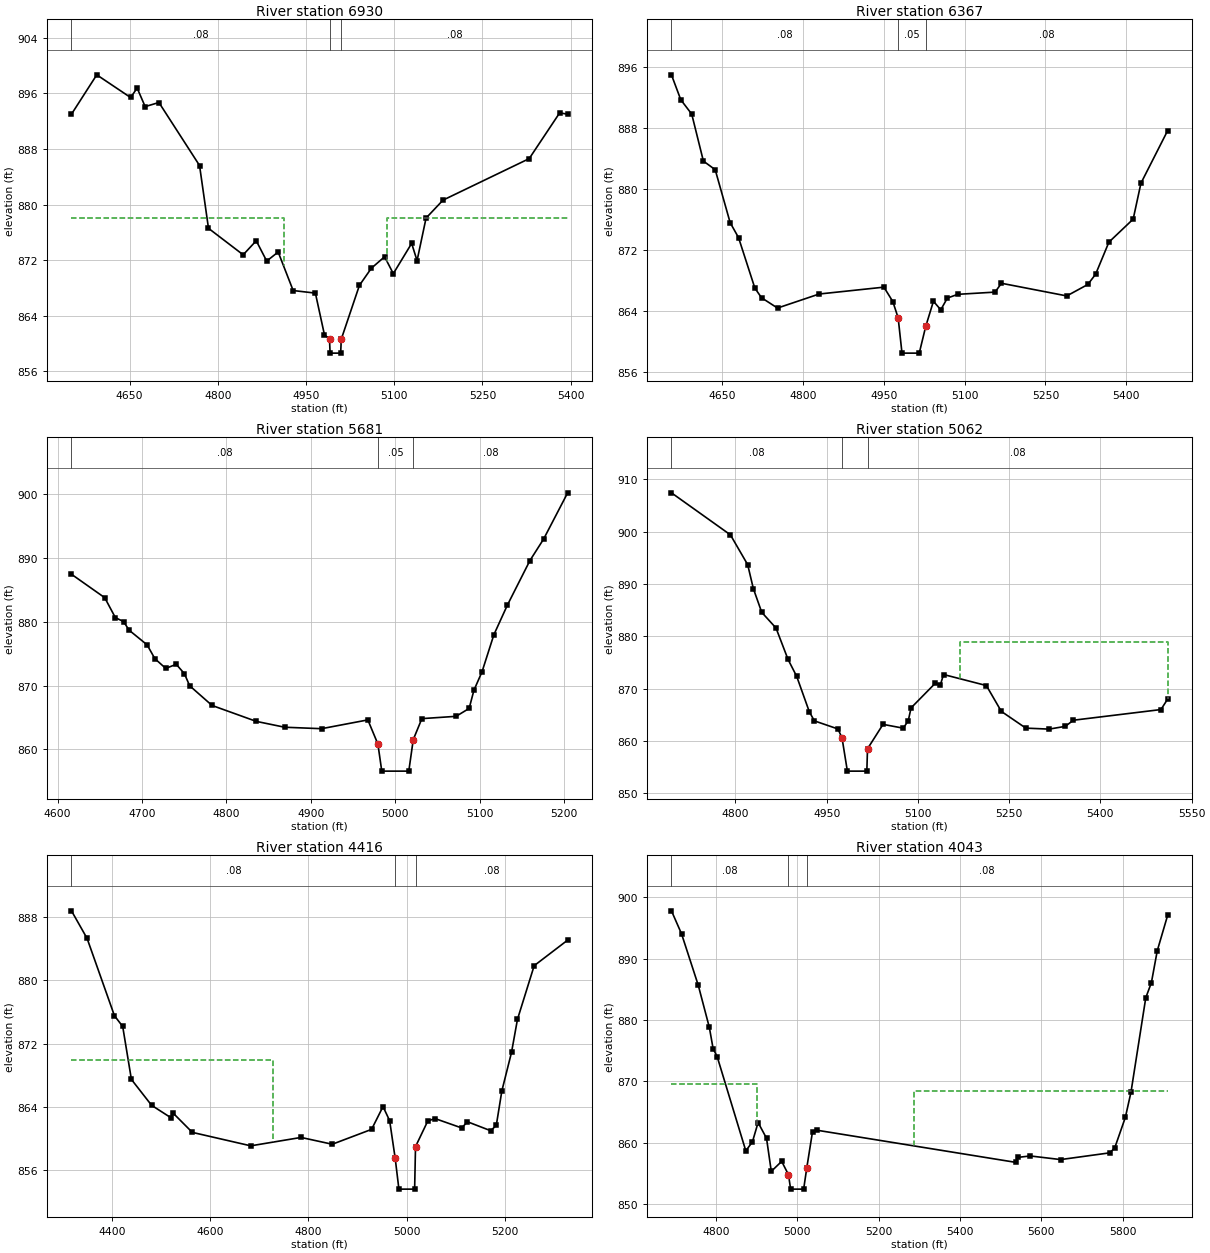
Type RM Length L Ch R = 1 ,6930    ,563,563,563
BEGIN DESCRIPTION:
Polkville Rd - DS
END DESCRIPTION:
XS GIS Cut Line= 6
      1209828.44       624822.95      1209974.98       624506.84
      1210044.06       624364.48      1210119.43       624249.34
      1210167.57       624146.77      1210209.44        624071.4
#Sta/Elev= 30
  4551.2  892.99  4594.2  898.65  4651.7  895.39  4662.9  896.74  4676.5  894.08
  4699.9  894.67    4769  885.61  4784.2  876.58  4843.2  872.77  4865.4  874.79
  4883.2  871.87  4902.7  873.17  4928.2  867.63    4966  867.26 4981.36  861.28
    4990  860.63    4991  858.63    5009  858.63    5010  860.63  5040.9  868.38
  5061.2  870.84  5083.7  872.49  5098.5  870.06  5129.7  874.41  5138.9  871.93
  5154.2  878.05    5183  880.63  5329.6   886.6  5381.4  893.18    5395  892.99
#Mann= 3 ,-1 , 0
  4551.2     .08       0    4990     .05       0    5010     .08       0
#XS Ineff= 2 , 0
       0    4912     878    5088       0     878
Permanent Ineff=
       F       F
Bank Sta=4990,5010
Exp/Cntr=0.5,0.3

Type RM Length L Ch R = 1 ,6367    ,686,686,686
BEGIN DESCRIPTION:
Hinton Crk - 9.0
END DESCRIPTION:
XS GIS Cut Line= 6
      1210408.61       624830.56      1210538.75       624661.07
      1210587.18       624491.58      1210550.86       624406.84
      1210411.63       624173.79      1210272.41       624082.99
#Sta/Elev= 30
  4556.6  894.92  4573.9  891.65  4594.2  889.77  4615.8  883.61  4637.7  882.48
  4665.4  875.54    4681  873.57  4711.2  866.96  4723.6  865.69  4753.2  864.34
  4830.4  866.18  4950.5  867.08    4967  865.19  4976.9  863.05    4984  858.43
    5016  858.43    5028  861.93  5042.3  865.23  5055.9  864.11  5068.1  865.65
  5087.4  866.14  5156.5  866.43  5168.4  867.59  5289.5  865.93  5328.5  867.43
    5343  868.78  5367.6  872.98  5412.6     876    5427  880.71  5476.5   887.6
#Mann= 3 ,-1 , 0
  4556.6     .08       0  4976.9     .05       0    5028     .08       0
Bank Sta=4976.9,5028
Exp/Cntr=0.3,0.1

Type RM Length L Ch R = 1 ,5681    ,619,619,619
BEGIN DESCRIPTION:
Hinton Crk - 8.0
END DESCRIPTION:
XS GIS Cut Line= 4
      1210569.02       624930.44      1210904.97       624942.54
      1211023.01        624960.7       1211147.1       624915.31
#Sta/Elev= 30
  4616.4  887.48  4655.8   883.8  4668.4  880.67  4678.1  880.05  4684.7   878.7
    4706   876.4  4715.2  874.23  4728.1   872.7  4740.5  873.35  4750.2  871.87
  4756.4  869.98  4782.9  866.89  4835.3  864.39  4868.9  863.47  4912.6  863.24
  4967.5  864.62  4979.4  860.83    4984  856.58    5016  856.58  5021.3  861.53
  5031.5  864.82    5072  865.18  5087.5  866.42  5093.1  869.25  5102.8  872.19
  5116.8  877.99  5132.7  882.61  5159.5  889.63  5175.7     893  5204.2  900.26
#Mann= 3 ,-1 , 0
  4616.4     .08       0  4979.4     .05       0  5021.3     .08       0
Bank Sta=4979.4,5021.3
Exp/Cntr=0.3,0.1

Type RM Length L Ch R = 1 ,5062    ,646,646,646
BEGIN DESCRIPTION:
Hinton Crk - 7.0
END DESCRIPTION:
XS GIS Cut Line= 4
      1210363.21       625299.68      1210572.04       625444.96
      1210702.19       625457.07      1210974.58        625414.7
#Sta/Elev= 30
  4694.8  907.43  4791.7   899.4  4820.1   893.7  4829.4  889.13  4843.2  884.59
  4866.7  881.58  4886.5  875.57  4900.7  872.34  4921.4  865.59  4929.7  863.84
  4968.5  862.29  4975.2  860.59    4984  854.23    5016  854.23  5017.1   858.5
  5042.6  863.17  5075.9  862.44  5084.1  863.87  5088.7  866.32  5128.8  871.06
  5136.7  870.66  5142.1   872.7  5212.5  870.59  5237.1  865.65  5277.4  862.45
  5315.7  862.26  5342.3  862.79  5355.5  863.96  5499.5     866  5510.5     868
#Mann= 3 ,-1 , 0
  4694.8     .08       0  4975.2     .05       0  5017.1     .08       0
#XS Ineff= 2 , 0
                         5168.97          878.84
Permanent Ineff=
       F       F
Bank Sta=4975.2,5017.1
Exp/Cntr=0.3,0.1

Type RM Length L Ch R = 1 ,4416    ,373,373,373
BEGIN DESCRIPTION:
Hinton Crk - 6.0
END DESCRIPTION:
XS GIS Cut Line= 6
      1209912.24       626374.13      1210227.01       626259.12
      1210469.14       626092.65      1210538.75        625995.8
      1210611.39       625920.14       1210726.4       625814.21
#Sta/Elev= 30
  4317.9  888.77  4349.7  885.28  4405.3  875.52  4422.1  874.16  4439.8  867.47
  4480.9   864.2  4519.7  862.65  4524.9   863.2  4563.7  860.78  4682.6  859.08
    4785  860.14  4848.4  859.28  4928.4  861.16  4951.7  864.04  4965.2  862.25
  4976.5  857.48    4984  853.61    5016  853.61  5017.8  858.98  5042.7  862.21
  5057.3  862.53  5111.7  861.34  5123.5  862.12  5170.7  860.99  5182.1  861.66
  5193.5  866.04  5213.1  870.89  5225.2  875.06  5259.2  881.84  5327.3  885.07
#Mann= 3 ,-1 , 0
  4317.9     .08       0  4976.5     .05       0  5017.8     .08       0
#XS Ineff= 2 , 0
         4727.83  869.91
Permanent Ineff=
       F       F
Bank Sta=4976.5,5017.8
Exp/Cntr=0.3,0.1

Type RM Length L Ch R = 1 ,4043    ,537,537,537
BEGIN DESCRIPTION:
Hinton Crk - 5.0
END DESCRIPTION:
XS GIS Cut Line= 5
      1210641.66       626355.97       1210817.2       626168.32
      1210886.81       626089.63      1211601.09       625935.27
      1211713.07       625877.77
#Sta/Elev= 30
  4691.3  897.76  4716.1  894.01  4757.2  885.63  4784.4  878.77  4793.6  875.33
  4803.6  874.02  4873.9  858.69  4890.2  860.16  4904.1   863.3  4924.8  860.74
  4936.5  855.35    4962  856.98  4978.7  854.81    4984  852.46    5016  852.46
 5023.78  855.97  5037.8  861.83  5049.5  862.04  5536.6  856.82  5542.4  857.63
  5572.5  857.86  5647.2  857.27  5768.2  858.37  5780.2   859.2  5806.2  864.15
  5819.9  868.22  5856.3  883.61  5870.1  886.07  5884.5  891.26    5910  897.03
#Mann= 3 ,-1 , 0
  4691.3     .08       0  4978.7     .05       0 5023.78     .08       0
#XS Ineff= 2 , 0
         4901.01  869.52 5286.79          868.49
Permanent Ineff=
       F       F
Bank Sta=4978.7,5023.78
Exp/Cntr=0.3,0.1

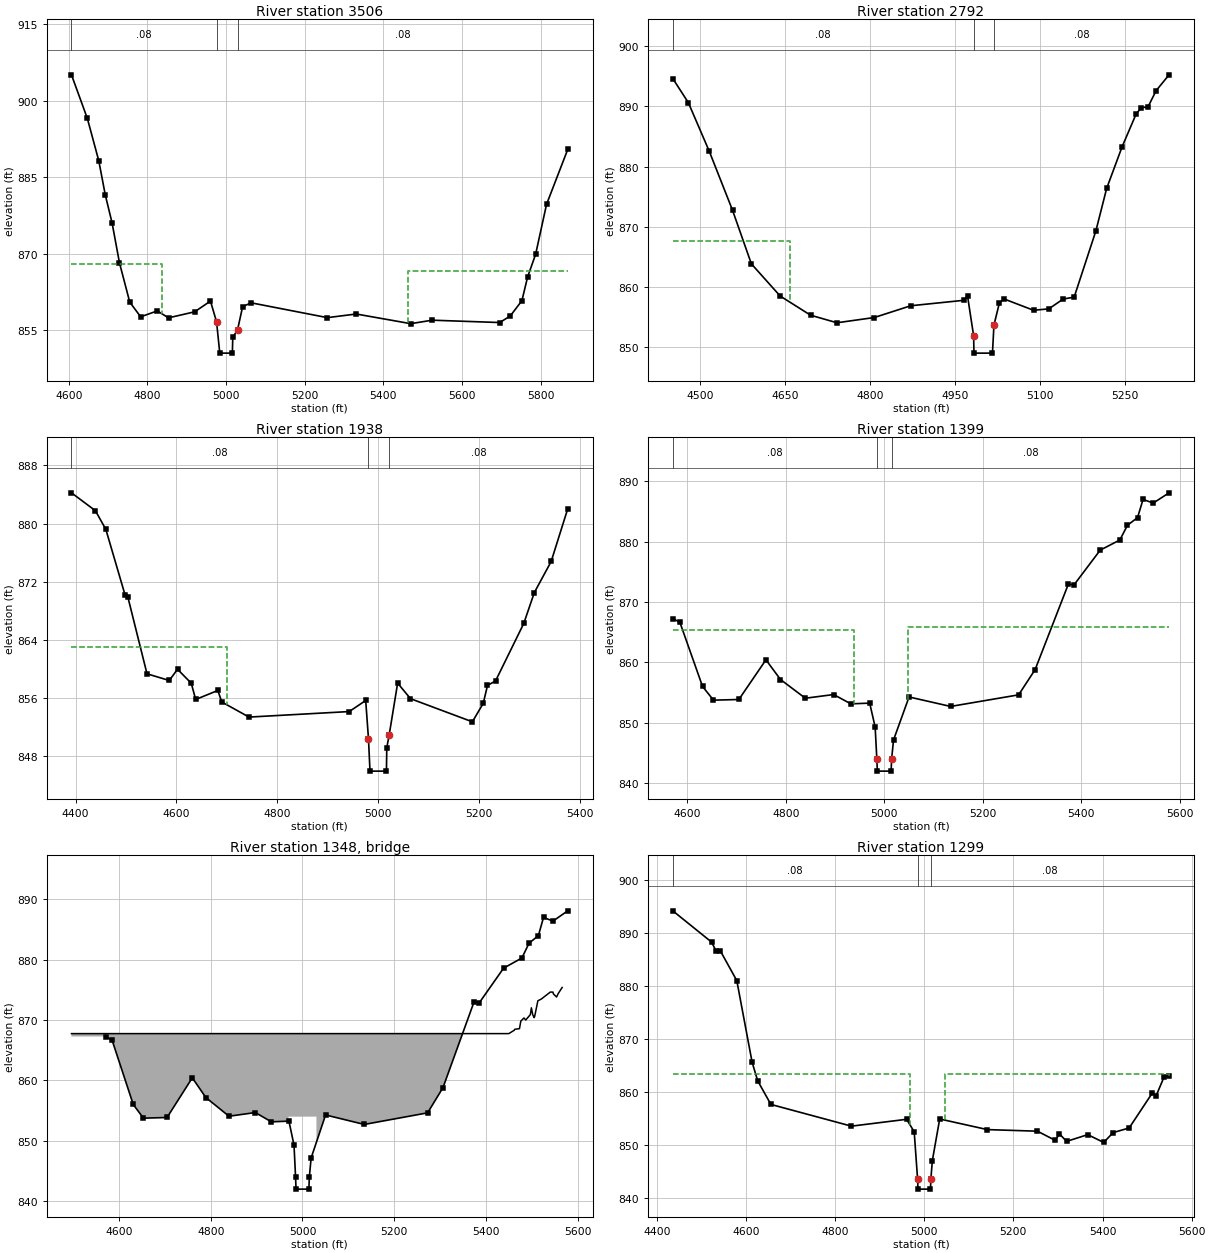
Type RM Length L Ch R = 1 ,3506    ,714,714,714
BEGIN DESCRIPTION:
Hinton Crk - 4.0
END DESCRIPTION:
XS GIS Cut Line= 6
      1210653.76       626579.94      1210911.02       626607.18
      1211013.93        626598.1      1211095.65        626564.8
      1211725.18       626410.45      1211888.62       626398.34
#Sta/Elev= 30
  4606.8  905.06  4647.2  896.51  4676.3  888.21  4692.8  881.53  4710.1  876.05
  4728.8  868.26    4755  860.55  4782.8  857.67  4825.1  858.83  4853.6  857.47
  4920.1  858.65  4960.3  860.75  4975.8   856.7    4984  850.56    5016  850.56
  5017.1  853.67  5029.1  855.08  5042.1  859.66  5063.9  860.41  5257.7  857.51
  5331.1  858.22  5469.7  856.33  5524.3  857.01    5696  856.55  5722.7  857.82
  5752.5  860.83  5766.8  865.42  5787.4  869.92  5815.1  879.68  5869.1  890.46
#Mann= 3 ,-1 , 0
  4606.8     .08       0  4975.8     .05       0  5029.1     .08       0
#XS Ineff= 2 , 0
         4837.12     868 5461.79          866.71
Permanent Ineff=
       F       F
Bank Sta=4975.8,5029.1
Exp/Cntr=0.3,0.1

Type RM Length L Ch R = 1 ,2792    ,854,854,854
BEGIN DESCRIPTION:
Hinton Crk - 3.0
END DESCRIPTION:
XS GIS Cut Line= 6
      1210553.88       627091.43      1210765.75       627242.76
      1210995.77       627273.03      1211104.73       627263.95
      1211183.42       627254.87      1211377.12       627236.71
#Sta/Elev= 30
  4452.4  894.63  4479.8  890.63  4516.8  882.52  4557.8  872.72    4591  863.81
  4641.8  858.46  4695.4  855.27    4742  854.01  4807.7  854.88  4872.2  856.84
  4965.3  857.74  4972.3  858.48    4983  851.88  4983.7  848.96  5016.3  848.96
  5018.9  853.62  5028.5  857.31  5036.5  857.98  5088.7  856.09  5115.6  856.32
  5141.1  857.96  5160.4  858.27  5198.7  869.29  5217.7  876.35  5244.7  883.22
  5269.9  888.78  5278.6  889.74  5290.9  889.96  5304.9  892.61  5327.8  895.25
#Mann= 3 ,-1 , 0
  4452.4     .08       0    4983     .05       0  5018.9     .08       0
#XS Ineff= 2 , 0
         4658.62  867.58
Permanent Ineff=
       F       F
Bank Sta=4983,5018.9
Exp/Cntr=0.3,0.1

Type RM Length L Ch R = 1 ,1938    ,539,539,539
BEGIN DESCRIPTION:
Hinton Crk - 2.0
END DESCRIPTION:
XS GIS Cut Line= 6
       1210396.5       628141.67       1210578.1       628165.88
      1210944.32       628108.37      1211086.57       628096.27
       1211204.6         628066.      1211365.01       628026.65
#Sta/Elev= 30
    4392  884.24  4439.4  881.78  4460.1  879.22    4498  870.25  4503.7  869.93
  4541.7  859.36  4585.8  858.44  4602.2  859.98  4629.4  858.07 4638.18  855.83
  4682.1  857.07  4689.9  855.49  4743.9  853.41  4942.6  854.17  4975.2  855.69
 4980.69  850.45  4983.7  845.98  5016.3  845.98    5017  849.21  5021.8  850.98
  5038.5  858.08    5064  855.94  5186.6  852.76  5208.2   855.3  5216.6  857.76
  5232.6  858.38  5288.5  866.28  5309.4  870.52  5342.8   874.8  5375.7  882.05
#Mann= 3 ,-1 , 0
    4392     .08       0 4980.69     .05       0  5021.8     .08       0
#XS Ineff= 2 , 0
         4700.94  863.06
Permanent Ineff=
       F       F
Bank Sta=4980.69,5021.8
Exp/Cntr=0.5,0.3

Type RM Length L Ch R = 1 ,1399    ,100,100,100
BEGIN DESCRIPTION:
Jackson White Rd SR 1521 - US
END DESCRIPTION:
XS GIS Cut Line= 6
      1210957.08       628448.96      1211114.42       628597.48
       1211192.5       628610.79       1211340.8       628450.38
      1211486.08       628229.44      1211707.02       628193.12
#Sta/Elev= 30
  4570.8  867.27  4585.2  866.64  4631.2  856.02  4653.4  853.75  4704.9  853.86
  4759.9  860.43  4789.4  857.17  4839.9  854.07  4897.3  854.68  4932.3  853.14
  4970.5  853.26  4981.6  849.29    4985     844    4986     842    5014     842
    5015     844  5018.9  847.16  5050.4  854.28  5134.8  852.71  5272.8  854.63
  5306.3  858.81  5373.9  872.99    5385  872.81  5438.4  878.59  5478.3  880.27
  5493.8  882.72  5514.2  883.97  5525.4  886.99    5546  886.38  5578.2  888.08
#Mann= 3 ,-1 , 0
  4570.8     .08       0    4985     .05       0    5015     .08       0
#XS Ineff= 2 , 0
         4939.29  865.45    5048          865.91
Permanent Ineff=
       F       F
Bank Sta=4985,5015
Exp/Cntr=0.5,0.3

Type RM Length L Ch R = 3 ,1348    ,,,
BEGIN DESCRIPTION:
Jackson White Rd SR 1521
Structure ID: Jackson White Rd SR 1521
Approximate Survey Structure
END DESCRIPTION:
Bridge Culvert--1,0,-1,-1, 0
Deck Dist Width WeirC Skew NumUp NumDn MinLoCord MaxHiCord MaxSubmerge Is_Ogee
40,22,3,0, 25, 25, , , , 0, 1,1,,
  4496.6  4969.5  4969.5  5030.5  5030.5  5449.7  5461.7  5462.8    5473  5475.9
  5482.8  5486.6  5496.8  5498.9    5502  5504.9    5506  5513.1  5520.5  5540.2
    5546  5546.9  5553.8  5557.4    5566
  867.75  867.75  867.75  867.75  867.75  867.75  868.31  868.47  868.57  869.82
  870.34     870  870.91  872.02  870.86   870.4  870.56  873.19  873.47  874.63
  874.62  874.33  873.81  874.38  875.39
     822     822     854     854     822     822     822     822     822     822
     822     822     822     822     822     822     822     822     822     822
     822     822     822     822     822
  4496.6  4969.5  4969.5  5030.5  5030.5  5449.7  5461.7  5462.8    5473  5475.9
  5482.8  5486.6  5496.8  5498.9    5502  5504.9    5506  5513.1  5520.5  5540.2
    5546  5546.9  5553.8  5557.4    5566
  867.75  867.75  867.75  867.75  867.75  867.75  868.31  868.47  868.57  869.82
  870.34     870  870.91  872.02  870.86   870.4  870.56  873.19  873.47  874.63
  874.62  874.33  873.81  874.38  875.39
     822     822     854     854     822     822     822     822     822     822
     822     822     822     822     822     822     822     822     822     822
     822     822     822     822     822
Abutment Skew #Up #Dn= , 2 , 2
  4969.5  4974.5
     854  851.74
  4969.5  4974.5
     854  852.99
Abutment Skew #Up #Dn= , 2 , 2
  5025.5  5030.5
  848.68     854
  5025.5  5030.5
  850.75     854
BR Coef= 1 , 1 , 0 ,1.25, 0 ,,,0.8,0,2,0,
WSPro=,,,, 1 ,,,, 0 ,,,, 0 ,,,,-1 ,-1 ,-1 , 0 , 0 , 0 , 0 , 0
BC Design=,, 0 ,, 0 ,,,,,,
BC HTab HWMax=888.08

Type RM Length L Ch R = 1 ,1299    ,541,541,541
BEGIN DESCRIPTION:
Jackson White Rd SR 1521 - DS
END DESCRIPTION:
XS GIS Cut Line= 6
      1210864.44       628707.76      1211282.05         628671.
      1211398.31        628523.1      1211443.71       628392.96
      1211525.42       628290.05       1211761.5       628277.95
#Sta/Elev= 30
  4435.9  894.16  4522.8  888.28  4533.6  886.51  4542.3  886.66  4579.5  881.02
  4613.8  865.67  4626.4  862.14    4656   857.7  4836.7  853.61  4960.4   854.9
  4977.5  852.56    4985  843.75    4986  841.75    5014  841.75    5015  843.75
  5018.2  847.11  5034.7  854.96  5141.7  852.96  5254.1  852.66    5294  850.93
  5303.3  852.16  5319.4  850.74  5366.9  852.01  5402.7  850.54  5423.7  852.39
  5459.8  853.27  5512.1   859.9    5520  859.28  5538.5  862.95  5549.3  863.11
#Mann= 3 ,-1 , 0
  4435.9     .08       0    4985     .05       0    5015     .08       0
#XS Ineff= 2 , 0
         4968.27  863.45 5045.83          863.45
Permanent Ineff=
       F       F
Bank Sta=4985,5015
Exp/Cntr=0.5,0.3

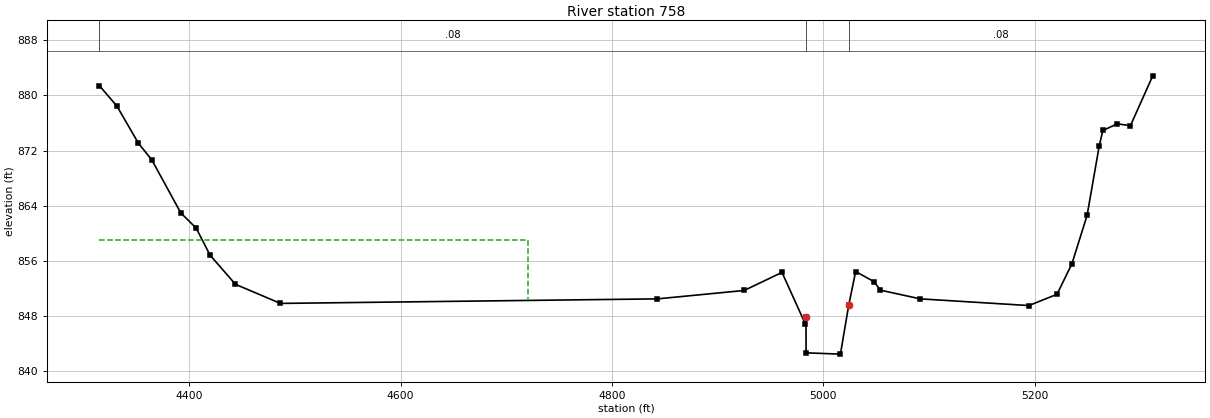
Type RM Length L Ch R = 1 ,758     ,0,0,0
BEGIN DESCRIPTION:
Hinton_Crk - 1.0
END DESCRIPTION:
XS GIS Cut Line= 6
      1211831.11       629164.66      1211894.67       628898.32
      1211891.64       628547.23      1211891.64       628447.35
      1211870.46       628274.84      1211855.32       628177.98
#Sta/Elev= 30
    4315  881.42  4331.7  878.43    4352  873.05  4364.6  870.65  4392.1  862.94
  4406.6  860.74  4419.8  856.81  4443.8  852.58  4486.4  849.81  4843.1  850.47
  4925.1  851.69  4960.9  854.31  4982.9  846.86  4983.6  847.81  4983.7  842.64
  5016.2  842.45  5024.1   849.6  5030.6  854.44  5048.3  852.94  5053.8  851.74
  5091.8  850.47  5194.5   849.5  5221.1  851.13  5235.2  855.55  5249.6   862.6
  5261.1   872.7  5264.5  874.91  5278.1  875.87  5290.6  875.61  5311.7  882.84
#Mann= 3 ,-1 , 0
    4315     .08       0  4983.6     .05       0  5024.1     .08       0
#XS Ineff= 2 , 0
         4720.75  858.95
Permanent Ineff=
       F       F
Bank Sta=4983.6,5024.1
Exp/Cntr=0.3,0.1

Chan Stop Cuts=-1
Use User Specified Reach Order=0
User Specified Reach Order=Hinton Creek    ,Reach-1