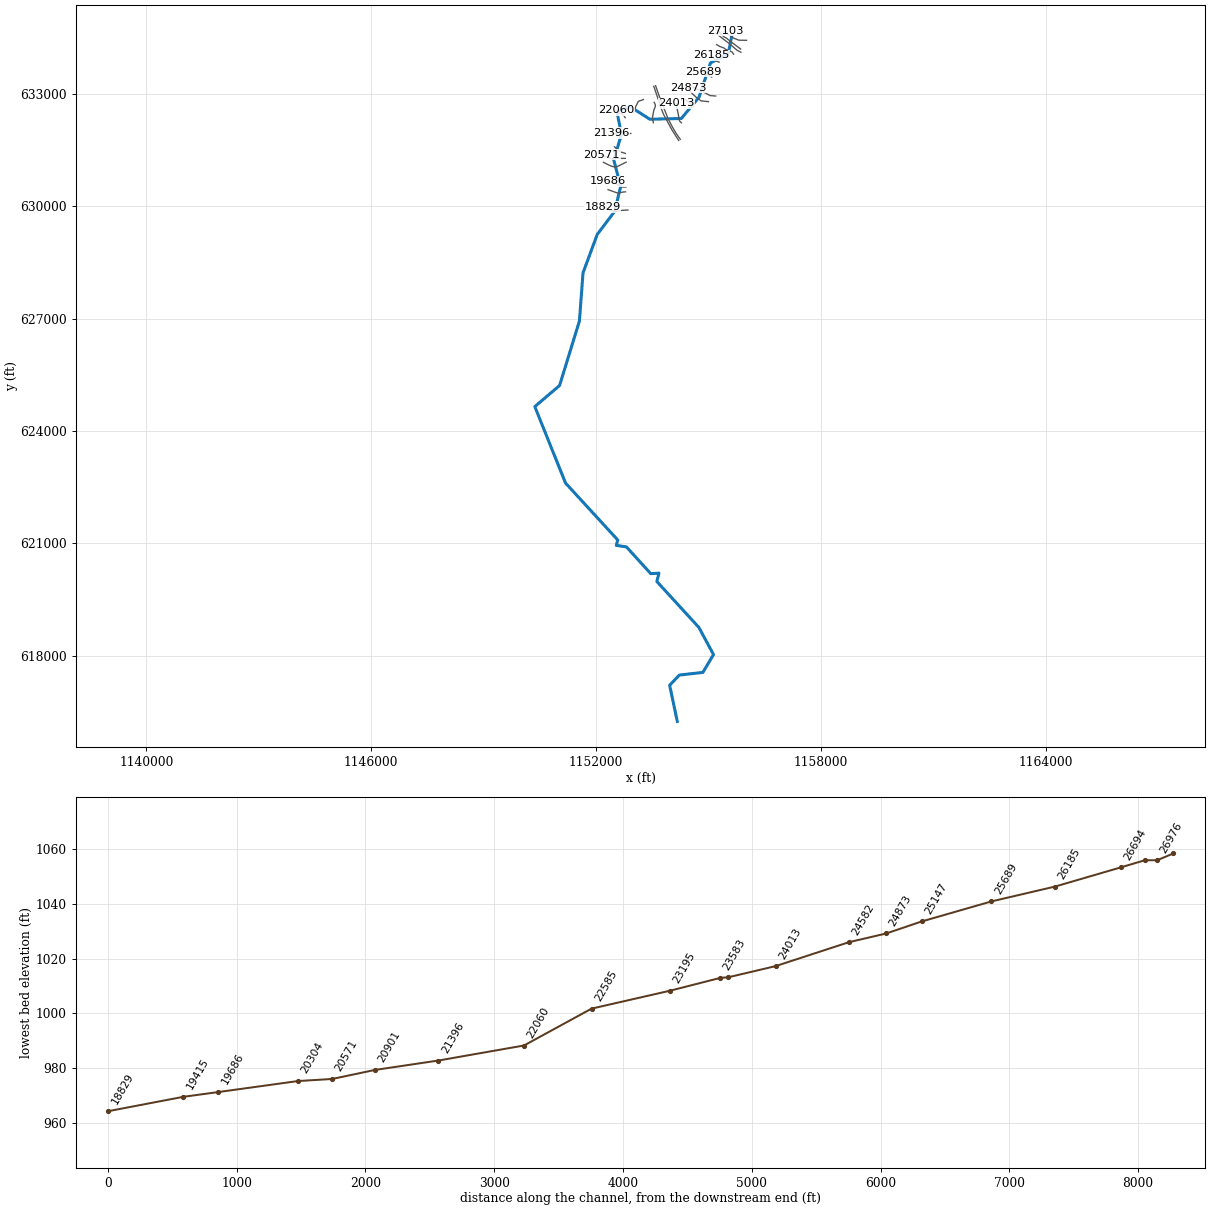
--- lds_hunting_crk.prj (project) ---

Proj Title=Hunting Creek Limited Detail Study
Current Plan=p02
Default Exp/Contr=0.3,0.1
English Units
Geom File=g01
Flow File=f02
Plan File=p02
Y Axis Title=Elevation
X Axis Title(PF)=Main Channel Distance
X Axis Title(XS)=Station
BEGIN DESCRIPTION:
Hunting Creek
END DESCRIPTION:
DSS Export Rating Curves= 0
DSS Export Rating Curve Sorted= 0
DSS Export Volume Flow Curves= 0
DXF OffsetX= 0
DXF OffsetY= 0
DXF ScaleX= 1
DXF ScaleY= 10

--- lds_hunting_crk.p02 (plan) ---

Plan Title=Floodway Run
Program Version=3.13
Short Identifier=Floodway
Geom File=g01
Flow File=f02
Subcritical Flow
K Sum by GR= 0
Std Step Tol= 0.01
Critical Tol= 0.01
Num of Std Step Trials= 20
Max Error Tol= 0.3
Flow Tol Ratio= 0.001
Split Flow NTrial= 30
Split Flow Tol= 0.02
Split Flow Ratio= 0.02
Log Output Level= 0
Friction Slope Method= 1
Unsteady Friction Slope Method= 2
Unsteady Bridges Friction Slope Method= 1
Parabolic Critical Depth
Global Vel Dist= 0 , 0 , 0
Global Log Level= 0
CheckData=True
Encroach Param=-1 ,10,10, 2
Encroach River=Hunting Creek
Encroach Reach=Reach-1
Encroach Node=27103
       4      .7
Encroach Node=26976
       1    4930  5052.5
Encroach Node=26881
       1    4930    5065
Encroach Node=26694
       4      .7
Encroach Node=26185
       4      .7
Encroach Node=25689
       4      .7
Encroach Node=25147
       4      .7
Encroach Node=24873
       4      .7
Encroach Node=24582
       1    4970    5020
Encroach Node=24013
       1    4987    5030
Encroach Node=23647
       1    4980    5020
Encroach Node=23583
       1    4980    5020
Encroach Node=23195
       4      .7
Encroach Node=22585
       1  4964.6  5046.4
Encroach Node=22060
       1    4950  5014.2
Encroach Node=21396
       4      .7
Encroach Node=20901
       1    4950    5050
Encroach Node=20571
       1    4880    5020
Encroach Node=20304
       1    4950    5030
Encroach Node=19686
       1    4960    5060
Encroach Node=19415
       4      .7
Encroach Node=18829
       1    4975    5054
Encroach Node=18186
       4      .7
Encroach Node=17694
       4      .7
Encroach Node=17141
       4      .7
Encroach Node=16852
       1  4948.5  5026.6
Encroach Node=16805
       1  4949.5 5019.59
Encroach Node=16494
       1    4967    5040
Encroach Node=15803
       4      .7
Encroach Node=15212
       4      .7
Encroach Node=14499
       4      .7
Encroach Node=14116
       1    4940    5130
Encroach Node=13331
       1 4988.65    5180
Encroach Node=12517
       1    4940    5080
Encroach Node=11637
       1    4900    5080
Encroach Node=11185
       4      .7
Encroach Node=10796
       4      .7
Encroach Node=10573
       1  4971.3 5022.37
Encroach Node=10516
       1  4963.4    5029
Encroach Node=10163
       4      .7
Encroach Node=9565
       4      .7
Encroach Node=8901
       1    4930    5025
Encroach Node=8205
       4      .7
Encroach Node=7615
       1    4940    5075
Encroach Node=7118
       1 4969.87 5029.22
Encroach Node=7060
       1    4970    5030
Encroach Node=6581
       4      .7
Encroach Node=5933
       4      .7
Encroach Node=5244
       4      .7
Encroach Node=4738
       4      .7
Encroach Node=4253
       4      .7
Encroach Node=3724
       1    4890    5060
Encroach Node=3211
       1    4890    5035
Encroach Node=2740
       1    4960    5038
Encroach Node=2189
       1    4972    5037
Encroach Node=1650
       1  4965.4    5055
Encroach Node=1507
       14958.929 5040.89
Encroach Node=1450
       1    4959    5041
Encroach Node=998
       4      .7
Encroach Node=439
       4      .7
BEGIN DESCRIPTION:
Floodway Run
END DESCRIPTION:
Computation Interval=1HOUR
Output Interval=1HOUR
Run HTab= 0
Run UNet= 0
Run PostProcess= 0
UNET Theta= 1
UNET Theta Warmup= 1
UNET ZTol= 0.02
UNET ZSATol= 0.05
UNET MxIter= 20
UNET MaxInSteps= 0
UNET DtIC= 0
UNET DtMin= 0
UNET MaxCRTS= 20
UNET WFStab= 2
UNET SFStab= 1
UNET WFX= 1
UNET SFX= 1
UNET DSS MLevel= 4
UNET DZMax Abort= 100
UNET Convert EG Bridges=-1
UNET Use Existing IB Tables=-1
UNET Froude Reduction=False
UNET Froude Limit= 1
UNET Froude Power= 10
Instantaneous Interval=1HOUR
Write IC File= 0
Echo Input=False
Echo Output=False
Write Detailed= 0
Detailed Automatic Start=False, 10

--- lds_hunting_crk.f02 (steady flow) ---

Flow Title=Floodway
Program Version=3.13
Number of Profiles= 2
Profile Names=100-year,100-FW
River Rch & RM=Hunting Creek,Reach-1         ,27103
    1370    1370
River Rch & RM=Hunting Creek,Reach-1         ,22060
    1730    1730
River Rch & RM=Hunting Creek,Reach-1         ,14116
    2020    2020
River Rch & RM=Hunting Creek,Reach-1         ,8205
    2160    2160
River Rch & RM=Hunting Creek,Reach-1         ,5244
    2460    2460
River Rch & RM=Hunting Creek,Reach-1         ,3724
    2550    2550
Boundary for River Rch & Prof#=Hunting Creek,Reach-1         , 1
Up Type= 0
Dn Type= 3
Dn Slope=0.005
Boundary for River Rch & Prof#=Hunting Creek,Reach-1         , 2
Up Type= 0
Dn Type= 3
Dn Slope=0.005
DSS Import GetInterval= 0
DSS Import GetPeak= 0
DSS Import FillOption= 0

--- lds_hunting_crk.g01 (geometry) ---

Geom Title=Existing Conditions
Program Version=3.13

River Reach=Hunting Creek   ,Reach-1
Reach XY= 30
      1155620.55       634534.99      1155527.25       634066.94
      1155053.25       633823.06        1154746.       632906.38
      1154275.63       632338.63       1153434.5       632318.63
      1152900.63       632660.69      1152556.13       632516.56
      1152676.75       631916.75      1152471.88         631231.
      1152655.88        630523.5      1152494.25       629858.06
      1152030.88         629245.      1151651.13       628220.69
      1151554.63       626931.63        1151025.       625211.81
      1150364.25       624649.75       1151184.5       622608.63
      1152577.75       621090.38       1152539.5       620946.31
      1152810.38        620905.5      1153457.88       620191.94
      1153678.38       620204.13      1153621.25         619982.
      1154742.38       618757.31        1155133.       618032.38
      1154850.88       617556.25      1154221.13       617484.81
       1153962.5       617213.06      1154166.88       616249.13

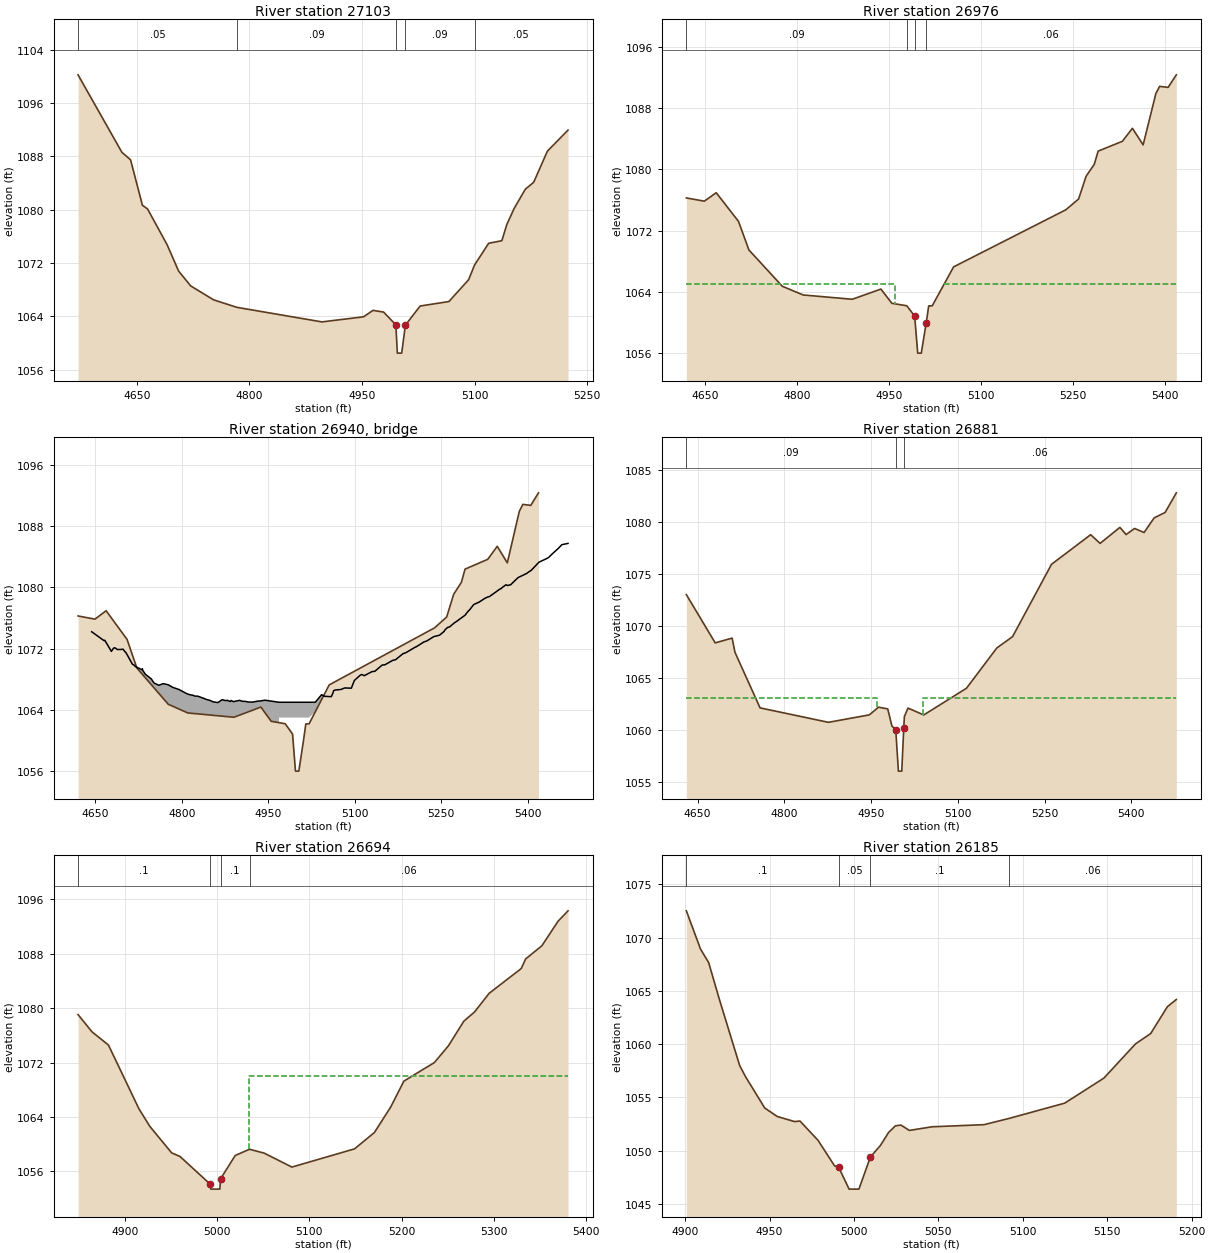
Type RM Length L Ch R = 1 ,27103   ,127,127,127
BEGIN DESCRIPTION:
XS 500
END DESCRIPTION:
XS GIS Cut Line= 6
      1156014.71       634424.96      1155809.07       634428.08
      1155654.84        634490.4      1155587.84       634541.81
      1155533.32       634580.75      1155452.31       634682.02
#Sta/Elev= 30
  4571.5 1100.21    4630 1088.59  4641.5 1087.48  4657.3 1080.67  4664.2  1080.1
  4690.3 1074.73  4705.6 1070.79  4721.7 1068.57  4752.3 1066.48  4783.3 1065.36
  4896.6 1063.18    4952 1063.94  4964.7 1064.91  4978.8 1064.65  4995.1 1062.74
  4997.1  1058.5  5002.9  1058.5  5007.8 1062.69  5027.5 1065.56  5065.8 1066.23
  5092.1  1069.5    5100  1071.7  5118.8 1074.96  5136.4 1075.35    5143 1077.77
  5152.8 1080.19  5167.7 1083.07  5178.8  1084.1  5197.1 1088.77  5224.6 1091.93
#Mann= 5 ,-1 , 0
  4571.5     .05       0  4783.3     .09       0  4995.1     .05       0
  5007.8     .09       0    5100     .05       0
Bank Sta=4995.1,5007.8
Exp/Cntr=0.3,0.1

Type RM Length L Ch R = 1 ,26976   ,95,95,95
BEGIN DESCRIPTION:
Depriest Road - US
END DESCRIPTION:
XS GIS Cut Line= 6
      1155858.92       634191.28      1155681.32       634325.26
      1155594.08       634389.13      1155477.23       634484.16
       1155411.9       634518.18      1155240.43       634691.37
#Sta/Elev= 30
    4620 1076.28  4649.3 1075.86  4668.7 1076.96    4705 1073.22    4722 1069.48
  4776.4 1064.74  4810.4  1063.6  4890.5 1063.04  4937.1 1064.37    4955 1062.51
  4979.3 1062.19  4992.1 1060.84  4997.1    1056  5002.9    1056    5011 1059.99
    5015 1062.17  5020.7 1062.18  5055.6 1067.27  5238.5 1074.73  5259.3 1076.14
  5271.5 1079.11  5284.8 1080.67  5291.2  1082.4  5330.6 1083.68    5347 1085.38
  5364.5 1083.22  5385.3 1089.94  5391.4 1090.86  5405.2 1090.73  5418.6 1092.37
#Mann= 4 ,-1 , 0
    4620     .09       0  4979.3     .06       0  4992.1     .04       0
    5011     .06       0
#XS Ineff= 2 , 0
       0    4960    1065    5040       0    1065
Permanent Ineff=
       F       F
Bank Sta=4992.1,5011
Exp/Cntr=0.3,0.1

Type RM Length L Ch R = 3 ,26940   ,,,
BEGIN DESCRIPTION:
Depriest Road
END DESCRIPTION:
Bridge Culvert--1,0,-1,-1, 0
Deck Dist Width WeirC Skew NumUp NumDn MinLoCord MaxHiCord MaxSubmerge Is_Ogee
25,31,2.6,0, 124, 124, , , 0.95, 0, 0,0,,
  4643.6  4644.3  4665.1  4666.4  4677.8  4681.4  4683.6  4688.4  4696.9  4698.1
  4701.3  4702.8  4714.4  4717.3  4719.1  4730.8  4731.6  4732.3  4736.9    4747
  4751.8  4760.1  4766.7  4768.4  4776.6  4784.2    4795  4807.3  4812.6  4820.1
  4821.7    4828  4837.2  4838.5  4841.1  4848.4  4851.9  4853.5  4862.4  4869.8
  4870.9  4875.4  4879.1  4883.6  4885.4  4889.3  4900.1  4905.5  4909.6  4915.1
  4922.2  4932.7    4934  4944.4  4945.1  4968.5  5031.5  5042.4    5047  5047.1
  5059.2  5061.9  5063.4  5066.7  5073.7  5076.5  5080.4  5082.6    5094  5099.2
  5108.8  5111.7  5116.6    5117  5129.8  5134.8  5147.4  5152.3  5165.6  5170.9
  5183.6  5188.9  5205.2  5206.8  5219.8  5224.8  5237.3  5246.6  5255.1  5255.8
  5260.7  5264.4  5273.4  5275.1  5291.1    5297  5297.6  5298.6  5306.2  5315.4
  5326.6    5328    5329  5333.6  5352.3  5353.3  5355.4  5362.1  5365.2  5370.3
    5383  5383.6  5398.2  5401.9  5405.8  5419.3  5434.2  5436.7  5441.4    5442
  5442.3  5453.8    5459  5469.8
 1074.21 1074.18 1073.05  1073.1 1071.65 1072.05 1072.13 1071.89 1071.91 1071.94
  1071.6 1071.53 1069.96 1069.86 1069.68 1069.25 1069.38 1069.15 1068.65 1068.05
 1067.52 1067.22 1067.41 1067.43 1067.28 1066.95 1066.67 1066.17 1066.01  1065.9
 1065.82 1065.79 1065.53 1065.51  1065.4 1065.25 1065.14 1065.07 1064.96 1065.33
 1065.33 1065.22 1065.25  1065.1 1065.23 1065.08 1065.25 1065.12 1065.12 1065.04
 1065.02 1065.16 1065.15 1065.27 1065.26    1065    1065 1065.99  1065.8 1065.78
 1065.73 1066.17 1066.53 1066.61 1066.65 1066.68 1066.81 1066.87 1066.84 1067.84
  1068.5 1068.63 1068.47  1068.5    1069 1069.05 1069.86  1069.9 1070.47 1070.57
 1071.35 1071.49 1072.22 1072.26 1072.88 1073.01 1073.59 1073.75 1074.27 1074.41
 1074.77 1074.85 1075.42 1075.49 1076.37 1076.94 1076.98 1077.03 1077.77 1078.08
 1078.63 1078.66 1078.71 1078.82 1079.83 1079.82 1079.98 1080.35 1080.26 1080.36
 1081.28 1081.31 1081.84 1082.05 1082.23  1083.3 1083.83 1083.96 1084.31 1084.35
 1084.38 1085.17 1085.59 1085.76
                                                                                
                                                                                
                                                                                
                                                                                
                                                                                
                                            1063    1063
                                                                                
                                                                                
                                                                                
                                                                                
                                                                                
                                                                                
                                
  4643.6  4644.3  4665.1  4666.4  4677.8  4681.4  4683.6  4688.4  4696.9  4698.1
  4701.3  4702.8  4714.4  4717.3  4719.1  4730.8  4731.6  4732.3  4736.9    4747
  4751.8  4760.1  4766.7  4768.4  4776.6  4784.2    4795  4807.3  4812.6  4820.1
  4821.7    4828  4837.2  4838.5  4841.1  4848.4  4851.9  4853.5  4862.4  4869.8
  4870.9  4875.4  4879.1  4883.6  4885.4  4889.3  4900.1  4905.5  4909.6  4915.1
  4922.2  4932.7    4934  4944.4  4945.1  4968.5  5031.5  5042.4    5047  5047.1
  5059.2  5061.9  5063.4  5066.7  5073.7  5076.5  5080.4  5082.6    5094  5099.2
  5108.8  5111.7  5116.6    5117  5129.8  5134.8  5147.4  5152.3  5165.6  5170.9
  5183.6  5188.9  5205.2  5206.8  5219.8  5224.8  5237.3  5246.6  5255.1  5255.8
  5260.7  5264.4  5273.4  5275.1  5291.1    5297  5297.6  5298.6  5306.2  5315.4
  5326.6    5328    5329  5333.6  5352.3  5353.3  5355.4  5362.1  5365.2  5370.3
    5383  5383.6  5398.2  5401.9  5405.8  5419.3  5434.2  5436.7  5441.4    5442
  5442.3  5453.8    5459  5469.8
 1074.21 1074.18 1073.05  1073.1 1071.65 1072.05 1072.13 1071.89 1071.91 1071.94
  1071.6 1071.53 1069.96 1069.86 1069.68 1069.25 1069.38 1069.15 1068.65 1068.05
 1067.52 1067.22 1067.41 1067.43 1067.28 1066.95 1066.67 1066.17 1066.01  1065.9
 1065.82 1065.79 1065.53 1065.51  1065.4 1065.25 1065.14 1065.07 1064.96 1065.33
 1065.33 1065.22 1065.25  1065.1 1065.23 1065.08 1065.25 1065.12 1065.12 1065.04
 1065.02 1065.16 1065.15 1065.27 1065.26    1065    1065 1065.99  1065.8 1065.78
 1065.73 1066.17 1066.53 1066.61 1066.65 1066.68 1066.81 1066.87 1066.84 1067.84
  1068.5 1068.63 1068.47  1068.5    1069 1069.05 1069.86  1069.9 1070.47 1070.57
 1071.35 1071.49 1072.22 1072.26 1072.88 1073.01 1073.59 1073.75 1074.27 1074.41
 1074.77 1074.85 1075.42 1075.49 1076.37 1076.94 1076.98 1077.03 1077.77 1078.08
 1078.63 1078.66 1078.71 1078.82 1079.83 1079.82 1079.98 1080.35 1080.26 1080.36
 1081.28 1081.31 1081.84 1082.05 1082.23  1083.3 1083.83 1083.96 1084.31 1084.35
 1084.38 1085.17 1085.59 1085.76
                                                                                
                                                                                
                                                                                
                                                                                
                                                                                
                                            1063    1063
                                                                                
                                                                                
                                                                                
                                                                                
                                                                                
                                                                                
                                
BR Coef=-1 , 0 , 0 ,, 0 ,,,0.8,-1,,0,
WSPro=,,,, 1 ,,,, 0 ,,,, 0 ,,,,-1 ,-1 ,-1 , 0 , 0 , 0 , 0 , 0
BC Design=,, 0 ,, 0 ,,,,,,

Type RM Length L Ch R = 1 ,26881   ,187,187,187
BEGIN DESCRIPTION:
Depriest Road - DS
END DESCRIPTION:
XS GIS Cut Line= 6
      1155865.04       634106.24      1155757.06       634163.17
      1155578.57       634319.76      1155511.58       634371.17
      1155457.05       634410.12       1155192.2       634617.32
#Sta/Elev= 30
  4630.4    1073  4680.3 1068.35  4709.6 1068.81  4714.5 1067.44  4757.9 1062.09
  4876.1  1060.7  4946.9 1061.42  4962.7 1062.16 4978.68 1061.99  4985.9 1060.34
  4992.5    1060  4997.1    1056  5002.9    1056  5006.4 1060.18 5007.42 1061.26
  5013.7 1062.07    5041 1061.41  5114.8 1063.98  5167.3 1067.86  5194.5 1068.95
  5261.9 1075.92  5329.6 1078.77  5345.8 1077.93  5380.1 1079.47  5390.8 1078.78
  5405.5 1079.37  5421.9 1078.98  5439.4 1080.39  5458.3 1080.91  5477.7  1082.8
#Mann= 3 ,-1 , 0
  4630.4     .09       0  4992.5     .04       0  5006.4     .06       0
#XS Ineff= 2 , 0
       0    4960    1063    5040       0    1063
Permanent Ineff=
       F       F
Bank Sta=4992.5,5006.4
Exp/Cntr=0.3,0.1

Type RM Length L Ch R = 1 ,26694   ,509,509,509
BEGIN DESCRIPTION:
Hunting_Crk_XS76
END DESCRIPTION:
XS GIS Cut Line= 6
      1155668.75        634054.8      1155627.29       634115.89
      1155454.94        634185.7      1155411.31       634220.61
       1155293.5       634264.24      1155217.14       634310.06
#Sta/Elev= 30
  4849.1 1079.05  4864.2 1076.52  4882.1 1074.57  4915.1 1065.21    4927 1062.61
  4950.6 1058.72  4959.7 1058.19  4991.7 1054.21  4993.1  1053.4  4997.1 1053.39
  5002.9 1053.39  5003.6 1054.89  5019.6 1058.34  5035.1 1059.25    5051 1058.68
    5081 1056.63    5149 1059.31  5170.5 1061.71  5188.2 1065.46  5202.5 1069.27
  5235.5 1071.99  5250.7 1074.44  5267.5 1078.08  5279.1 1079.43  5294.9 1082.17
  5329.7 1085.81  5334.5 1087.22  5352.1 1089.16  5369.7 1092.77  5380.5  1094.3
#Mann= 4 ,-1 , 0
  4849.1      .1       0  4991.7     .05       0  5003.6      .1       0
  5035.1     .06       0
#XS Ineff= 2 , 0
       0                    5035       0    1070
Permanent Ineff=
       F       F
Bank Sta=4991.7,5003.6
Exp/Cntr=0.3,0.1

Type RM Length L Ch R = 1 ,26185   ,496,496,496
BEGIN DESCRIPTION:
Hunting_Crk_XS75
END DESCRIPTION:
XS GIS Cut Line= 5
      1155282.59       633843.18      1155217.14         633865.
      1155175.69       633908.63      1155125.51        633971.9
      1155070.97        634030.8
#Sta/Elev= 30
  4900.7 1072.52  4909.1 1068.93  4913.9 1067.67  4920.3 1064.19  4932.3 1057.99
  4935.7 1056.97  4947.1 1054.02  4954.5 1053.22  4964.8 1052.74    4968 1052.79
  4978.7 1050.98  4988.5 1048.58  4990.9 1048.46  4997.1  1046.4  5002.9  1046.4
  5009.7 1049.41  5015.7 1050.51  5020.4  1051.7  5024.5 1052.34  5027.8 1052.41
  5032.8 1051.91  5046.2 1052.25    5077 1052.45  5091.7 1053.03  5124.8 1054.47
    5148 1056.82  5166.7 1060.03  5175.7    1061  5185.6 1063.52  5190.9  1064.2
#Mann= 4 ,-1 , 0
  4900.7      .1       0  4990.9     .05       0  5009.7      .1       0
  5091.7     .06       0
Bank Sta=4990.9,5009.7
Exp/Cntr=0.3,0.1

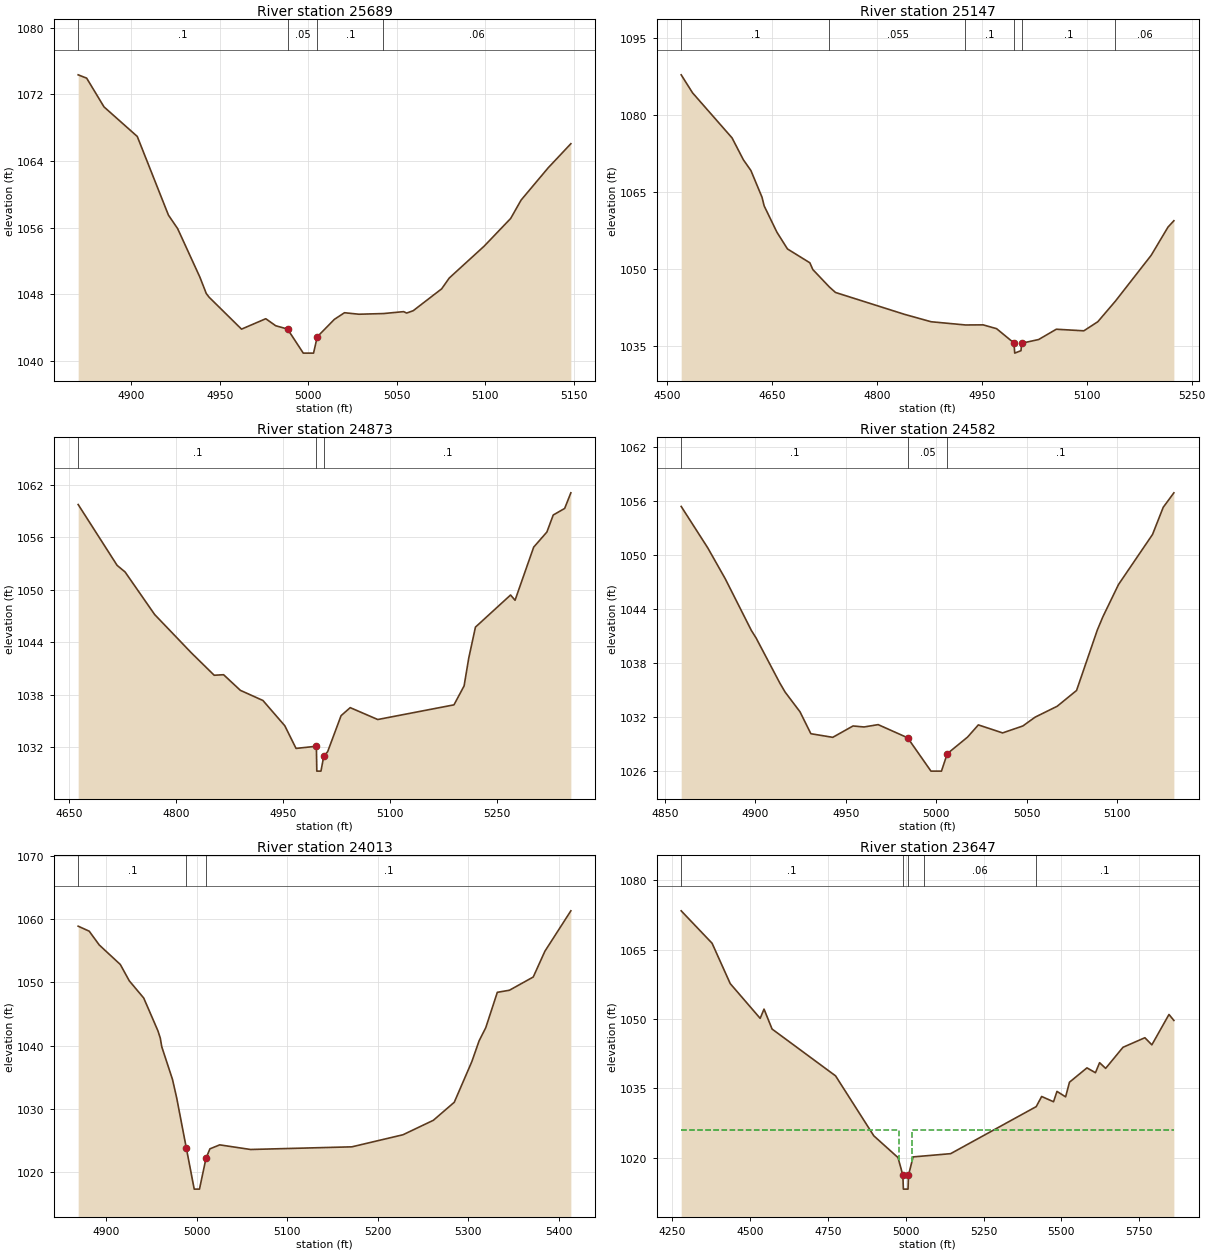
Type RM Length L Ch R = 1 ,25689   ,542,542,542
BEGIN DESCRIPTION:
Hunting_Crk_XS74
END DESCRIPTION:
XS GIS Cut Line= 2
      1155086.24       633443.93      1154850.62       633592.29
#Sta/Elev= 30
  4869.9 1074.35  4874.7 1073.95  4884.5  1070.5  4903.3 1066.95  4920.9 1057.51
  4926.1 1055.89  4938.7 1050.05  4942.3 1048.09  4943.9 1047.65  4962.2 1043.82
  4975.9 1045.07  4981.5 1044.23  4988.2 1043.83  4997.1 1040.94  5002.9 1040.94
    5005  1042.9  5014.7    1045  5020.4 1045.79  5028.5 1045.61  5042.4 1045.69
  5053.8 1045.92  5055.5 1045.75  5059.2 1046.03  5075.3 1048.66  5079.6 1049.96
  5099.3 1053.78  5114.3 1057.11  5120.2 1059.32  5135.5 1063.19  5148.3 1066.08
#Mann= 4 ,-1 , 0
  4869.9      .1       0  4988.2     .05       0    5005      .1       0
  5042.4     .06       0
Bank Sta=4988.2,5005
Exp/Cntr=0.3,0.1

Type RM Length L Ch R = 1 ,25147   ,274,274,274
BEGIN DESCRIPTION:
Hunting_Crk_XS72
END DESCRIPTION:
XS GIS Cut Line= 6
      1155190.96       632937.78      1155038.24       632950.87
      1154909.52       633022.87      1154710.99       633112.32
      1154625.91       633153.77      1154547.37       633199.59
#Sta/Elev= 30
  4520.4 1087.87  4536.7 1084.35  4593.1 1075.57  4609.3  1071.3    4620 1069.22
  4635.9 1064.01    4639 1062.31  4657.2 1057.19  4672.3 1053.92  4704.3 1051.22
  4708.5 1049.91  4732.2  1046.5  4740.9 1045.44  4839.6 1041.17  4877.5 1039.73
  4926.7  1039.1  4951.9 1039.12  4971.1 1038.38  4995.9  1035.6  4997.1 1033.61
    5006 1034.09    5007 1035.54  5031.2 1036.26  5056.5 1038.27  5095.8 1037.96
  5115.8 1039.73  5140.9 1043.74  5192.1 1052.69  5216.1 1058.18  5224.5 1059.42
#Mann= 6 ,-1 , 0
  4520.4      .1       0  4732.2    .055       0  4926.7      .1       0
  4995.9     .05       0    5007      .1       0  5140.9     .06       0
Bank Sta=4995.9,5007
Exp/Cntr=0.3,0.1

Type RM Length L Ch R = 1 ,24873   ,291,291,291
BEGIN DESCRIPTION:
Hunting_Crk_XS73
END DESCRIPTION:
XS GIS Cut Line= 6
      1154998.97       632787.25      1154800.44       632809.07
      1154671.72       632905.06      1154569.18       632998.87
      1154503.73       633079.59      1154466.64       633158.13
#Sta/Elev= 30
  4662.7 1059.77  4717.3  1052.8  4728.4 1052.05  4769.9 1047.17    4821 1042.81
  4853.3 1040.22  4866.5 1040.28    4890 1038.49  4921.6 1037.33  4952.3 1034.43
    4968 1031.84  4996.5 1032.09  4997.1 1029.24  5002.9 1029.24  5006.8 1030.93
  5012.3 1031.47  5031.1 1035.59  5043.9 1036.51  5082.5 1035.15  5189.3 1036.83
  5203.5    1039    5210 1042.18  5219.4 1045.73  5268.6 1049.41  5274.9 1048.81
    5301 1054.89  5319.5 1056.62  5328.4 1058.57  5344.4 1059.32  5353.1 1061.11
#Mann= 3 ,-1 , 0
  4662.7      .1       0  4996.5     .05       0  5006.8      .1       0
Bank Sta=4996.5,5006.8
Exp/Cntr=0.3,0.1

Type RM Length L Ch R = 1 ,24582   ,569,569,569
BEGIN DESCRIPTION:
Hunting_Crk_XS71
END DESCRIPTION:
XS GIS Cut Line= 4
        1154591.       632662.89      1154556.09       632713.07
      1154444.83       632798.16      1154390.28       632843.97
#Sta/Elev= 30
    4859  1055.4  4873.7  1050.8  4883.4 1047.36  4897.8 1041.64  4900.4 1040.81
  4913.6 1035.78  4916.5 1034.79  4924.7 1032.61  4930.7 1030.18  4942.8 1029.78
    4954 1031.04  4960.1 1030.93  4967.9 1031.19  4984.2 1029.73  4997.1 1026.03
  5002.9 1026.03  5006.1 1027.96  5017.3  1029.8  5023.3 1031.16  5036.7 1030.27
  5047.9 1031.04  5054.7 1032.02  5066.9 1033.23  5077.6 1034.98  5089.1  1041.7
  5092.2 1043.18  5100.8 1046.74  5119.6 1052.29  5125.5  1055.3  5131.4 1056.91
#Mann= 3 ,-1 , 0
    4859      .1       0  4984.2     .05       0  5006.1      .1       0
Bank Sta=4984.2,5006.1
Exp/Cntr=0.3,0.1

Type RM Length L Ch R = 1 ,24013   ,366,366,366
BEGIN DESCRIPTION:
XS 600
END DESCRIPTION:
XS GIS Cut Line= 5
      1154277.13       632222.31      1154225.78       632275.45
      1154187.08       632483.26      1154149.99       632654.84
      1154147.57        632738.7
#Sta/Elev= 30
  4868.8 1058.88    4881 1058.09  4892.1 1055.91  4915.4 1052.82  4925.3 1050.24
  4941.3 1047.51    4957 1042.32  4959.6 1041.17  4961.2 1039.82  4973.1 1034.63
  4977.7 1031.73 4988.42 1023.75  4997.1 1017.29  5002.9 1017.29  5010.1 1022.15
 5014.43 1023.66 5025.26 1024.29  5059.4 1023.56  5171.4 1023.98  5227.9 1025.89
  5261.5 1028.18  5284.6 1031.03    5304 1037.45  5312.1 1040.76  5319.4 1042.82
  5332.2 1048.42  5345.6 1048.75  5371.9 1050.84  5384.8 1054.92  5413.5 1061.31
#Mann= 3 ,-1 , 0
  4868.8      .1       0 4988.42     .05       0  5010.1      .1       0
Bank Sta=4988.42,5010.1
Exp/Cntr=0.5,0.3

Type RM Length L Ch R = 1 ,23647   ,64,64,64
BEGIN DESCRIPTION:
Hunting_Crk_XS68
END DESCRIPTION:
XS GIS Cut Line= 6
      1154246.29       631783.68      1154148.12       631923.31
       1154043.4       632097.84      1153919.04       632337.82
      1153705.24       632878.88      1153587.43       633214.86
#Sta/Elev= 30
  4278.9 1073.43  4378.2 1066.41  4436.4 1057.69  4532.6 1050.17    4545 1052.17
  4570.8 1047.86  4774.8 1037.73  4897.6 1024.76 4975.25 1020.06    4991 1016.23
  4992.5 1013.23  5007.5 1013.23    5009 1016.23 5023.77  1020.2  5144.4  1020.9
  5419.3 1031.08  5436.7 1033.27  5474.9 1032.13  5485.9 1034.37  5513.7 1033.19
  5526.1 1036.36  5582.2 1039.46  5609.5 1038.41  5622.8 1040.58  5642.2 1039.35
    5698 1043.91  5768.3 1045.98  5790.7 1044.44  5845.7 1051.01  5861.4 1049.72
#Mann= 5 ,-1 , 0
  4278.9      .1       0    4991     .05       0    5009      .1       0
  5058.9     .06       0  5419.3      .1       0
#XS Ineff= 2 , 0
       0    4980    1026    5020       0    1026
Permanent Ineff=
       F       F
Bank Sta=4991,5009
Exp/Cntr=0.5,0.3

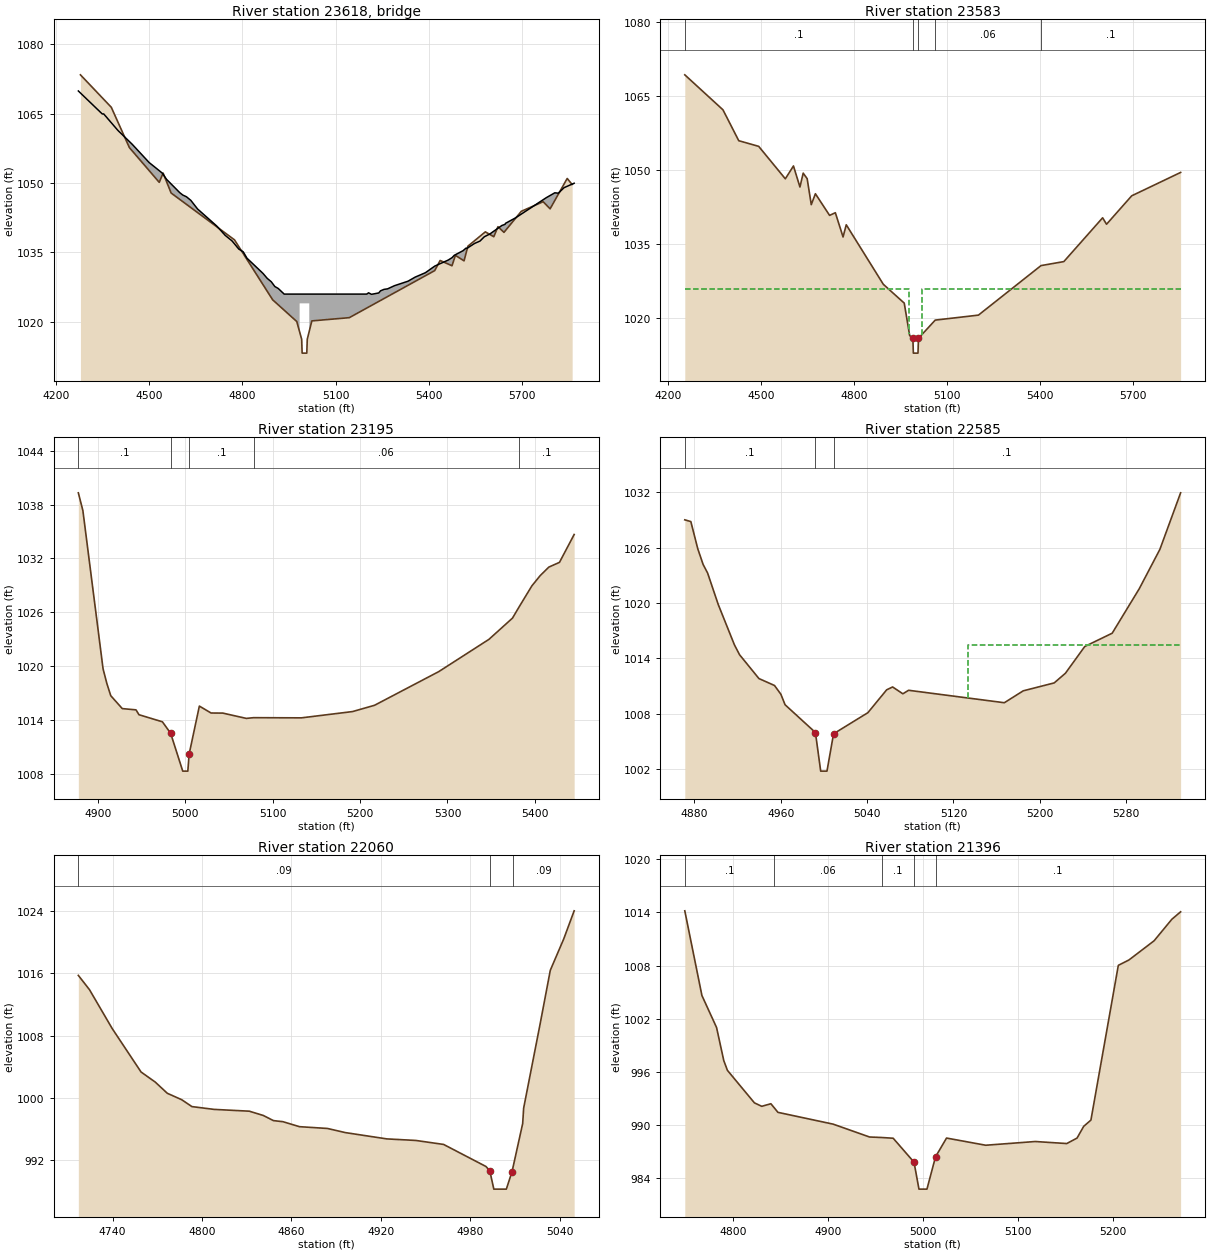
Type RM Length L Ch R = 3 ,23618   ,,,
BEGIN DESCRIPTION:
Hunting_Crk_XS67
Structure ID: Brooks Rd. SR-1715
Approximate Survey Structure
END DESCRIPTION:
Bridge Culvert--1,0,-1,-1, 0
Deck Dist Width WeirC Skew NumUp NumDn MinLoCord MaxHiCord MaxSubmerge Is_Ogee
15,28,3,0, 60, 60, , , , 0, 1,1,,
  4272.1    4349  4353.8  4399.7  4444.9    4500    4542    4556  4598.6    4608
  4620.2  4634.3  4656.1  4717.5  4745.2  4766.9  4788.7  4802.8    4815  4866.6
    4880    4893  4904.8  4915.5  4934.7  4984.5  4984.5  5015.5  5015.5  5200.4
  5206.4  5215.7  5239.1  5244.8    5256  5267.7  5289.8  5333.4  5356.2  5389.4
  5419.5  5462.6  5475.2  5482.2  5510.5  5520.1  5523.1  5547.9  5564.8  5578.9
  5596.9  5635.2  5645.6  5647.2  5679.7  5778.5  5805.8  5817.2  5835.6  5868.1
 1069.94 1064.97 1064.97 1061.39 1058.45 1054.46 1052.19 1050.83 1047.94 1047.44
 1047.05 1046.27  1044.4 1040.73 1038.68  1037.5 1035.73 1035.15 1033.76 1030.47
 1029.41 1028.68 1027.63 1027.22    1026    1026    1026    1026    1026    1026
 1026.28 1025.95 1026.25 1026.71 1027.02 1027.14 1027.82 1028.79 1029.67 1030.63
 1032.06 1033.36 1033.89 1034.39 1035.39 1035.95  1035.9 1036.97 1037.46  1038.4
 1039.01 1040.83 1041.09 1041.31  1042.5 1046.86 1047.91 1047.83 1049.02 1049.98
  993.23  993.23  993.23  993.23  993.23  993.23  993.23  993.23  993.23  993.23
  993.23  993.23  993.23  993.23  993.23  993.23  993.23  993.23  993.23  993.23
  993.23  993.23  993.23  993.23  993.23  993.23    1024    1024  993.23  993.23
  993.23  993.23  993.23  993.23  993.23  993.23  993.23  993.23  993.23  993.23
  993.23  993.23  993.23  993.23  993.23  993.23  993.23  993.23  993.23  993.23
  993.23  993.23  993.23  993.23  993.23  993.23  993.23  993.23  993.23  993.23
  4272.1    4349  4353.8  4399.7  4444.9    4500    4542    4556  4598.6    4608
  4620.2  4634.3  4656.1  4717.5  4745.2  4766.9  4788.7  4802.8    4815  4866.6
    4880    4893  4904.8  4915.5  4934.7  4984.5  4984.5  5015.5  5015.5  5200.4
  5206.4  5215.7  5239.1  5244.8    5256  5267.7  5289.8  5333.4  5356.2  5389.4
  5419.5  5462.6  5475.2  5482.2  5510.5  5520.1  5523.1  5547.9  5564.8  5578.9
  5596.9  5635.2  5645.6  5647.2  5679.7  5778.5  5805.8  5817.2  5835.6  5868.1
 1069.94 1064.97 1064.97 1061.39 1058.45 1054.46 1052.19 1050.83 1047.94 1047.44
 1047.05 1046.27  1044.4 1040.73 1038.68  1037.5 1035.73 1035.15 1033.76 1030.47
 1029.41 1028.68 1027.63 1027.22    1026    1026    1026    1026    1026    1026
 1026.28 1025.95 1026.25 1026.71 1027.02 1027.14 1027.82 1028.79 1029.67 1030.63
 1032.06 1033.36 1033.89 1034.39 1035.39 1035.95  1035.9 1036.97 1037.46  1038.4
 1039.01 1040.83 1041.09 1041.31  1042.5 1046.86 1047.91 1047.83 1049.02 1049.98
  993.23  993.23  993.23  993.23  993.23  993.23  993.23  993.23  993.23  993.23
  993.23  993.23  993.23  993.23  993.23  993.23  993.23  993.23  993.23  993.23
  993.23  993.23  993.23  993.23  993.23  993.23    1024    1024  993.23  993.23
  993.23  993.23  993.23  993.23  993.23  993.23  993.23  993.23  993.23  993.23
  993.23  993.23  993.23  993.23  993.23  993.23  993.23  993.23  993.23  993.23
  993.23  993.23  993.23  993.23  993.23  993.23  993.23  993.23  993.23  993.23
Abutment Skew #Up #Dn= , 2 , 2
  4984.5    4986
    1024  1017.7
  4984.5    4986
    1024 1017.17
Abutment Skew #Up #Dn= , 2 , 2
    5014  5015.5
 1018.99    1024
    5014  5015.5
 1017.53    1024
BR Coef= 1 , 1 , 0 ,1.25, 0 ,,,0.8,0,2,0,
WSPro=,,,, 1 ,,,, 0 ,,,, 0 ,,,,-1 ,-1 ,-1 , 0 , 0 , 0 , 0 , 0
BC Design=,, 0 ,, 0 ,,,,,,
BC HTab HWMax=1074.14

Type RM Length L Ch R = 1 ,23583   ,388,388,388
BEGIN DESCRIPTION:
Hunting_Crk_XS69
END DESCRIPTION:
XS GIS Cut Line= 6
      1154204.84       631750.95      1154023.76       632036.75
      1153803.41       632440.36      1153713.97       632667.26
      1153692.15       632750.16      1153539.43        633197.4
#Sta/Elev= 30
  4254.7 1069.29  4377.9 1062.21  4428.9 1055.96  4493.2 1054.82  4579.2 1048.25
  4605.5 1050.85  4626.4 1046.59  4636.9  1049.4  4649.7 1048.28    4663 1043.02
  4676.3 1045.23  4722.1 1040.85  4740.7 1041.39  4765.6 1036.48  4775.9 1038.95
  4895.5 1026.91  4963.1  1023.1  4980.6 1016.54    4991 1015.98  4992.5 1012.98
  5007.5 1012.98    5009 1015.98  5063.1 1019.66  5202.6 1020.67  5404.6 1030.69
  5478.3  1031.5  5603.5 1040.36  5616.2 1039.06  5697.4 1044.81  5855.3 1049.54
#Mann= 5 ,-1 , 0
  4254.7      .1       0    4991     .05       0    5009      .1       0
  5063.1     .06       0  5404.6      .1       0
#XS Ineff= 2 , 0
       0    4980    1026    5020       0    1026
Permanent Ineff=
       F       F
Bank Sta=4991,5009
Exp/Cntr=0.5,0.3

Type RM Length L Ch R = 1 ,23195   ,610,610,610
BEGIN DESCRIPTION:
Hunting_Crk_XS66
END DESCRIPTION:
XS GIS Cut Line= 6
      1153528.52       632224.38      1153504.52         632364.
      1153539.43       632553.81      1153580.88       632660.71
      1153580.88       632706.53      1153550.34        632769.8
#Sta/Elev= 30
  4877.6  1039.3  4882.8 1037.33  4905.9 1019.71  4910.2 1018.09  4914.7 1016.72
  4927.9 1015.28  4943.6 1015.14    4947  1014.6  4973.8 1013.81  4983.2 1012.54
  4997.1 1008.32  5002.9 1008.32  5004.4 1010.21  5016.1 1015.56  5029.5 1014.79
  5042.9 1014.78  5069.8 1014.19  5078.1 1014.27  5132.9 1014.25  5191.4 1014.95
  5216.6 1015.65  5290.1  1019.4  5347.5 1022.99  5374.4 1025.35  5381.5 1026.52
  5396.6 1028.94  5406.1 1030.08    5416 1031.03  5428.2 1031.56    5445 1034.66
#Mann= 5 ,-1 , 0
  4877.6      .1       0  4983.2     .05       0  5004.4      .1       0
  5078.1     .06       0  5381.5      .1       0
Bank Sta=4983.2,5004.4
Exp/Cntr=0.3,0.1

Type RM Length L Ch R = 1 ,22585   ,525,525,525
BEGIN DESCRIPTION:
Hunting_Crk_XS65
END DESCRIPTION:
XS GIS Cut Line= 6
      1152998.38       632510.18      1153057.28       632656.35
      1153122.73       632787.25      1153153.27       632809.07
      1153196.91       632817.79      1153264.54       632846.15
#Sta/Elev= 30
  4871.2 1029.02  4876.8 1028.83  4883.2 1025.89  4888.2 1024.17  4892.3 1023.26
  4902.2 1019.83  4917.1 1015.48  4921.9 1014.39  4939.9  1011.8  4954.3 1011.05
  4960.2  1010.1  4964.1 1008.96  4992.2 1005.95  4997.1 1001.76  5002.9 1001.76
    5009 1005.81  5040.8  1008.1  5058.2 1010.58  5063.7 1010.89  5073.2 1010.15
  5078.5 1010.53  5167.2 1009.18  5184.7 1010.47  5213.4 1011.33  5223.8 1012.38
  5241.7 1015.28  5267.1 1016.72  5292.2 1021.55  5311.3 1025.82  5330.5 1031.95
#Mann= 3 ,-1 , 0
  4871.2      .1       0  4992.2     .05       0    5009      .1       0
#XS Ineff= 2 , 0
       0                 5133.47       0 1015.48
Permanent Ineff=
       F       F
Bank Sta=4992.2,5009
Exp/Cntr=0.3,0.1

Type RM Length L Ch R = 1 ,22060   ,664,664,664
BEGIN DESCRIPTION:
Hunting_Crk_XS64
END DESCRIPTION:
XS GIS Cut Line= 6
      1152775.84       632359.64      1152747.48       632409.82
      1152703.85       632449.09       1152662.4       632466.54
      1152588.22       632486.18      1152527.13       632558.17
#Sta/Elev= 30
    4717 1015.73  4724.5 1013.89  4739.7 1008.91  4759.1 1003.32  4768.6 1002.03
  4776.7 1000.59  4786.4  999.76  4793.2  998.88  4808.1  998.52  4831.7  998.29
  4841.1  997.74  4847.9  997.08  4854.3  996.94 4865.39   996.3  4884.2  996.07
 4896.13  995.54 4924.01  994.73  4943.5  994.53  4962.1  994.02  4990.5  991.19
  4993.1  990.63  4995.8  988.28  5004.2  988.28 5008.04  990.54 5015.17  996.71
  5015.8  998.67  5026.8 1009.43  5033.7 1016.39  5042.7 1020.41  5049.7 1024.02
#Mann= 3 ,-1 , 0
    4717     .09       0  4993.1     .05       0  5008.8     .09       0
Bank Sta=4993.1,5008.04
Exp/Cntr=0.3,0.1

Type RM Length L Ch R = 1 ,21396   ,495,495,495
BEGIN DESCRIPTION:
Hunting_Crk_XS63
END DESCRIPTION:
XS GIS Cut Line= 6
      1152926.38       631938.58      1152832.57       631938.58
      1152710.39       631925.49      1152509.68       631927.67
      1152450.78       631953.85       1152411.5       631951.67
#Sta/Elev= 30
  4749.6 1014.18  4767.6 1004.63    4783 1001.02  4790.6  997.28  4794.4  996.19
  4822.8  992.52  4830.5  992.13  4840.1  992.42  4843.3  992.01  4847.5  991.45
  4905.6  990.12  4943.8  988.67  4956.9  988.61  4968.7  988.53  4990.6  985.83
  4995.8  982.79  5004.2  982.79  5013.2  986.43  5024.8  988.55    5066  987.74
  5118.1  988.16  5151.2  987.93    5162  988.55    5169  989.87  5176.6  990.58
  5205.4 1008.03  5216.6 1008.64    5243  1010.8  5261.7 1013.23  5270.9 1014.07
#Mann= 5 ,-1 , 0
  4749.6      .1       0  4843.3     .06       0  4956.9      .1       0
  4990.6     .05       0  5013.2      .1       0
Bank Sta=4990.6,5013.2
Exp/Cntr=0.3,0.1

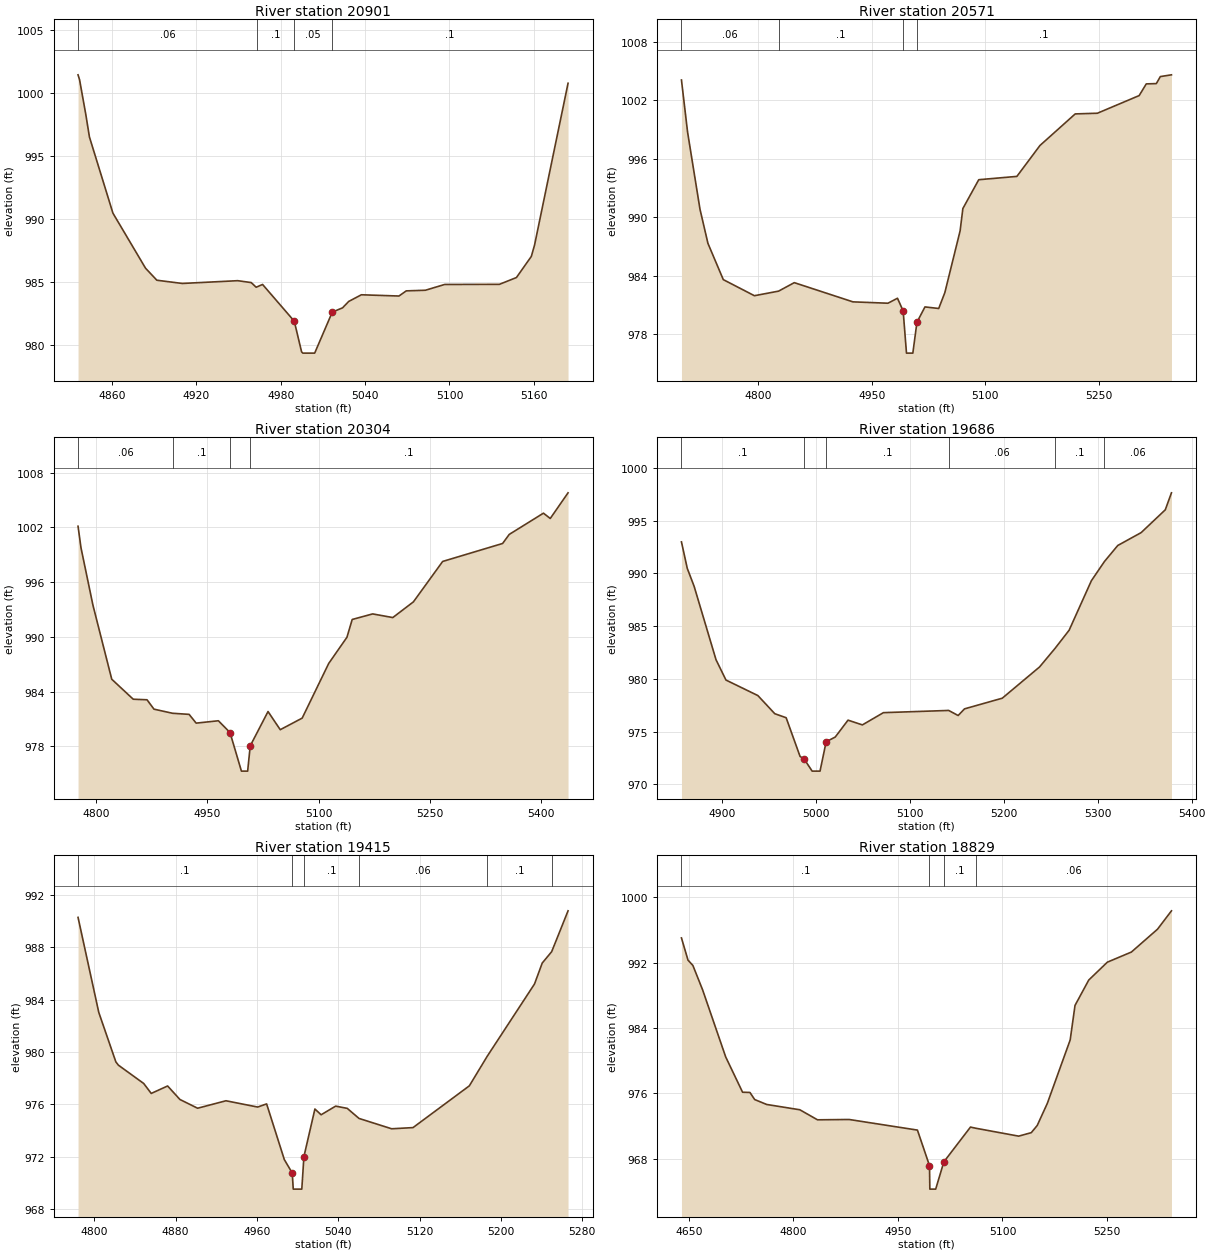
Type RM Length L Ch R = 1 ,20901   ,330,330,330
BEGIN DESCRIPTION:
Hunting_Crk_XS62
END DESCRIPTION:
XS GIS Cut Line= 5
      1152782.39       631406.25      1152730.03        631423.7
      1152658.03       631443.34       1152590.4       631497.88
      1152490.05       631582.96
#Sta/Elev= 30
    4836 1001.46  4837.1 1001.06  4841.5  998.32  4844.1  996.52  4860.8  990.46
    4884  986.08    4892  985.13  4893.9   985.1  4910.1  984.87  4949.5  985.09
  4959.1  984.94  4962.6  984.57 4967.17  984.79  4989.7  981.87  4994.9  979.43
  4995.8  979.33  5004.2  979.33  5016.7  982.59    5024  982.93  5028.4  983.44
  5037.4  983.97  5064.1  983.87  5069.3  984.28  5082.9  984.33  5096.6  984.79
  5135.5   984.8  5147.6  985.34  5158.2  987.02  5160.5  987.93  5184.3 1000.79
#Mann= 4 ,-1 , 0
    4836     .06       0    4963      .1       0  4989.7     .05       0
  5016.7      .1       0
Bank Sta=4989.7,5016.7
Exp/Cntr=0.3,0.1

Type RM Length L Ch R = 1 ,20571   ,267,267,267
BEGIN DESCRIPTION:
Hunting_Crk_XS60
END DESCRIPTION:
XS GIS Cut Line= 6
 1152779.9358935  631273.8522782      1152590.07       631273.68
      1152453.65       631264.81       1152423.1       631266.99
      1152388.83       631274.35 1152150.6366417   631366.459362
#Sta/Elev= 30
  4698.4 1004.07  4706.5  998.72  4722.9  990.81  4733.4  987.31  4753.7  983.59
  4794.8  981.94  4826.8  982.41  4847.5  983.28    4925  981.31  4971.3  981.17
  4983.9  981.68  4991.4  980.38  4995.8  976.05  5004.2  976.05  5009.6  979.21
  5020.2  980.79  5038.4  980.63  5046.5  982.26  5066.7   988.6  5070.3  990.88
  5091.3  993.84  5141.7  994.18  5172.2  997.35  5218.8 1000.59  5248.1 1000.66
  5303.3 1002.47  5312.7 1003.67    5326  1003.7  5331.3 1004.42    5346  1004.6
#Mann= 4 ,-1 , 0
  4698.4     .06       0  4826.8      .1       0  4991.4     .05       0
  5009.6      .1       0
Bank Sta=4991.4,5009.6
Exp/Cntr=0.3,0.1

Type RM Length L Ch R = 1 ,20304   ,618,618,618
BEGIN DESCRIPTION:
Hunting_Crk_XS59
END DESCRIPTION:
XS GIS Cut Line= 6
      1152802.02       631172.81      1152553.31       631050.64
      1152518.41       631046.27      1152452.96       631052.82
      1152380.96       631076.82      1152195.52       631168.45
#Sta/Elev= 30
  4775.3 1002.12  4779.3  999.75  4795.4  993.47  4820.8  985.35  4849.8  983.16
  4868.4   983.1  4877.8  982.07  4902.9  981.62  4925.2   981.5  4934.7  980.54
  4964.7   980.8  4980.4  979.51  4995.8  975.28  5004.2  975.28  5007.7  978.05
  5031.7  981.81  5048.2  979.82  5077.8  981.09  5113.6  987.08  5138.2  989.95
  5145.3   991.9  5172.9  992.51  5200.1  992.11  5227.9  993.83  5267.4  998.26
  5348.3 1000.23  5357.2 1001.22  5403.4 1003.55  5412.6 1002.97  5436.6 1005.78
#Mann= 4 ,-1 , 0
  4775.3     .06       0  4902.9      .1       0  4980.4     .05       0
  5007.7      .1       0
Bank Sta=4980.4,5007.7
Exp/Cntr=0.3,0.1

Type RM Length L Ch R = 1 ,19686   ,271,271,271
BEGIN DESCRIPTION:
Hunting_Crk_XS57
END DESCRIPTION:
XS GIS Cut Line= 6
      1152795.48       630509.58       1152721.3       630509.58
      1152690.76       630511.76      1152610.04       630546.67
      1152500.95       630633.94      1152313.33       630660.12
#Sta/Elev= 30
  4856.6  992.98  4862.8  990.47  4870.1  988.77  4893.4  981.82    4904  979.89
    4938  978.42    4956   976.7  4968.1  976.32  4982.9  972.66  4987.4  972.39
  4995.8  971.26  5004.2  971.26  5010.7  974.04  5020.4  974.49    5034  976.09
  5049.3  975.64  5071.7   976.8  5141.2  977.01  5151.3  976.53  5158.1  977.16
  5198.3  978.17    5238  981.13  5254.5  982.89  5269.5  984.61  5293.2   989.3
  5307.1  991.12  5321.3  992.64  5346.2  993.86  5371.9  996.02  5378.5  997.63
#Mann= 6 ,-1 , 0
  4856.6      .1       0  4987.4     .05       0  5010.7      .1       0
  5141.2     .06       0  5254.5      .1       0  5307.1     .06       0
Bank Sta=4987.4,5010.7
Exp/Cntr=0.3,0.1

Type RM Length L Ch R = 1 ,19415   ,586,586,586
BEGIN DESCRIPTION:
Hunting_Crk_XS55
END DESCRIPTION:
XS GIS Cut Line= 5
      1152784.57       630380.86      1152738.76       630378.68
      1152603.49        630352.5      1152548.95       630356.86
      1152319.87       630439.77
#Sta/Elev= 30
  4784.1  990.28  4804.5  983.02  4821.3  979.24  4823.8  978.99  4848.7  977.59
  4856.1  976.83  4872.2   977.4  4884.3  976.37  4901.7   975.7  4929.6  976.27
  4960.8  975.79  4969.6  976.03    4987  971.78  4994.8  970.75  4995.8  969.52
  5004.2  969.52  5006.3  972.01  5017.1  975.64  5023.2   975.2  5037.5  975.86
  5048.9  975.69  5060.5  974.92  5092.6  974.13  5113.6  974.22    5169  977.41
  5186.6  979.67  5233.1  985.19  5240.7  986.79    5250  987.66  5266.1  990.78
#Mann= 6 ,-1 , 0
  4784.1      .1       0  4994.8     .05       0  5006.3      .1       0
  5060.5     .06       0  5186.6      .1       0    5250     .06       0
Bank Sta=4994.8,5006.3
Exp/Cntr=0.3,0.1

Type RM Length L Ch R = 1 ,18829   ,643,643,643
BEGIN DESCRIPTION:
Hunting_Crk_XS53
END DESCRIPTION:
XS GIS Cut Line= 6
      1152850.02       629896.53      1152695.12        629887.8
      1152511.86        629852.9       1152352.6       629903.07
      1152263.15       629957.62      1152175.88       629975.07
#Sta/Elev= 30
  4639.4  995.02  4648.8   992.3  4655.8  991.65  4669.8  988.65  4702.9  980.44
  4727.1  976.12  4737.7  976.09  4744.5  975.22  4761.7  974.62  4809.3  973.97
  4834.6  972.74    4880  972.78    4978  971.48  4995.3  967.13  4995.8  964.25
  5004.2  964.25  5015.9  967.59  5054.1  971.85  5061.6  971.71  5123.3  970.74
  5141.4  971.17  5149.9  972.05  5164.4  974.76  5197.2  982.53  5204.1  986.75
  5223.8  989.86  5250.5  992.05    5285  993.29  5322.5  996.09  5342.5  998.34
#Mann= 4 ,-1 , 0
  4639.4      .1       0  4995.3     .05       0  5015.9      .1       0
  5061.6     .06       0
Bank Sta=4995.3,5015.9
Exp/Cntr=0.3,0.1