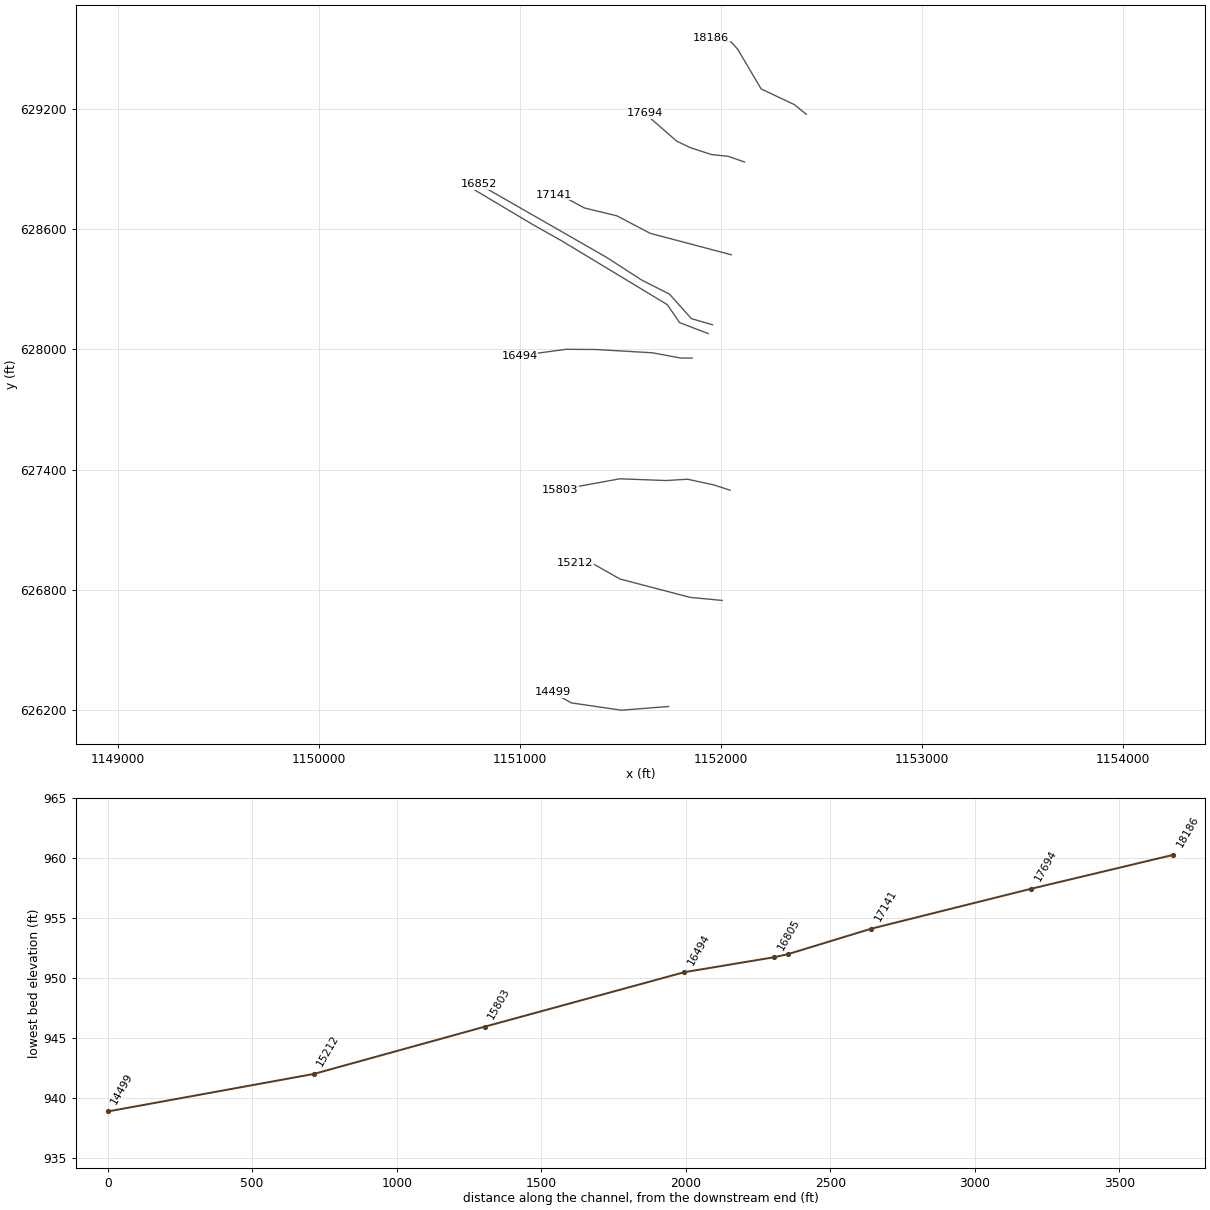
HEC-RAS study lds_hunting_crk.prj: Hunting Creek Limited Detail Study

--- lds_hunting_crk.g01 (geometry) --- (continued)

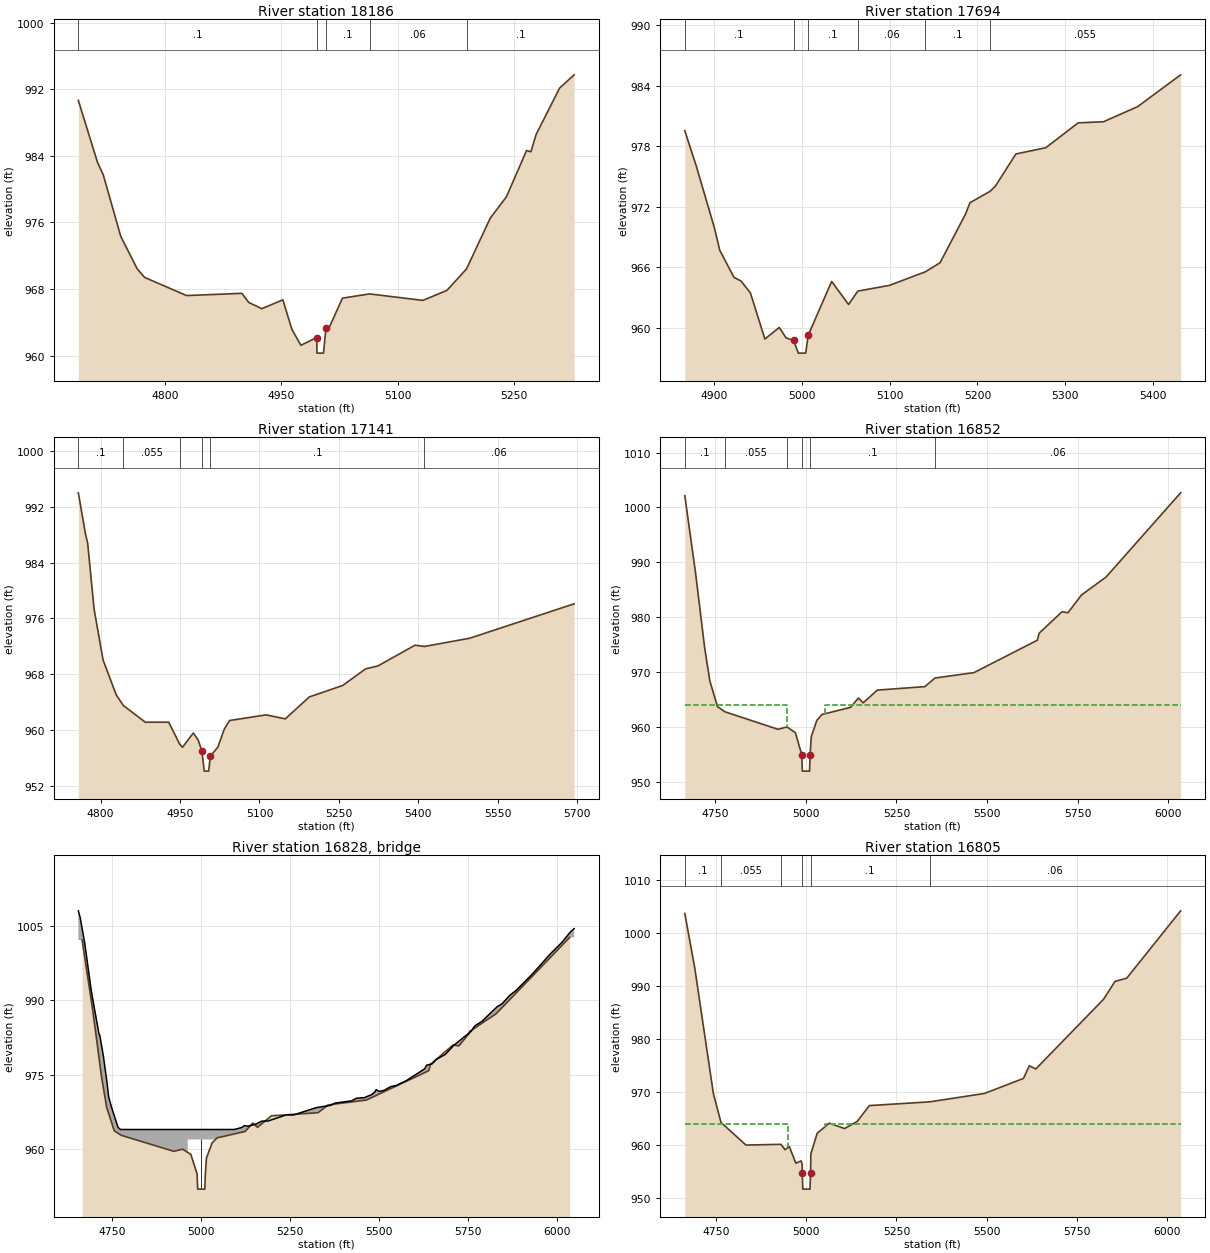
Type RM Length L Ch R = 1 ,18186   ,492,492,492
BEGIN DESCRIPTION:
Hunting_Crk_XS52
END DESCRIPTION:
XS GIS Cut Line= 6
      1152424.59       629172.21      1152365.69       629220.21
      1152199.88       629298.75      1152084.25        629495.1
      1152051.53       629532.19      1151951.17       629551.82
#Sta/Elev= 30
  4687.9  990.68  4712.5  983.27  4720.1  981.72  4742.6  974.34  4763.8  970.43
  4773.5  969.39  4827.6  967.21  4898.9  967.48  4907.7  966.39  4924.6  965.63
  4951.8   966.7  4963.4  963.16    4975  961.23  4995.4  962.16  4995.8  960.29
  5004.2  960.29  5007.4  963.28  5012.1  963.48  5028.7   966.9  5063.7  967.41
  5132.4  966.63  5163.4  967.83  5188.8  970.42  5219.3  976.51  5240.3   979.1
  5266.2  984.65  5271.8   984.5  5278.6  986.59  5308.9  992.17  5327.6  993.75
#Mann= 5 ,-1 , 0
  4687.9      .1       0  4995.4     .05       0  5007.4      .1       0
  5063.7     .06       0  5188.8      .1       0
Bank Sta=4995.4,5007.4
Exp/Cntr=0.3,0.1

Type RM Length L Ch R = 1 ,17694   ,553,553,553
BEGIN DESCRIPTION:
Hunting_Crk_XS51
END DESCRIPTION:
XS GIS Cut Line= 6
      1152116.98       628934.41      1152036.26       628962.77
      1151953.35        628971.5      1151846.45       629006.41
      1151778.82       629039.13      1151621.74       629176.58
#Sta/Elev= 30
  4866.4  979.55  4879.5  976.04  4900.4  969.83  4906.2  967.69  4922.4  964.99
  4930.5  964.62  4941.2  963.44  4957.7  958.86  4974.1  960.01  4981.8  958.98
  4990.5  958.72  4995.8  957.46  5004.2  957.46  5007.1  959.24  5033.8  964.58
  5053.1  962.29  5063.6  963.62  5099.7  964.19  5140.7  965.54  5157.4  966.44
  5186.3  971.25  5191.5   972.4  5214.4  973.53  5220.5  974.05  5243.8  977.24
  5277.9  977.86  5314.8  980.33  5343.7  980.44  5382.6  981.94  5431.6   985.1
#Mann= 6 ,-1 , 0
  4866.4      .1       0  4990.5     .05       0  5007.1      .1       0
  5063.6     .06       0  5140.7      .1       0  5214.4    .055       0
Bank Sta=4990.5,5007.1
Exp/Cntr=0.3,0.1

Type RM Length L Ch R = 1 ,17141   ,289,289,289
BEGIN DESCRIPTION:
Hunting_Crk_XS49
END DESCRIPTION:
XS GIS Cut Line= 6
      1152051.53        628471.9      1151647.92        628578.8
      1151482.11       628666.06      1151320.67       628705.33
      1151239.95       628748.97      1151170.13       628770.78
#Sta/Elev= 30
  4758.1     994  4771.7  988.05  4775.7  986.81  4787.8  977.36  4804.8  970.06
  4829.6  965.06  4843.2  963.52  4884.6  961.14  4928.7  961.14  4949.4     958
  4954.7  957.55  4975.2  959.59  4984.4  958.58  4991.4  956.98  4995.8  954.13
  5004.2  954.13  5007.2  956.26  5021.6  957.58  5033.7  960.16  5043.6  961.38
  5112.6  962.19  5148.8  961.62  5194.2  964.76  5257.1   966.4  5300.6  968.79
  5323.4  969.19  5393.6  972.17  5411.4  971.99    5497  973.17  5694.1   978.1
#Mann= 6 ,-1 , 0
  4758.1      .1       0  4843.2    .055       0  4949.4      .1       0
  4991.4     .05       0  5007.2      .1       0  5411.4     .06       0
Bank Sta=4991.4,5007.2
Exp/Cntr=0.5,0.3

Type RM Length L Ch R = 1 ,16852   ,47,47,47
BEGIN DESCRIPTION:
Hunting_Crk_XS46
END DESCRIPTION:
XS GIS Cut Line= 6
      1151957.72       628122.83        1151853.       628153.37
      1151743.91       628275.54      1151606.47       628345.36
      1151427.57       628460.99      1150797.07       628823.15
#Sta/Elev= 30
  4665.5 1002.15  4695.1  988.13  4720.4  974.43  4734.6  968.43  4755.8  963.74
  4775.7  962.82  4922.9  959.61  4947.7  960.04  4970.8     959  4988.5     955
    4990     952    5010     952  5011.5     955  5014.7  958.25  5030.2  961.25
  5044.4  962.31  5123.3  963.61  5144.9  965.31    5158  964.43  5197.1  966.75
  5328.2  967.38  5356.4  968.95  5463.9  969.93    5639  975.83  5643.8   977.1
  5707.3  981.02  5723.4  980.82  5760.8  984.06  5828.5  987.32  6034.6 1002.66
#Mann= 6 ,-1 , 0
  4665.5      .1       0  4775.7    .055       0  4947.7      .1       0
  4988.5     .05       0  5011.5      .1       0  5356.4     .06       0
#XS Ineff= 2 , 0
       0  4948.5     964  5051.5       0     964
Permanent Ineff=
       F       F
Bank Sta=4988.5,5011.5
Exp/Cntr=0.5,0.3

Type RM Length L Ch R = 3 ,16828   ,,,
BEGIN DESCRIPTION:
Hunting_Crk_XS45
Structure ID: Lebanon Church Rd. SR-1706 #2
Approximate Survey Structure
END DESCRIPTION:
Bridge Culvert--1,0,-1,-1, 0
Deck Dist Width WeirC Skew NumUp NumDn MinLoCord MaxHiCord MaxSubmerge Is_Ogee
13.5,21,3,0, 60, 60, , , , 0, 1,1,,
  4654.9    4660  4672.9  4691.1  4693.7    4713    4715  4725.4  4735.4    4740
  4748.2  4766.3  4773.2    4962    4962    5038    5038  5092.3  5113.5  5121.7
  5130.7  5152.3  5169.7  5187.9  5239.6  5259.2  5323.1  5363.6  5376.1  5422.3
  5436.2  5457.9  5477.7  5487.6  5491.4  5499.3    5514  5532.3  5547.3  5575.8
  5627.8  5632.6  5648.3  5660.1  5685.4  5709.3  5751.6  5756.2  5757.6  5768.6
  5788.5  5830.9  5844.8  5866.9  5882.8  5929.1  5981.3  6012.1  6036.7  6047.2
 1008.01 1006.68 1001.49  992.01  990.92  983.19  983.03  978.71  973.44   970.6
  968.46  964.45     964     964     964     964     964     964  964.39  964.79
  964.67  965.04  965.68  965.71  966.96  966.93   968.4  968.87  969.32  969.77
   970.3   970.4     971  971.56  972.03  971.65   971.9  972.64  972.85  973.83
  976.23  976.94  977.21   978.1  979.12  980.94   983.4  983.92  983.75  984.88
  985.77  988.71   989.3  991.03   991.9  995.22  999.42  1001.6 1003.76 1004.43
     932     932     932     932     932     932     932     932     932     932
     932     932     932     932     962     962     932     932     932     932
     932     932     932     932     932     932     932     932     932     932
     932     932     932     932     932     932     932     932     932     932
     932     932     932     932     932     932     932     932     932     932
     932     932     932     932     932     932     932     932     932     932
  4654.9    4660  4672.9  4691.1  4693.7    4713    4715  4725.4  4735.4    4740
  4748.2  4766.3  4773.2    4962    4962    5038    5038  5092.3  5113.5  5121.7
  5130.7  5152.3  5169.7  5187.9  5239.6  5259.2  5323.1  5363.6  5376.1  5422.3
  5436.2  5457.9  5477.7  5487.6  5491.4  5499.3    5514  5532.3  5547.3  5575.8
  5627.8  5632.6  5648.3  5660.1  5685.4  5709.3  5751.6  5756.2  5757.6  5768.6
  5788.5  5830.9  5844.8  5866.9  5882.8  5929.1  5981.3  6012.1  6036.7  6047.2
 1008.01 1006.68 1001.49  992.01  990.92  983.19  983.03  978.71  973.44   970.6
  968.46  964.45     964     964     964     964     964     964  964.39  964.79
  964.67  965.04  965.68  965.71  966.96  966.93   968.4  968.87  969.32  969.77
   970.3   970.4     971  971.56  972.03  971.65   971.9  972.64  972.85  973.83
  976.23  976.94  977.21   978.1  979.12  980.94   983.4  983.92  983.75  984.88
  985.77  988.71   989.3  991.03   991.9  995.22  999.42  1001.6 1003.76 1004.43
     932     932     932     932     932     932     932     932     932     932
     932     932     932     932     962     962     932     932     932     932
     932     932     932     932     932     932     932     932     932     932
     932     932     932     932     932     932     932     932     932     932
     932     932     932     932     932     932     932     932     932     932
     932     932     932     932     932     932     932     932     932     932
Pier Skew, UpSta & Num, DnSta & Num=  ,5000, 2 ,5000, 2 , 0 , 0 , 0 ,0,0
     1.5     1.5
     952     962
     1.5     1.5
  951.75     962
Abutment Skew #Up #Dn= , 2 , 2
    4962  4963.5
     962  958.85
    4962  4963.5
     962  957.85
Abutment Skew #Up #Dn= , 2 , 2
  5036.5    5038
  961.78     962
  5036.5    5038
  962.75     962
BR Coef= 1 , 1 , 0 ,1.25, 0 ,,,0.8,0,2,0,
WSPro=,,,, 1 ,,,, 0 ,,,, 0 ,,,,-1 ,-1 ,-1 , 0 , 0 , 0 , 0 , 0
BC Design=,, 0 ,, 0 ,,,,,,
BC HTab HWMax=1002.73

Type RM Length L Ch R = 1 ,16805   ,311,311,311
BEGIN DESCRIPTION:
Hunting_Crk_XS47
END DESCRIPTION:
XS GIS Cut Line= 6
       1151935.9       628079.19      1151794.09       628133.74
        1151733.       628223.18      1151207.22       628541.71
      1151067.59       628620.25      1150775.25       628794.78
#Sta/Elev= 30
  4662.6 1003.73  4690.2  993.48  4741.9  969.78    4763  964.33  4832.3  960.06
  4929.6   960.2  4940.8  959.18  4952.6  959.79  4970.7  956.64  4985.4  957.07
  4988.4  956.44  4988.5  954.75    4990  951.75    5010  951.75  5011.5  954.75
  5012.4  958.43    5030  962.29  5063.7  964.19    5106  963.17  5141.4  964.54
  5174.6   967.5  5342.4  968.21  5494.2  969.79  5602.4  972.63  5618.5  975.01
  5636.5  974.41  5824.7  987.56  5856.4  990.93  5888.9  991.53  6038.4 1004.23
#Mann= 6 ,-1 , 0
  4662.6      .1       0    4763    .055       0  4929.6      .1       0
  4988.5     .05       0  5011.5      .1       0  5342.4     .06       0
#XS Ineff= 2 , 0
       0  4949.5     964  5050.5       0     964
Permanent Ineff=
       F       F
Bank Sta=4988.5,5011.5
Exp/Cntr=0.5,0.3

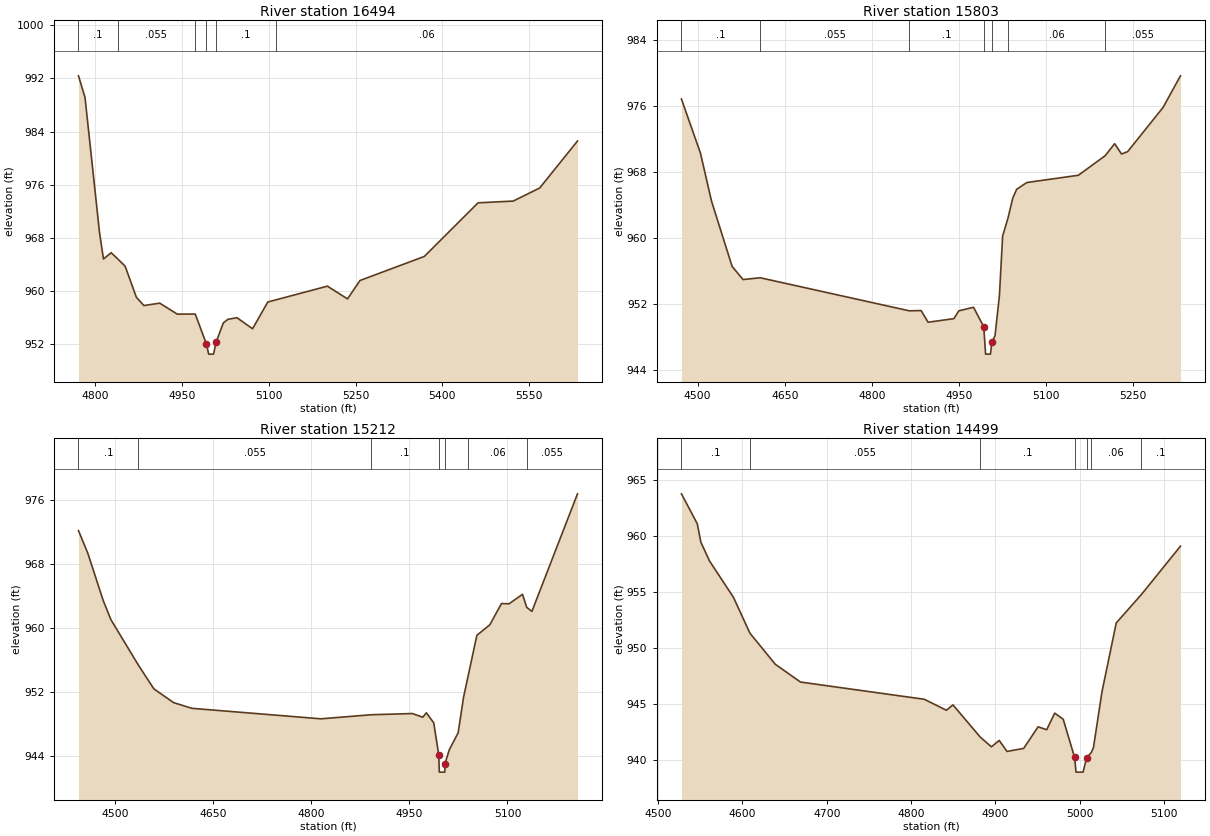
Type RM Length L Ch R = 1 ,16494   ,691,691,691
BEGIN DESCRIPTION:
Hunting_Crk_XS48
END DESCRIPTION:
XS GIS Cut Line= 6
 1151856.4600833  627956.8513087      1151800.27       627956.97
      1151658.46       627983.15      1151377.48       627999.52
      1151230.15       628000.57 1150998.4036423  627969.1861165
#Sta/Elev= 30
  4770.6  992.38  4781.9  989.11    4807  968.79  4813.8  964.82  4827.1  965.76
  4838.2  964.85  4851.3  963.73  4870.7  959.06  4883.7  957.81  4911.1  958.17
  4941.5  956.52  4972.6  956.53    4992  951.99  4995.8   950.5  5004.2   950.5
  5008.6   952.3  5021.2  955.21 5029.08  955.74 5044.59  955.98  5071.7  954.32
    5098  958.34  5111.4  958.65  5201.1  960.73  5235.9  958.81  5257.5  961.58
  5368.8   965.2  5461.7  973.27  5522.5  973.53  5568.3   975.5  5633.7  982.57
#Mann= 6 ,-1 , 0
  4770.6      .1       0  4838.2    .055       0  4972.6      .1       0
    4992     .05       0  5008.6      .1       0  5111.4     .06       0
Bank Sta=4992,5008.6
Exp/Cntr=0.3,0.1

Type RM Length L Ch R = 1 ,15803   ,591,591,591
BEGIN DESCRIPTION:
Hunting_Crk_XS43
END DESCRIPTION:
XS GIS Cut Line= 6
      1152044.98       627298.15      1151964.26       627324.33
      1151833.36        627352.7      1151726.46       627346.15
      1151497.38       627354.88      1151198.49       627300.34
#Sta/Elev= 30
  4472.3  976.81    4505  970.27    4524  964.47  4559.5  956.56  4578.4  954.97
  4607.8  955.19  4864.4  951.19  4884.8  951.22  4896.8  949.81  4941.2  950.24
  4949.8  951.19    4975  951.62  4992.6  949.26  4995.8  945.95  5004.2  945.95
  5006.6  947.43    5012  948.17  5019.6  953.05  5025.1  960.23  5034.4  962.42
  5042.6  964.84  5049.3  965.89  5066.7  966.71  5155.5  967.59  5201.7  969.96
  5217.9  971.41  5229.8  970.16  5240.3  970.45  5301.2  975.79  5331.2  979.62
#Mann= 7 ,-1 , 0
  4472.3      .1       0  4607.8    .055       0  4864.4      .1       0
  4992.6     .05       0  5006.6      .1       0  5034.4     .06       0
  5201.7    .055       0
Bank Sta=4992.6,5006.6
Exp/Cntr=0.3,0.1

Type RM Length L Ch R = 1 ,15212   ,713,713,713
BEGIN DESCRIPTION:
Hunting_Crk_XS41
END DESCRIPTION:
XS GIS Cut Line= 5
      1152005.71       626748.37      1151846.45       626763.64
      1151497.38       626855.27      1151370.85       626927.27
      1151274.85       626933.81
#Sta/Elev= 30
  4444.3  972.14  4458.6  969.31    4482  963.44  4493.8  961.04  4535.7  955.38
  4559.5   952.4  4589.7  950.68  4617.7  949.97  4814.8  948.66  4891.8  949.17
  4954.6  949.32  4970.5  948.86    4976  949.41  4987.3  948.15  4994.9  944.18
  4995.8  942.01  5004.2  942.01  5004.3  943.03  5011.1  944.81  5024.6  946.92
  5032.8  951.33  5039.8  953.99  5053.2  959.08    5073  960.39  5090.8  963.04
  5102.4  963.01  5122.9  964.19  5129.4  962.57  5137.3  962.06    5207  976.73
#Mann= 7 ,-1 , 0
  4444.3      .1       0  4535.7    .055       0  4891.8      .1       0
  4994.9     .05       0  5004.3      .1       0  5039.8     .06       0
  5129.4    .055       0
Bank Sta=4994.9,5004.3
Exp/Cntr=0.3,0.1

Type RM Length L Ch R = 1 ,14499   ,383,383,383
BEGIN DESCRIPTION:
Hunting_Crk_XS40
END DESCRIPTION:
XS GIS Cut Line= 4
 1151738.9585658  626219.5132224       1151504.6       626201.08
      1151255.17       626237.52 1151164.3806532   626289.888495
#Sta/Elev= 30
  4527.7  963.75  4546.5  961.07  4550.7  959.44  4560.9  957.76  4589.4   954.5
  4608.9   951.3    4639  948.52  4668.9  946.93  4815.8  945.39    4842  944.41
  4849.8  944.89  4882.2  942.01  4895.4  941.14  4904.7  941.71  4913.9  940.73
  4933.7     941  4950.8  942.93    4961  942.67  4970.5  944.15  4980.6  943.61
  4994.1   940.2  4995.8  938.88  5004.2  938.88  5008.3  940.16  5013.9  940.63
  5016.5  941.08  5026.5  946.02  5043.5  952.21  5073.2  954.74  5119.7  959.07
#Mann= 7 ,-1 , 0
  4527.7      .1       0  4608.9    .055       0  4882.2      .1       0
  4994.1     .05       0  5008.3      .1       0  5013.9     .06       0
  5073.2      .1       0
Bank Sta=4994.1,5008.3
Exp/Cntr=0.3,0.1