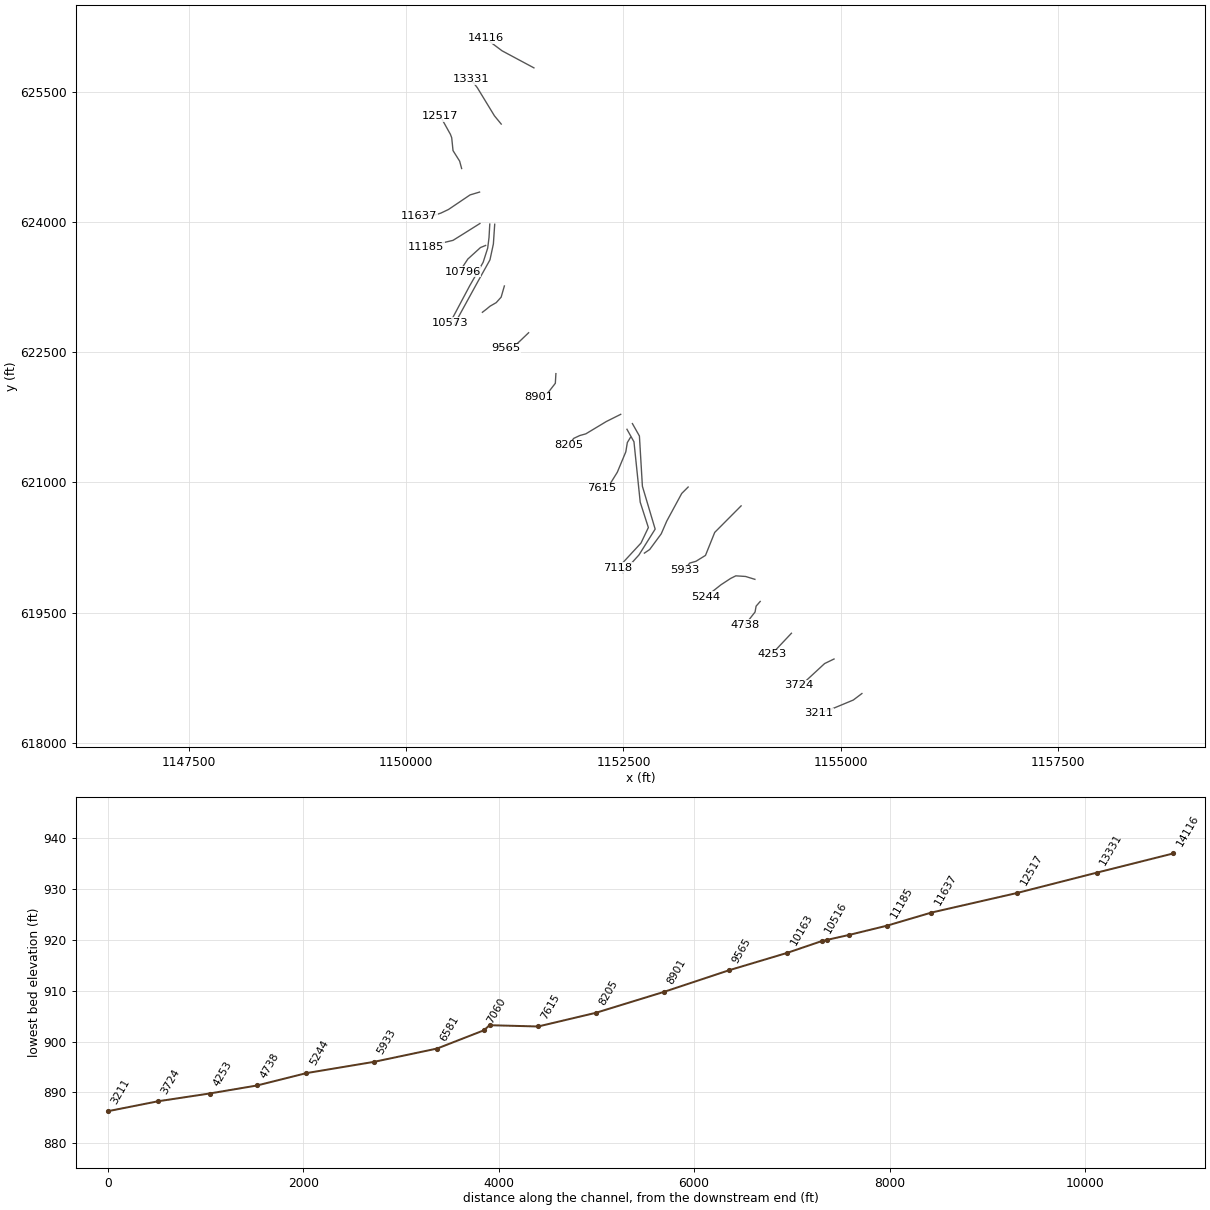
HEC-RAS study lds_hunting_crk.prj: Hunting Creek Limited Detail Study

--- lds_hunting_crk.g01 (geometry) --- (continued)

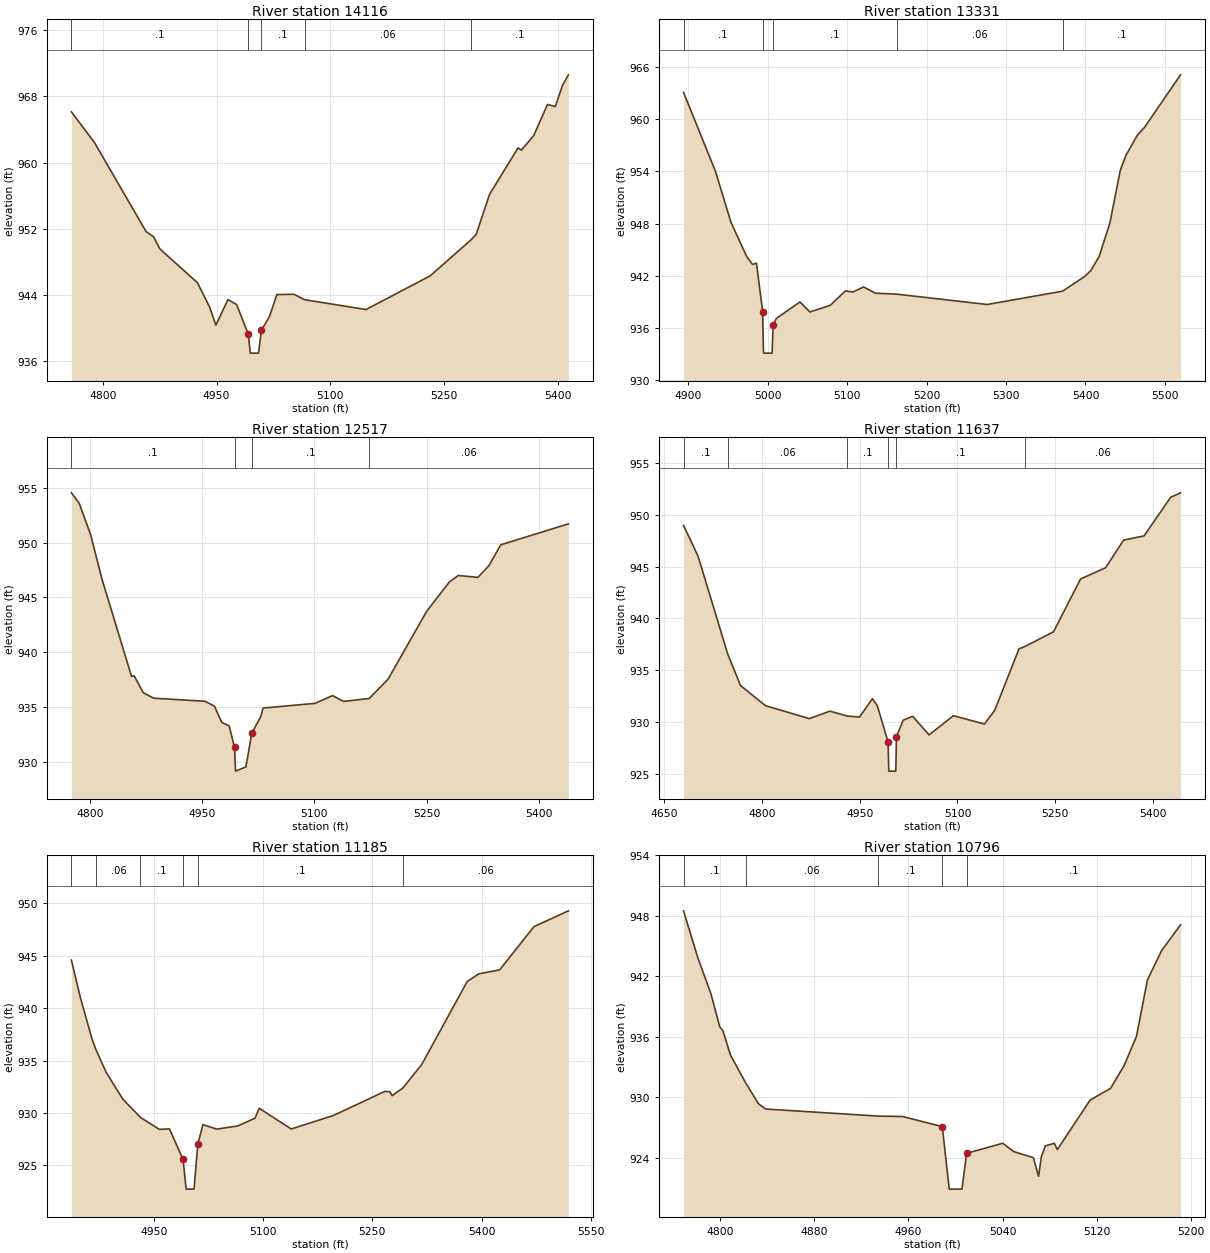
Type RM Length L Ch R = 1 ,14116   ,785,785,785
BEGIN DESCRIPTION:
Hunting_Crk_XS38
END DESCRIPTION:
XS GIS Cut Line= 3
      1151469.02       625777.53       1151102.5       625973.88
      1150910.51       626117.87
#Sta/Elev= 30
  4758.5  966.14    4789  962.41  4857.1  951.63  4866.9  951.01  4875.3  949.53
  4924.9  945.43  4941.3  942.41  4949.1  940.29  4965.1   943.4  4976.5  942.79
  4991.8  939.22  4994.6  936.91  5005.4  936.91  5009.2  939.67  5020.1  941.38
  5029.6     944  5052.1  944.04  5066.3  943.38  5147.3  942.19  5231.9  946.27
  5285.9  950.64  5292.6  951.29  5310.2  956.13  5347.8  961.77  5352.3   961.5
  5368.6  963.27  5386.7  967.03    5397  966.78  5406.5  969.35  5414.3  970.62
#Mann= 5 ,-1 , 0
  4758.5      .1       0  4991.8     .05       0  5009.2      .1       0
  5066.3     .06       0  5285.9      .1       0
Bank Sta=4991.8,5009.2
Exp/Cntr=0.3,0.1

Type RM Length L Ch R = 1 ,13331   ,814,814,814
BEGIN DESCRIPTION:
Hunting_Crk_XS37
END DESCRIPTION:
XS GIS Cut Line= 4
 1151092.4052573  625129.9523644      1151014.48       625224.77
      1150816.56       625549.86 1150741.6328825  625646.7946708
#Sta/Elev= 30
  4893.9  963.05  4934.1  953.99  4953.7  948.12  4973.5   944.2  4980.9   943.3
  4985.7  943.46  4993.5   937.9  4994.6  933.13  5005.4  933.13  5006.8   936.4
    5011  937.13  5040.5     939  5053.1  937.85  5078.7  938.62  5097.7  940.27
  5107.2  940.14  5120.6  940.72  5135.5  940.01    5163  939.89  5276.2  938.71
  5371.2  940.24    5399  941.93  5406.6  942.59  5417.3  944.24  5430.7  948.06
  5443.7  954.07    5451  955.84  5465.5  958.16  5474.3  959.03  5519.7  965.06
#Mann= 5 ,-1 , 0
  4893.9      .1       0  4993.5     .05       0  5006.8      .1       0
    5163     .06       0  5371.2      .1       0
Bank Sta=4993.5,5006.8
Exp/Cntr=0.3,0.1

Type RM Length L Ch R = 1 ,12517   ,880,880,880
BEGIN DESCRIPTION:
Hunting_Crk_XS35
END DESCRIPTION:
XS GIS Cut Line= 6
 1150636.6800441  624617.6438367       1150613.6       624703.04
      1150537.55       624823.94      1150522.27       624972.29
       1150507.4       625011.71 1150389.9869671  625222.5799339
#Sta/Elev= 30
  4775.1  954.53  4785.6  953.57  4800.8  950.72    4816  946.66  4855.5  937.79
  4859.1  937.83  4871.2   936.3  4885.2   935.8  4953.9  935.52  4966.4  935.07
  4976.1   933.6  4986.1  933.26  4993.2  931.31  4994.6  929.15  5008.4  929.53
  5016.3   932.6  5028.5  934.15  5031.3   934.9  5100.9  935.33  5124.2  936.04
    5139  935.51  5173.3  935.77  5198.6  937.55  5250.3  943.75  5280.7  946.42
  5292.4  946.99  5318.6  946.82  5333.1  947.87  5349.2  949.79  5439.6   951.7
#Mann= 4 ,-1 , 0
  4775.1      .1       0  4993.2     .05       0  5016.3      .1       0
  5173.3     .06       0
Bank Sta=4993.2,5016.3
Exp/Cntr=0.3,0.1

Type RM Length L Ch R = 1 ,11637   ,452,452,452
BEGIN DESCRIPTION:
Hunting_Crk_XS33
END DESCRIPTION:
XS GIS Cut Line= 6
      1150842.88       624346.35       1150733.8       624313.62
      1150485.09       624145.63      1150397.82       624104.18
      1150332.37       624082.36      1150149.11       624075.82
#Sta/Elev= 30
  4679.5  948.97  4701.8  946.01  4747.4  936.56    4767  933.54  4805.2   931.6
  4872.6  930.35  4904.2  931.07  4930.8   930.6  4949.7   930.5  4969.4  932.27
    4977  931.59  4993.5  928.11  4994.6  925.29  5005.4  925.29  5006.3  928.61
  5016.7   930.2  5031.3  930.57  5056.4  928.78  5093.7  930.63  5141.5  929.83
  5157.3  931.16  5194.5  937.07  5204.2  937.32  5247.5  938.72    5289  943.81
  5327.5  944.89    5355  947.55  5386.5  947.96  5427.3  951.68  5442.5  952.11
#Mann= 6 ,-1 , 0
  4679.5      .1       0  4747.4     .06       0  4930.8      .1       0
  4993.5     .05       0  5006.3      .1       0  5204.2     .06       0
Bank Sta=4993.5,5006.3
Exp/Cntr=0.3,0.1

Type RM Length L Ch R = 1 ,11185   ,389,389,389
BEGIN DESCRIPTION:
Hunting_Crk_XS30
END DESCRIPTION:
XS GIS Cut Line= 4
      1150847.24       623984.19      1150653.07       623862.02
      1150537.45       623790.02      1150229.83       623715.84
#Sta/Elev= 30
  4837.1   944.6  4849.5     941  4865.2  937.11  4871.1     936  4884.9  933.87
  4907.9   931.3  4931.9  929.58  4957.7  928.44  4971.7  928.48  4990.3  925.57
  4994.6  922.73  5005.4  922.73  5010.6  927.01  5017.6  928.89  5036.4  928.46
  5065.4  928.76    5089   929.5  5094.9  930.45  5138.8  928.47    5197  929.77
  5267.2  932.06  5274.2  932.03  5277.3  931.65  5292.1  932.39  5317.9  934.63
  5380.2  942.54    5396  943.28  5424.8  943.66  5471.9  947.79  5519.2   949.3
#Mann= 6 ,-1 , 0
  4837.1      .1       0  4871.1     .06       0  4931.9      .1       0
  4990.3     .05       0  5010.6      .1       0  5292.1     .06       0
Bank Sta=4990.3,5010.6
Exp/Cntr=0.3,0.1

Type RM Length L Ch R = 1 ,10796   ,223,223,223
BEGIN DESCRIPTION:
Hunting_Crk_XS29
END DESCRIPTION:
XS GIS Cut Line= 5
      1150912.69       623731.11      1150853.79       623707.12
      1150707.62       623574.03      1150653.07       623491.13
      1150648.71       623430.04
#Sta/Elev= 30
  4769.1   948.5  4781.3  943.83  4792.4  940.26  4799.8  937.01  4802.5  936.62
  4808.9  934.21  4821.8  931.46  4832.7  929.37  4838.9  928.85  4934.4  928.15
  4954.9  928.11  4988.7  927.11  4994.6  920.91  5005.4  920.91  5009.3  924.46
    5040  925.46  5049.3  924.63    5066  924.03  5070.4  922.18  5072.7  924.08
  5076.1  925.19  5083.7  925.46  5086.3  924.83  5114.1  929.73  5131.5   930.9
  5143.1  933.18  5153.5  936.06  5162.8  941.66  5174.8  944.55  5190.9  947.12
#Mann= 5 ,-1 , 0
  4769.1      .1       0  4821.8     .06       0  4934.4      .1       0
  4988.7     .05       0  5009.3      .1       0
Bank Sta=4988.7,5009.3
Exp/Cntr=0.5,0.3

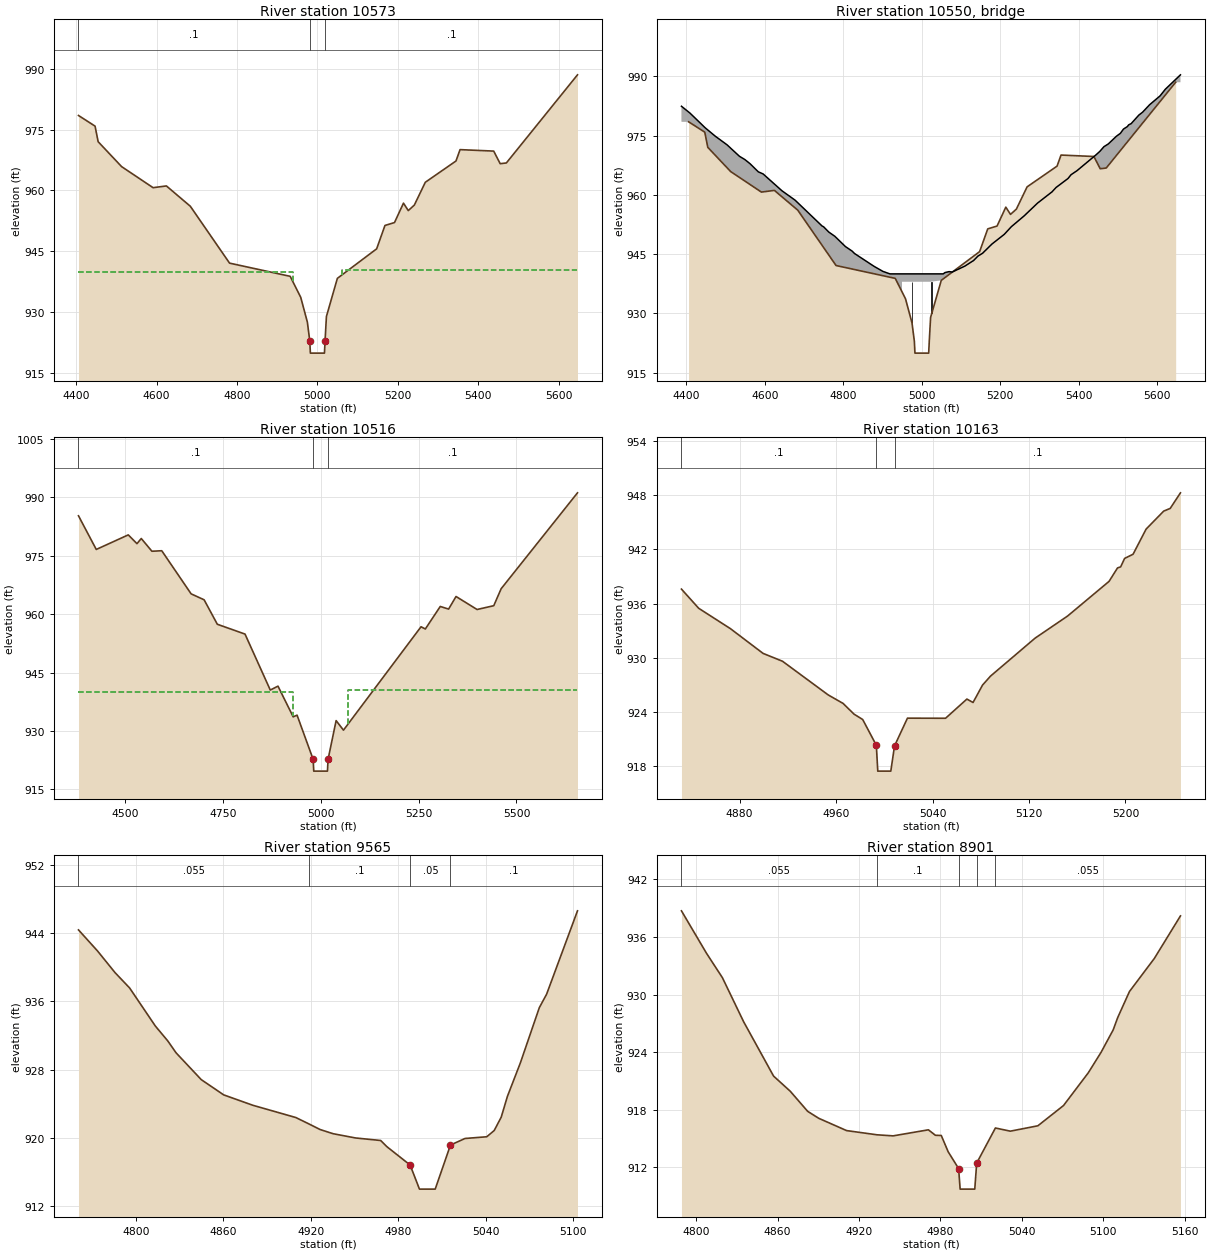
Type RM Length L Ch R = 1 ,10573   ,57,57,57
BEGIN DESCRIPTION:
Hunting_Crk_XS28
END DESCRIPTION:
XS GIS Cut Line= 6
      1150960.69       623977.64      1150951.96       623822.75
      1150936.69       623700.57      1150884.33       623536.95
      1150729.43       623266.42      1150504.72       622843.17
#Sta/Elev= 30
  4405.8  978.47    4447  975.85  4454.7  972.01    4513  965.88  4591.3  960.69
  4624.4  961.12  4683.9  956.12  4781.5  942.11  4932.3  938.86  4958.5  933.69
    4975  927.59    4981  922.95  4982.5  919.95  5017.5  919.95    5019  922.95
  5022.4  928.98  5049.6  938.36  5147.3  945.63    5168  951.39  5191.7   952.1
    5214  956.88    5226  955.05    5241   956.4  5268.3  962.02  5344.6  967.26
  5354.7  970.06  5438.4   969.7  5454.5   966.6  5469.9  966.78  5646.8  988.48
#Mann= 3 ,-1 , 0
  4405.8      .1       0    4981     .05       0    5019      .1       0
#XS Ineff= 2 , 0
       0    4940     940    5060       0  940.35
Permanent Ineff=
       F       F
Bank Sta=4981,5019
Exp/Cntr=0.5,0.3

Type RM Length L Ch R = 3 ,10550   ,,,
BEGIN DESCRIPTION:
Hunting_Crk_XS26
Structure ID: Whiteside Rd. SR-1538
Approximate Survey Structure
END DESCRIPTION:
Bridge Culvert--1,0,-1,-1, 0
Deck Dist Width WeirC Skew NumUp NumDn MinLoCord MaxHiCord MaxSubmerge Is_Ogee
9.5,27,3,0, 60, 60, , , , 0, 1,1,,
  4387.6  4409.4  4447.9  4473.7  4503.8  4535.5  4549.1  4562.6  4583.4  4595.6
  4643.6    4677  4745.9  4749.7  4762.9  4778.5  4805.4  4822.5  4828.5  4878.1
  4900.9  4918.7  4949.5  4949.5  5050.5  5050.5  5054.5  5059.2  5069.4  5077.5
  5109.8    5132    5143  5154.7  5178.9  5210.1    5228  5260.7  5294.9  5331.8
  5342.1  5372.6  5380.1  5395.3  5443.5  5453.6  5464.1  5475.2  5495.5  5505.9
  5513.7  5523.7  5526.9  5533.5    5553  5562.3  5580.3  5607.1  5620.3    5659
  982.41  980.67  976.97  974.84  972.65  969.74  968.93  967.85  965.82  965.29
  961.03  958.66  952.11  951.92  950.59   949.5  946.91  945.76  945.16  941.92
  940.63     940     940     940     940     940     940  940.34  940.57  940.47
  941.97  943.39   944.5  945.21  947.57     950  951.93  954.67  957.91  960.76
  961.86  964.14  965.08   966.1  970.09     971  972.19  972.88   974.8  975.56
  976.63  977.27  977.69  978.03  980.18  980.89  982.79  985.04   986.7  990.36
  899.95  899.95  899.95  899.95  899.95  899.95  899.95  899.95  899.95  899.95
  899.95  899.95  899.95  899.95  899.95  899.95  899.95  899.95  899.95  899.95
  899.95  899.95  899.95     938     938  899.95  899.95  899.95  899.95  899.95
  899.95  899.95  899.95  899.95  899.95  899.95  899.95  899.95  899.95  899.95
  899.95  899.95  899.95  899.95  899.95  899.95  899.95  899.95  899.95  899.95
  899.95  899.95  899.95  899.95  899.95  899.95  899.95  899.95  899.95  899.95
  4387.6  4409.4  4447.9  4473.7  4503.8  4535.5  4549.1  4562.6  4583.4  4595.6
  4643.6    4677  4745.9  4749.7  4762.9  4778.5  4805.4  4822.5  4828.5  4878.1
  4900.9  4918.7  4949.5  4949.5  5050.5  5050.5  5054.5  5059.2  5069.4  5077.5
  5109.8    5132    5143  5154.7  5178.9  5210.1    5228  5260.7  5294.9  5331.8
  5342.1  5372.6  5380.1  5395.3  5443.5  5453.6  5464.1  5475.2  5495.5  5505.9
  5513.7  5523.7  5526.9  5533.5    5553  5562.3  5580.3  5607.1  5620.3    5659
  982.41  980.67  976.97  974.84  972.65  969.74  968.93  967.85  965.82  965.29
  961.03  958.66  952.11  951.92  950.59   949.5  946.91  945.76  945.16  941.92
  940.63     940     940     940     940     940     940  940.34  940.57  940.47
  941.97  943.39   944.5  945.21  947.57     950  951.93  954.67  957.91  960.76
  961.86  964.14  965.08   966.1  970.09     971  972.19  972.88   974.8  975.56
  976.63  977.27  977.69  978.03  980.18  980.89  982.79  985.04   986.7  990.36
  899.95  899.95  899.95  899.95  899.95  899.95  899.95  899.95  899.95  899.95
  899.95  899.95  899.95  899.95  899.95  899.95  899.95  899.95  899.95  899.95
  899.95  899.95  899.95     938     938  899.95  899.95  899.95  899.95  899.95
  899.95  899.95  899.95  899.95  899.95  899.95  899.95  899.95  899.95  899.95
  899.95  899.95  899.95  899.95  899.95  899.95  899.95  899.95  899.95  899.95
  899.95  899.95  899.95  899.95  899.95  899.95  899.95  899.95  899.95  899.95
Pier Skew, UpSta & Num, DnSta & Num=  ,4974.8, 2 ,4974.8, 2 , 0 , 0 , 0 ,0,0
     1.5     1.5
  927.66     938
     1.5     1.5
     925     938
Pier Skew, UpSta & Num, DnSta & Num=  ,5025.3, 2 ,5025.3, 2 , 0 , 0 , 0 ,0,0
     1.5     1.5
  929.86     938
     1.5     1.5
  926.39     938
Abutment Skew #Up #Dn= , 2 , 2
  4949.5    4951
     938  934.82
  4949.5    4951
     938  931.53
Abutment Skew #Up #Dn= , 2 , 2
    5049  5050.5
  938.14     938
    5049  5050.5
  931.86     938
BR Coef= 1 , 1 , 0 ,1.25, 0 ,,,0.8,0,2,0,
WSPro=,,,, 1 ,,,, 0 ,,,, 0 ,,,,-1 ,-1 ,-1 , 0 , 0 , 0 , 0 , 0
BC Design=,, 0 ,, 0 ,,,,,,
BC HTab HWMax=988.48

Type RM Length L Ch R = 1 ,10516   ,353,353,353
BEGIN DESCRIPTION:
Hunting_Crk_XS27
END DESCRIPTION:
XS GIS Cut Line= 6
      1151017.41       623975.46      1151002.14       623748.57
      1150962.87       623565.31      1150834.15       623334.05
      1150687.98       623067.89      1150548.35       622812.63
#Sta/Elev= 30
  4381.8  985.26  4427.2  976.62  4508.9  980.36  4531.1  978.11  4542.1  979.43
  4569.3  976.16  4594.4  976.29  4669.4  965.22  4702.6  963.69  4736.3  957.41
    4807  954.89  4871.5  940.52  4891.2  941.52    4930  933.64  4939.9  934.07
    4981   922.7  4982.5   919.7  5017.5   919.7    5019   922.7  5039.6  932.67
  5058.4  930.22  5256.4  956.77  5267.4   956.2  5305.5  961.98  5326.8  961.31
  5345.8  964.54  5399.5   961.2  5442.1  962.18    5461  966.54  5655.9  991.16
#Mann= 3 ,-1 , 0
  4381.8      .1       0    4981     .05       0    5019      .1       0
#XS Ineff= 2 , 0
       0    4929     940    5071       0  940.55
Permanent Ineff=
       F       F
Bank Sta=4981,5019
Exp/Cntr=0.5,0.3

Type RM Length L Ch R = 1 ,10163   ,598,598,598
BEGIN DESCRIPTION:
Hunting_Crk_XS31
END DESCRIPTION:
XS GIS Cut Line= 6
      1151128.68       623264.24      1151091.59       623135.52
      1151034.87       623072.25      1150962.87        623030.8
       1150923.6       622998.07      1150875.61       622960.98
#Sta/Elev= 30
  4831.8   937.6  4846.1  935.47  4872.4  933.21  4899.5  930.46  4915.6  929.59
  4953.5  925.85  4965.8  924.91  4974.9  923.72  4982.1  923.12  4993.4  920.26
  4994.6  917.39  5005.4  917.39  5008.5  920.19  5019.2  923.27  5050.8  923.26
  5068.5  925.39  5073.6  925.01  5081.5  926.95  5088.1  927.94  5125.1  932.16
    5152  934.61  5186.4  938.46  5193.4  939.95    5196  940.07  5199.3  941.01
  5206.3  941.47  5217.1  944.26  5231.7  946.26  5237.1  946.56  5245.6  948.29
#Mann= 3 ,-1 , 0
  4831.8      .1       0  4993.4     .05       0  5008.5      .1       0
Bank Sta=4993.4,5008.5
Exp/Cntr=0.3,0.1

Type RM Length L Ch R = 1 ,9565    ,664,664,664
BEGIN DESCRIPTION:
Hunting_Crk_XS25
END DESCRIPTION:
XS GIS Cut Line= 4
      1151407.93       622725.36       1151305.4       622627.19
      1151207.22       622535.56      1151141.77       622546.47
#Sta/Elev= 30
  4760.5  944.41  4773.5  941.95  4785.6  939.39  4795.6  937.59  4813.3  933.11
  4821.8  931.37  4827.5  929.97  4844.8  926.82  4860.2  925.03  4880.2  923.81
  4909.7  922.37  4918.7  921.62  4926.4  920.96  4935.3  920.47  4950.7  919.97
    4968  919.67  4972.2  918.95  4988.2  916.79  4994.6  913.96  5005.4  913.96
  5015.9  919.14  5025.9  919.91  5040.8  920.11  5045.9  920.84  5050.7   922.4
    5055  924.86  5063.9   928.8  5076.9  935.28  5081.9  936.86  5103.1  946.65
#Mann= 4 ,-1 , 0
  4760.5    .055       0  4918.7      .1       0  4988.2     .05       0
  5015.9      .1       0
Bank Sta=4988.2,5015.9
Exp/Cntr=0.3,0.1

Type RM Length L Ch R = 1 ,8901    ,696,696,696
BEGIN DESCRIPTION:
Hunting_Crk_XS24
END DESCRIPTION:
XS GIS Cut Line= 4
       1151722.1       622254.12      1151715.55       622142.86
      1151632.65       622035.95      1151523.56       621983.59
#Sta/Elev= 30
  4789.2  938.73  4807.6  934.32  4819.4  931.76    4835  927.18  4857.1  921.51
  4869.4  919.93  4882.2  917.84  4890.4  917.11  4910.9  915.83  4933.4  915.39
  4945.2  915.28  4971.2  915.91  4976.4  915.34  4980.7  915.32  4985.8  913.62
  4993.5  911.87  4994.6  909.73  5005.4  909.73  5006.8  912.44  5020.6   916.1
  5031.6  915.77  5051.9  916.33  5070.8  918.44  5089.1  921.86  5098.5  923.99
  5107.4  926.32  5110.7  927.59  5119.4  930.32  5137.7  933.76    5157   938.2
#Mann= 5 ,-1 , 0
  4789.2    .055       0  4933.4      .1       0  4993.5     .05       0
  5006.8      .1       0  5020.6    .055       0
Bank Sta=4993.5,5006.8
Exp/Cntr=0.3,0.1

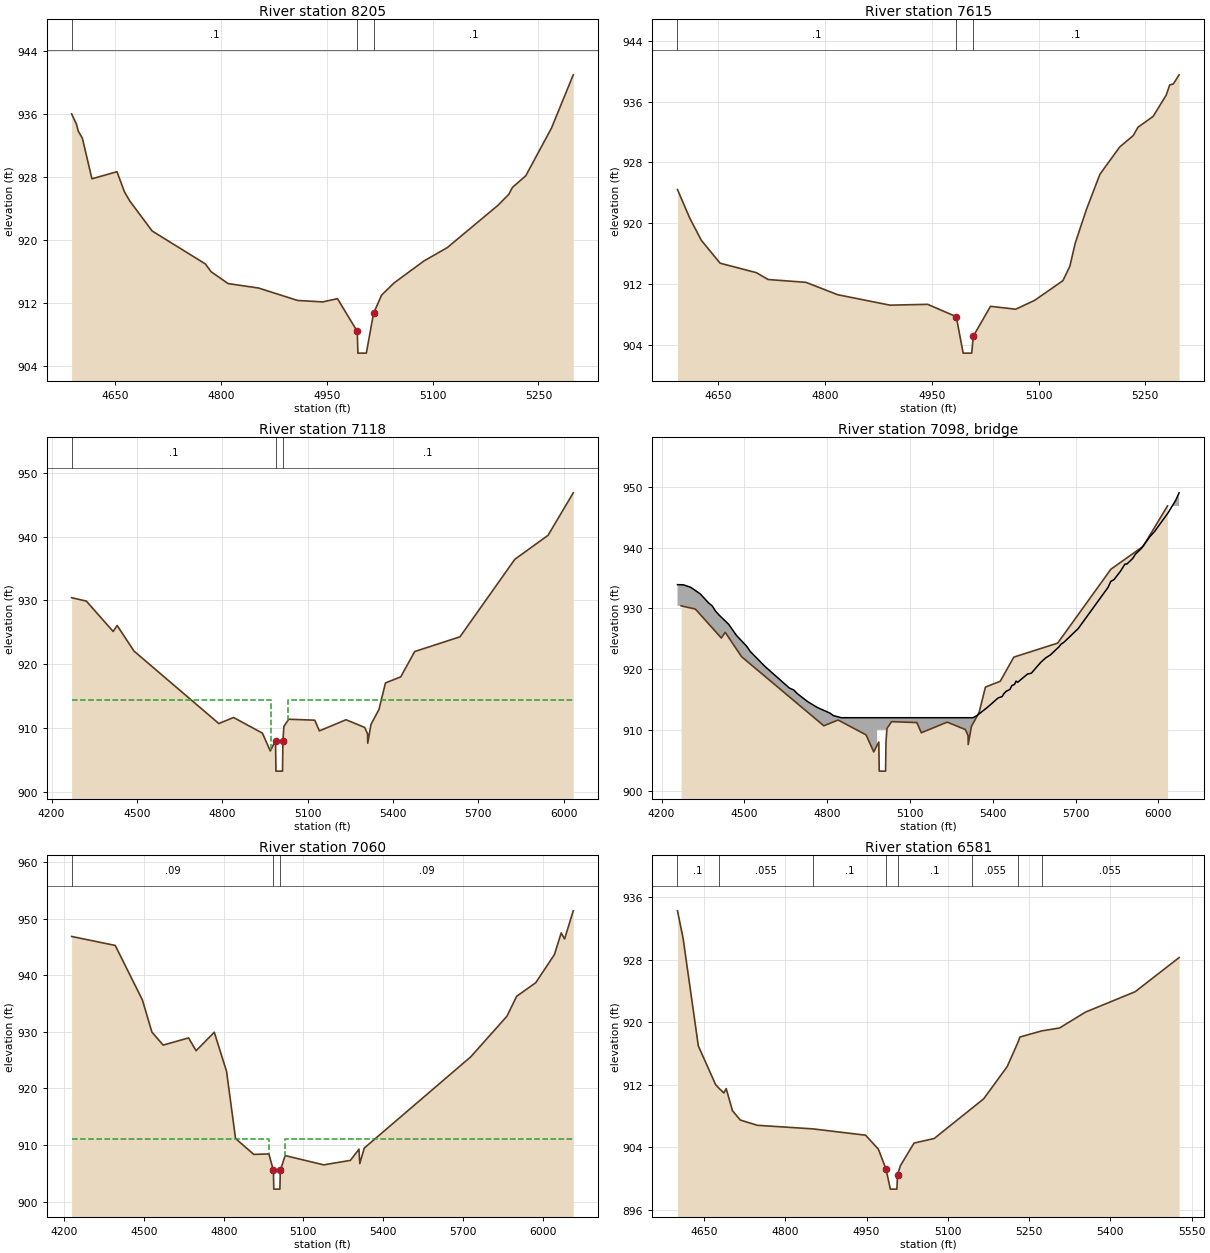
Type RM Length L Ch R = 1 ,8205    ,590,590,590
BEGIN DESCRIPTION:
Hunting_Crk_XS23
END DESCRIPTION:
XS GIS Cut Line= 6
      1152468.23       621785.06      1152302.42       621702.16
       1152066.8       621560.35      1151996.99       621540.71
      1151927.17       621507.99      1151866.09       621427.27
#Sta/Elev= 30
  4588.1  936.03    4595  934.72  4597.6  933.82  4603.3  932.95  4616.9  927.78
  4652.4  928.68  4663.1  926.11  4670.5  924.97  4702.3  921.15  4777.8  916.96
  4785.8  915.98  4809.9  914.47  4853.2   913.9  4908.6  912.32  4944.1  912.14
  4965.1  912.55  4993.2  908.38    4994  905.63    5006  905.63  5016.2  910.67
  5027.6     913  5045.5  914.56  5087.5  917.33  5120.7  919.03  5192.5   924.4
  5208.1  925.82  5213.1  926.68  5232.1  928.17  5268.5  934.22  5299.4  940.99
#Mann= 3 ,-1 , 0
  4588.1      .1       0  4993.2     .05       0  5016.2      .1       0
Bank Sta=4993.2,5016.2
Exp/Cntr=0.3,0.1

Type RM Length L Ch R = 1 ,7615    ,497,497,497
BEGIN DESCRIPTION:
Hunting_Crk_XS21
END DESCRIPTION:
XS GIS Cut Line= 6
      1152581.68       621521.08      1152544.59       621459.99
      1152527.13       621353.09      1152428.96       621117.47
      1152343.87       620980.02       1152245.7       620934.21
#Sta/Elev= 30
  4592.5  924.44  4609.9  920.66  4626.1  917.76  4652.5  914.76  4703.4  913.52
 4719.92  912.62    4773  912.25  4817.8  910.62  4891.1  909.25  4944.1  909.36
  4984.3  907.74    4994  902.95    5006  902.95  5008.2  905.16  5032.4   909.1
  5067.9  908.72  5094.4  909.88  5134.2  912.47    5144  914.38  5151.4  917.37
  5167.1  921.79  5186.2  926.45    5214  930.03    5233  931.53  5239.6  932.62
  5260.9  934.04  5279.4  936.85  5284.3  938.19  5289.3  938.31  5297.5  939.51
#Mann= 3 ,-1 , 0
  4592.5      .1       0  4984.3     .05       0  5008.2      .1       0
Bank Sta=4984.3,5008.2
Exp/Cntr=0.5,0.3

Type RM Length L Ch R = 1 ,7118    ,58,58,58
BEGIN DESCRIPTION:
Hunting_Crk_XS19
END DESCRIPTION:
XS GIS Cut Line= 6
      1152540.22       621612.71      1152620.95       621468.72
      1152692.94       620772.76      1152786.75       620480.42
      1152701.67       620301.52      1152437.69       620015.72
#Sta/Elev= 30
  4270.5  930.43  4322.3   929.9  4416.4  925.13  4430.5  926.07  4489.7  922.05
  4787.8  910.67  4839.5  911.62  4940.9  909.17  4968.6  906.37    4987     908
  4988.5   903.2  5011.5   903.2    5013     908  5016.4  910.22  5033.3  911.35
  5124.8   911.2  5141.1  909.52  5234.8  911.27  5300.3  910.06  5310.4  909.05
    5311  907.58  5322.4  910.53  5350.6   912.9  5373.3  917.05  5426.9     918
  5476.1  921.98  5635.1  924.29  5827.8  936.46  5944.7  940.23  6033.2   946.9
#Mann= 3 ,-1 , 0
  4270.5      .1       0    4987     .05       0    5013      .1       0
#XS Ineff= 2 , 0
       0 4969.87   914.3 5029.22       0   914.3
Permanent Ineff=
       F       F
Bank Sta=4987,5013
Exp/Cntr=0.5,0.3

Type RM Length L Ch R = 3 ,7098    ,,,
BEGIN DESCRIPTION:
Hunting_Crk_XS17
Structure ID: Lebanon Church Rd. SR-1706
Approximate Survey Structure
END DESCRIPTION:
Bridge Culvert--1,0,-1,-1, 0
Deck Dist Width WeirC Skew NumUp NumDn MinLoCord MaxHiCord MaxSubmerge Is_Ogee
11,18,3,0, 60, 60, , , , 0, 1,1,,
  4257.5  4278.3  4304.9    4340  4370.7  4382.7  4395.2  4408.6    4443    4471
  4508.7  4521.7  4574.4  4662.6  4678.9  4691.9  4729.1  4763.6  4809.9  4822.2
  4850.8    4981    4981    5019    5019  5328.4  5342.5    5380  5419.4  5433.6
  5440.1  5448.9  5461.8  5469.3  5478.7  5484.2  5489.9  5525.9  5539.6    5574
  5591.5  5608.6  5639.8    5648    5656  5709.4    5818  5827.4  5839.1  5862.4
  5878.9  5885.9    5907  5916.6  5937.6  5970.4  5985.7  6035.5  6062.4  6075.1
  933.92   933.9   933.5   932.4  930.89  930.46  929.58   928.9  927.39  925.57
  923.74  922.89  920.45   916.9  916.57  915.96  914.65   913.7  912.76  912.35
     912     912     912     912     912     912  912.35  913.69  915.26  915.48
  915.96  916.37  916.65   917.3  917.48  918.03  917.83   919.2  919.33  921.14
  921.85  922.34  923.68  924.16  924.36  926.68   933.5  934.46  934.75  936.12
  937.32  937.32  938.24  938.93  939.85  941.91  942.65  945.78   947.8  949.05
  881.23  881.23  881.23  881.23  881.23  881.23  881.23  881.23  881.23  881.23
  881.23  881.23  881.23  881.23  881.23  881.23  881.23  881.23  881.23  881.23
  881.23  881.23     910     910  881.23  881.23  881.23  881.23  881.23  881.23
  881.23  881.23  881.23  881.23  881.23  881.23  881.23  881.23  881.23  881.23
  881.23  881.23  881.23  881.23  881.23  881.23  881.23  881.23  881.23  881.23
  881.23  881.23  881.23  881.23  881.23  881.23  881.23  881.23  881.23  881.23
  4257.5  4278.3  4304.9    4340  4370.7  4382.7  4395.2  4408.6    4443    4471
  4508.7  4521.7  4574.4  4662.6  4678.9  4691.9  4729.1  4763.6  4809.9  4822.2
  4850.8    4981    4981    5019    5019  5328.4  5342.5    5380  5419.4  5433.6
  5440.1  5448.9  5461.8  5469.3  5478.7  5484.2  5489.9  5525.9  5539.6    5574
  5591.5  5608.6  5639.8    5648    5656  5709.4    5818  5827.4  5839.1  5862.4
  5878.9  5885.9    5907  5916.6  5937.6  5970.4  5985.7  6035.5  6062.4  6075.1
  933.92   933.9   933.5   932.4  930.89  930.46  929.58   928.9  927.39  925.57
  923.74  922.89  920.45   916.9  916.57  915.96  914.65   913.7  912.76  912.35
     912     912     912     912     912     912  912.35  913.69  915.26  915.48
  915.96  916.37  916.65   917.3  917.48  918.03  917.83   919.2  919.33  921.14
  921.85  922.34  923.68  924.16  924.36  926.68   933.5  934.46  934.75  936.12
  937.32  937.32  938.24  938.93  939.85  941.91  942.65  945.78   947.8  949.05
  881.23  881.23  881.23  881.23  881.23  881.23  881.23  881.23  881.23  881.23
  881.23  881.23  881.23  881.23  881.23  881.23  881.23  881.23  881.23  881.23
  881.23  881.23     910     910  881.23  881.23  881.23  881.23  881.23  881.23
  881.23  881.23  881.23  881.23  881.23  881.23  881.23  881.23  881.23  881.23
  881.23  881.23  881.23  881.23  881.23  881.23  881.23  881.23  881.23  881.23
  881.23  881.23  881.23  881.23  881.23  881.23  881.23  881.23  881.23  881.23
BR Coef= 1 , 1 , 0 ,1.25, 0 ,,,0.8,0,2,0,
WSPro=,,,, 1 ,,,, 0 ,,,, 0 ,,,,-1 ,-1 ,-1 , 0 , 0 , 0 , 0 , 0
BC Design=,, 0 ,, 0 ,,,,,,
BC HTab HWMax=946.9

Type RM Length L Ch R = 1 ,7060    ,479,479,479
BEGIN DESCRIPTION:
Hunting_Crk_XS18
END DESCRIPTION:
XS GIS Cut Line= 6
      1152603.07       621678.28      1152683.69       621535.37
      1152718.08       620956.28      1152865.01       620462.43
      1152678.35       620164.74      1152494.91       619961.99
#Sta/Elev= 30
  4227.7  946.86  4391.8  945.27  4493.9  935.66  4529.8  929.96  4572.2  927.66
  4667.9  928.93  4696.1  926.66  4764.5  929.93  4810.8  923.01  4844.5  911.15
  4913.2  908.34  4970.1  908.42    4987   905.5  4988.5   902.2  5011.5   902.2
    5013   905.5  5031.2  908.13  5176.2  906.49  5276.7  907.28  5309.1  909.26
    5312  906.71    5329  909.46  5729.8  925.59  5865.8  932.76  5902.3  936.28
  5974.3  938.69  6044.6  943.67  6070.1  947.49  6082.7  946.42  6115.4  951.39
#Mann= 3 ,-1 , 0
  4227.7     .09       0    4987     .05       0    5013     .09       0
#XS Ineff= 2 , 0
       0    4970     911    5030       0     911
Permanent Ineff=
       F       F
Bank Sta=4987,5013
Exp/Cntr=0.5,0.3

Type RM Length L Ch R = 1 ,6581    ,648,648,648
BEGIN DESCRIPTION:
Hunting_Crk_XS22
END DESCRIPTION:
XS GIS Cut Line= 6
       1153244.9        620947.3      1153170.73       620873.12
      1152998.38        620554.6      1152935.11       620408.42
      1152802.02       620227.34      1152740.94       620185.89
#Sta/Elev= 30
  4601.1  934.28  4611.4  930.79  4639.6  916.97  4671.5  912.01  4677.4  911.56
  4686.7  910.95    4691   911.5  4702.6  908.67  4717.1  907.47  4748.4   906.8
  4851.1  906.34 4948.25  905.53  4971.8  903.75  4985.8  901.23    4994  898.62
    5006  898.62  5007.3  900.48  5012.5  901.62 5037.64  904.52 5074.95  905.11
  5144.8     909  5166.2  910.19  5209.6  914.32  5229.4  917.42  5233.1  918.11
    5273  918.89  5306.3  919.27    5354   921.3  5445.9  923.92  5526.9  928.29
#Mann= 8 ,-1 , 0
  4601.1      .1       0  4677.4    .055       0  4851.1      .1       0
  4985.8     .05       0  5007.3      .1       0  5144.8    .055       0
  5229.4      .1       0    5273    .055       0
Bank Sta=4985.8,5007.3
Exp/Cntr=0.3,0.1

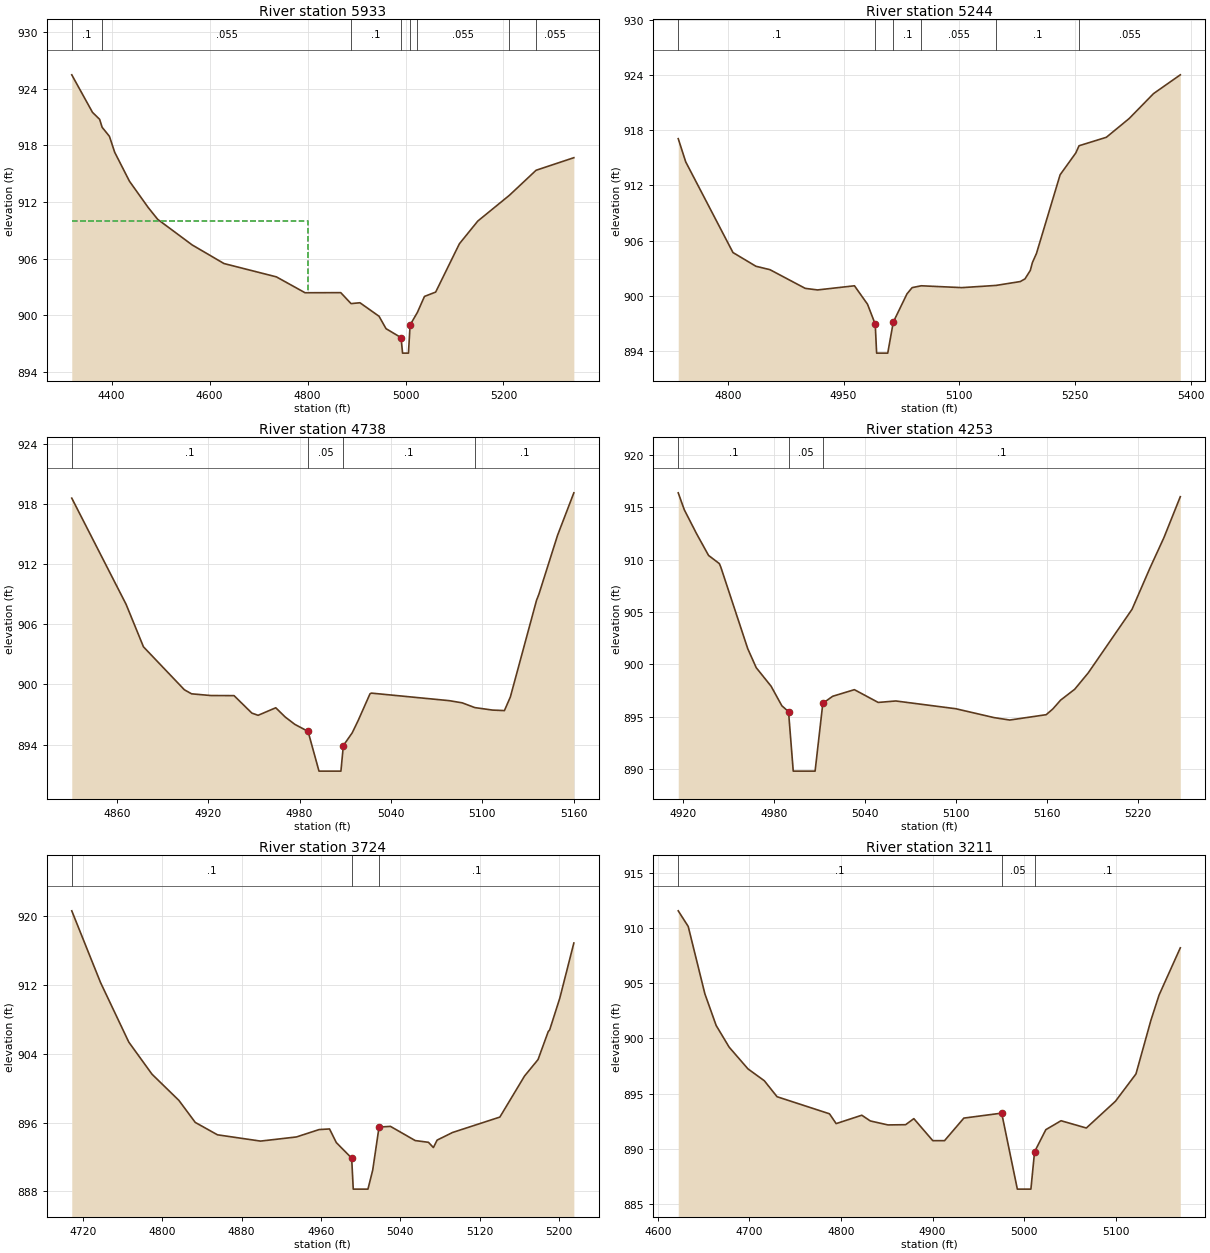
Type RM Length L Ch R = 1 ,5933    ,689,689,689
BEGIN DESCRIPTION:
Hunting_Crk_XS16
END DESCRIPTION:
XS GIS Cut Line= 6
      1153854.68       620730.22      1153550.99       620424.79
      1153444.53       620159.49      1153334.57       620091.43
      1153261.27       620070.48      1153201.93       619986.71
#Sta/Elev= 30
  4318.6  925.45  4360.9  921.48  4375.5  920.74  4380.6   919.9  4395.5  918.94
  4406.3  917.25  4436.4  914.19  4474.8   911.4    4494  910.16  4564.4  907.45
  4629.4  905.48  4736.4  904.07  4794.9  902.39  4867.8   902.4  4888.8  901.24
    4907  901.33    4946   899.9  4960.2  898.59  4990.9  897.64    4994     896
    5006     896  5009.4  898.98  5024.2   900.3  5038.7     902  5061.6  902.46
    5110  907.57  5147.5  909.97  5212.3  912.71  5266.6  915.35  5343.7  916.68
#Mann= 8 ,-1 , 0
  4318.6      .1       0  4380.6    .055       0  4888.8      .1       0
  4990.9     .05       0  5009.4      .1       0  5024.2    .055       0
  5212.3      .1       0  5266.6    .055       0
#XS Ineff= 2 , 0
       0    4800     910               0
Permanent Ineff=
       F       F
Bank Sta=4990.9,5009.4
Exp/Cntr=0.3,0.1

Type RM Length L Ch R = 1 ,5244    ,506,506,506
BEGIN DESCRIPTION:
Hunting_Crk_XS13
END DESCRIPTION:
XS GIS Cut Line= 6
      1154013.51       619883.73       1153905.3       619916.89
       1153793.6       619923.87      1153734.25        619894.2
      1153622.55        619820.9      1153446.27       619681.27
#Sta/Elev= 30
  4735.8  917.08  4745.5  914.56  4806.7  904.72  4836.4  903.23  4854.6  902.86
  4900.3  900.83  4916.3  900.66  4964.1  901.11    4981  899.11    4991  896.94
  4992.8   893.8  5007.2   893.8  5014.4  897.17  5032.1  900.23  5038.8  900.91
  5050.6  901.11  5103.3  900.91  5147.5  901.15  5178.9  901.57    5185  901.86
  5191.9  902.78  5194.6  903.63  5199.9  904.63  5230.5  913.16  5250.9  915.54
    5255  916.31  5290.4  917.23    5320  919.27  5351.5  921.97  5386.2  924.01
#Mann= 6 ,-1 , 0
  4735.8      .1       0    4991     .05       0  5014.4      .1       0
  5050.6    .055       0  5147.5      .1       0    5255    .055       0
Bank Sta=4991,5014.4
Exp/Cntr=0.3,0.1

Type RM Length L Ch R = 1 ,4738    ,485,485,485
BEGIN DESCRIPTION:
Hunting_Crk_XS12
END DESCRIPTION:
XS GIS Cut Line= 4
       1154074.6       619628.91      1154027.47       619574.81
      1154015.25       619506.74      1153898.32       619358.38
#Sta/Elev= 30
  4830.4  918.56  4866.1  907.98  4877.5  903.75  4904.4  899.47  4909.1  899.07
  4921.6   898.9    4937  898.89  4948.7  897.15  4952.8  896.93  4964.4  897.68
  4970.6  896.76  4976.9  896.03  4985.6  895.33  4992.8  891.37  5007.2  891.37
  5008.8  893.92  5014.6  895.18  5018.5   896.4  5026.3  899.07  5027.2  899.14
  5078.3  898.39  5086.9  898.17  5095.1   897.7  5106.8  897.45  5114.6   897.4
  5118.5  898.76  5135.7  908.39  5137.2  908.97  5149.5  914.86  5160.2  919.09
#Mann= 4 ,-1 , 0
  4830.4      .1       0  4985.6     .05       0  5008.8      .1       0
  5095.1      .1       0
Bank Sta=4985.6,5008.8
Exp/Cntr=0.3,0.1

Type RM Length L Ch R = 1 ,4253    ,529,529,529
BEGIN DESCRIPTION:
Hunting_Crk_XS11
END DESCRIPTION:
XS GIS Cut Line= 2
      1154434.14       619262.39      1154207.24       619021.53
#Sta/Elev= 30
    4917  916.38    4921  914.76  4929.1  912.47    4937   910.4  4944.1  909.62
  4945.1  909.27  4962.8   901.5  4968.4  899.68  4978.2  897.91  4985.3  896.04
  4989.7  895.48  4992.8   889.8  5007.2   889.8  5012.3  896.28  5018.8  896.95
  5033.1  897.58  5048.8  896.36  5060.4   896.5  5099.9  895.76  5125.2  894.91
  5135.5  894.68  5159.5  895.19  5163.9  895.74    5169  896.58  5178.3  897.62
  5187.2  899.18  5216.1  905.26  5227.9   909.2  5237.1   912.1  5247.9  916.01
#Mann= 3 ,-1 , 0
    4917      .1       0  4989.7     .05       0  5012.3      .1       0
Bank Sta=4989.7,5012.3
Exp/Cntr=0.3,0.1

Type RM Length L Ch R = 1 ,3724    ,513,513,513
BEGIN DESCRIPTION:
Hunting_Crk_XS10
END DESCRIPTION:
XS GIS Cut Line= 4
      1154924.58       618965.68      1154816.37       618913.32
      1154606.92       618719.59      1154523.15       618663.74
#Sta/Elev= 30
  4708.8   920.6  4737.8  912.27  4766.3  905.35  4789.7  901.62  4816.8  898.58
  4833.3  896.02  4855.7  894.58  4899.1  893.85  4935.3  894.33  4958.2  895.19
  4968.7  895.26  4975.5  893.68    4991  891.87  4992.6  888.27  5007.4  888.27
  5012.2  890.47  5018.6  895.48  5030.1  895.56  5055.1  893.91  5068.4  893.71
  5073.4   893.1  5077.1  893.96  5092.7  894.85  5140.4  896.64  5165.3  901.41
  5178.9  903.32  5189.2  906.58  5190.6  906.76  5200.8  910.44    5215  916.86
#Mann= 3 ,-1 , 0
  4708.8      .1       0    4991     .05       0  5018.6      .1       0
Bank Sta=4991,5018.6
Exp/Cntr=0.3,0.1

Type RM Length L Ch R = 1 ,3211    ,471,471,471
BEGIN DESCRIPTION:
Hunting_Crk_XS9
END DESCRIPTION:
XS GIS Cut Line= 4
      1155245.72       618567.74      1155146.23       618492.69
      1154886.18       618384.48      1154751.79        618339.1
#Sta/Elev= 30
  4622.4  911.59  4633.3  910.17  4651.5  904.05  4663.8  901.18    4678  899.21
  4698.5  897.24  4716.4  896.16  4730.3  894.71  4787.5  893.16  4794.8  892.27
  4822.8  893.03  4832.1  892.51  4851.3  892.15  4870.6  892.17  4879.6  892.72
  4900.3  890.72  4913.1  890.72  4934.2  892.77  4975.5  893.22  4992.6  886.32
  5007.4  886.32  5011.4  889.71  5023.7  891.72  5040.3  892.53  5067.9  891.87
  5099.7   894.3  5122.1  896.78  5138.4  901.65  5147.3  903.94  5170.5  908.23
#Mann= 3 ,-1 , 0
  4622.4      .1       0  4975.5     .05       0  5011.4      .1       0
Bank Sta=4975.5,5011.4
Exp/Cntr=0.3,0.1