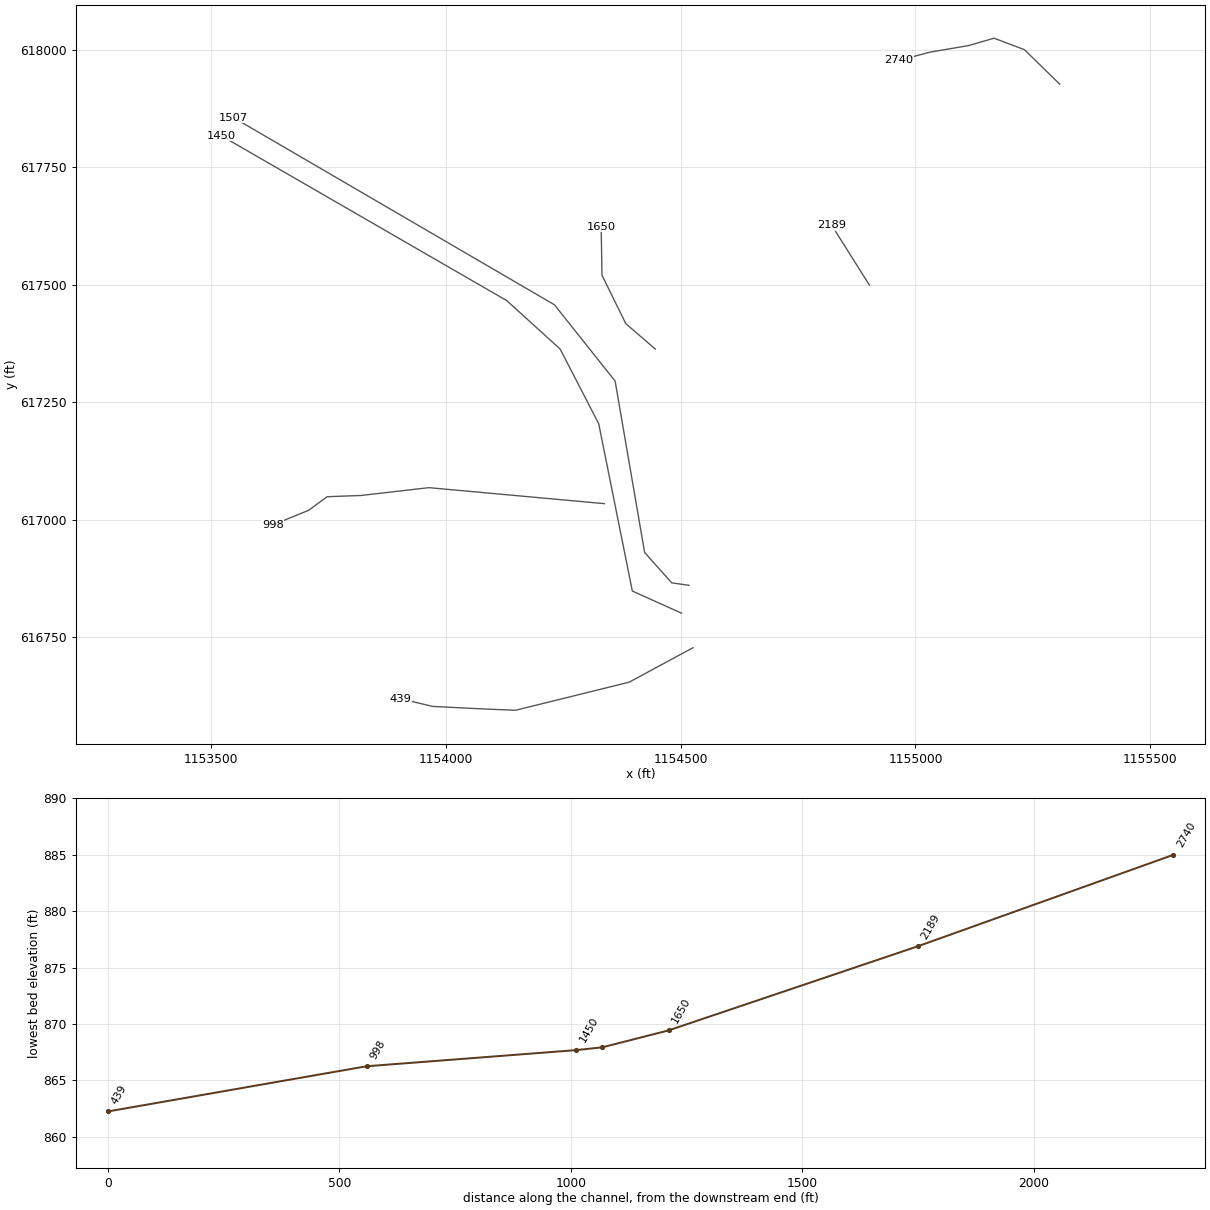
HEC-RAS study lds_hunting_crk.prj: Hunting Creek Limited Detail Study

--- lds_hunting_crk.g01 (geometry) --- (continued)

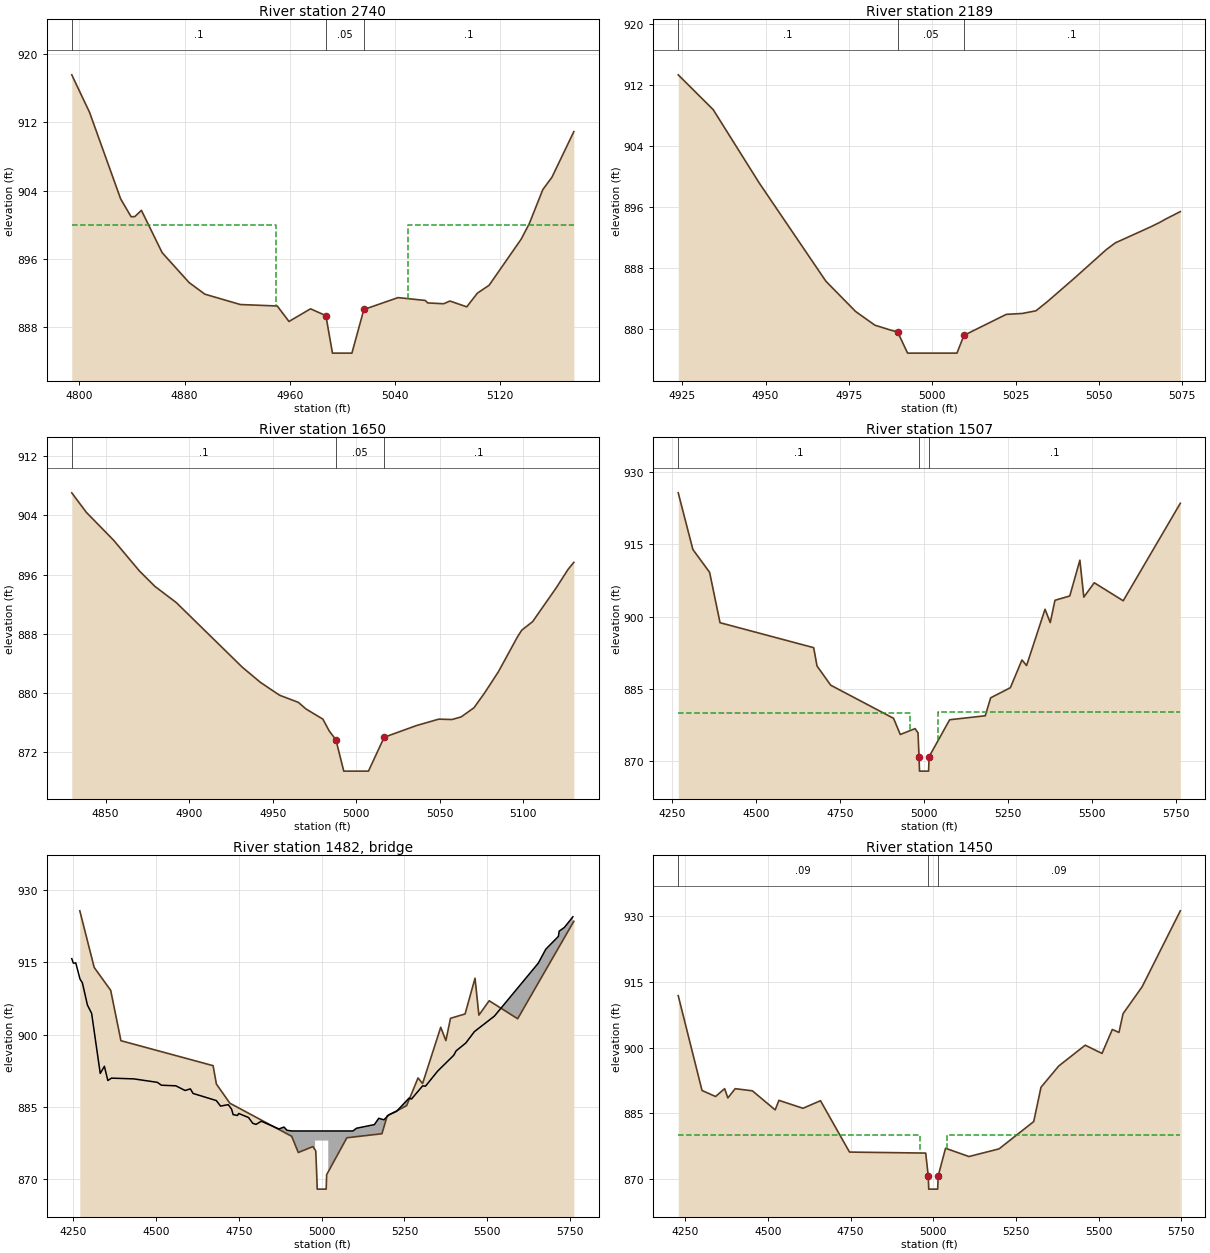
Type RM Length L Ch R = 1 ,2740    ,551,551,551
BEGIN DESCRIPTION:
Hunting_Crk_XS8
END DESCRIPTION:
XS GIS Cut Line= 6
      1155306.81        617927.2      1155231.76       618000.51
      1155167.18       618024.94      1155113.07       618009.24
      1155031.04       617995.27      1154964.72       617977.82
#Sta/Elev= 30
  4794.2  917.53  4807.7  913.16  4831.4  903.03  4839.4  900.94  4842.2  900.96
  4847.2  901.69    4863  896.74  4883.5  893.25  4895.5  891.89  4922.5  890.68
  4950.6  890.51  4959.5   888.7  4975.9  890.18  4987.6  889.38  4992.6     885
  5007.4     885  5016.5   890.1  5042.5  891.49  5063.2  891.16  5065.1  890.87
  5077.2  890.77    5082  891.09  5094.8  890.41  5102.9  892.01  5111.8  892.93
  5136.2  898.32  5142.4  900.14  5152.7  904.12  5159.6  905.55  5176.3  910.89
#Mann= 3 ,-1 , 0
  4794.2      .1       0  4987.6     .05       0  5016.5      .1       0
#XS Ineff= 2 , 0
       0    4950     900    5050       0     900
Permanent Ineff=
       F       F
Bank Sta=4987.6,5016.5
Exp/Cntr=0.3,0.1

Type RM Length L Ch R = 1 ,2189    ,539,539,539
BEGIN DESCRIPTION:
Hunting_Crk_XS7
END DESCRIPTION:
XS GIS Cut Line= 2
      1154901.89        617499.6       1154821.6       617627.01
#Sta/Elev= 22
  4923.8  913.38  4934.3  908.81  4948.1   899.2  4968.1  886.32    4977  882.36
  4982.8  880.56  4987.8  879.88  4989.6  879.68  4992.6   876.9  5007.4   876.9
  5009.5  879.23  5022.2  881.98    5027   882.1  5031.1  882.45  5034.5  883.64
  5042.8  886.79  5052.2  890.47  5054.9  891.35  5065.4  893.43  5068.2  894.03
  5069.9  894.45  5074.4  895.45
#Mann= 3 ,-1 , 0
  4923.8      .1       0  4989.6     .05       0  5009.5      .1       0
Bank Sta=4989.6,5009.5
Exp/Cntr=0.3,0.1

Type RM Length L Ch R = 1 ,1650    ,143,143,143
BEGIN DESCRIPTION:
Hunting_Crk_XS5
END DESCRIPTION:
XS GIS Cut Line= 4
      1154446.35       617363.46      1154383.52       617417.56
      1154332.91       617520.54      1154331.16       617623.51
#Sta/Elev= 30
  4829.7  907.06  4838.4  904.43  4854.8  900.64  4870.2   896.5  4879.5  894.41
  4892.3  892.22  4931.8  883.49  4942.7  881.43  4954.2  879.69  4965.4  878.73
    4970  877.83  4980.1  876.46  4983.8   874.9  4987.9  873.66  4992.6  869.43
  5007.4  869.43  5016.8  874.01    5036  875.58  5049.5  876.46  5057.4  876.41
  5062.9  876.76  5070.6     878    5077  880.02  5085.2  882.86  5096.6  887.57
  5099.2  888.49  5105.7  889.64  5120.1   894.3    5127  896.73  5130.4  897.66
#Mann= 3 ,-1 , 0
  4829.7      .1       0  4987.9     .05       0  5016.8      .1       0
Bank Sta=4987.9,5016.8
Exp/Cntr=0.5,0.3

Type RM Length L Ch R = 1 ,1507    ,57,57,57
BEGIN DESCRIPTION:
Hunting_Crk_XS3
END DESCRIPTION:
XS GIS Cut Line= 6
      1154517.91        616860.8      1154481.26       616866.04
      1154423.66       616930.61      1154360.83       617295.39
      1154231.68       617457.71      1153549.25       617855.65
#Sta/Elev= 30
  4269.1  925.68  4312.6  913.93  4362.4  909.18  4393.4  898.73  4671.8  893.55
  4681.8  889.74  4722.5  885.76  4909.3  878.89  4929.3  875.53  4973.3  876.75
  4982.1  875.86    4985  870.93  4986.5  867.93  5013.5  867.93    5015  870.93
  5076.1  878.59    5182  879.42    5198  883.14  5256.6  885.24  5291.1     891
  5304.8  889.84  5359.7  901.52  5375.2  898.75  5389.2  903.38  5433.3  904.28
  5463.3   911.7    5475  904.04  5506.1  907.02  5592.1  903.28  5761.9  923.51
#Mann= 3 ,-1 , 0
  4269.1      .1       0    4985     .05       0    5015      .1       0
#XS Ineff= 2 , 0
       0 4958.93  880.04 5040.89       0  880.18
Permanent Ineff=
       F       F
Bank Sta=4985,5015
Exp/Cntr=0.5,0.3

Type RM Length L Ch R = 3 ,1482    ,,,
BEGIN DESCRIPTION:
Hunting_Crk_XS2
Structure ID: Andrew Mills Rd. SR-1007
Approximate Survey Structure
END DESCRIPTION:
Bridge Culvert--1,0,-1,-1, 0
Deck Dist Width WeirC Skew NumUp NumDn MinLoCord MaxHiCord MaxSubmerge Is_Ogee
14,22,3,0, 60, 60, , , , 0, 1,1,,
  4244.8  4249.5  4256.9  4269.6  4276.9  4292.1  4304.8  4330.8  4343.3  4353.8
  4364.7  4431.9  4503.2  4515.7  4559.2  4587.1  4603.1  4611.4  4681.5  4694.4
  4717.7  4727.7  4732.4  4745.6  4749.2  4778.9  4791.7  4801.6  4817.5  4870.6
  4886.1  4895.2  4910.4    4980    4980    5020    5020  5094.3  5105.3  5159.1
  5172.5    5188  5203.3  5226.4  5263.8  5271.3  5305.1  5313.6  5350.5  5398.8
  5406.3  5435.4  5461.5  5521.8  5654.5  5677.1  5715.2  5717.5  5733.2  5759.1
  915.75  914.83  914.87  911.54  910.73  906.13   904.4  891.93  893.42  890.47
  890.96  890.81  890.09  889.49  889.37   888.4  888.73  887.78  886.31  885.16
  885.46  884.52  883.39  883.21  883.63  882.79  881.59  881.36  882.02  880.42
  880.81  880.14     880     880     880     880     880     880  880.57  881.32
  882.63  882.32  883.37  884.08  886.81  886.63  889.36  889.29  892.43  895.69
  896.63  898.25  900.62  903.83  914.83  917.72  920.38  921.46  922.23  924.45
  847.93  847.93  847.93  847.93  847.93  847.93  847.93  847.93  847.93  847.93
  847.93  847.93  847.93  847.93  847.93  847.93  847.93  847.93  847.93  847.93
  847.93  847.93  847.93  847.93  847.93  847.93  847.93  847.93  847.93  847.93
  847.93  847.93  847.93  847.93     878     878  847.93  847.93  847.93  847.93
  847.93  847.93  847.93  847.93  847.93  847.93  847.93  847.93  847.93  847.93
  847.93  847.93  847.93  847.93  847.93  847.93  847.93  847.93  847.93  847.93
  4244.8  4249.5  4256.9  4269.6  4276.9  4292.1  4304.8  4330.8  4343.3  4353.8
  4364.7  4431.9  4503.2  4515.7  4559.2  4587.1  4603.1  4611.4  4681.5  4694.4
  4717.7  4727.7  4732.4  4745.6  4749.2  4778.9  4791.7  4801.6  4817.5  4870.6
  4886.1  4895.2  4910.4    4980    4980    5020    5020  5094.3  5105.3  5159.1
  5172.5    5188  5203.3  5226.4  5263.8  5271.3  5305.1  5313.6  5350.5  5398.8
  5406.3  5435.4  5461.5  5521.8  5654.5  5677.1  5715.2  5717.5  5733.2  5759.1
  915.75  914.83  914.87  911.54  910.73  906.13   904.4  891.93  893.42  890.47
  890.96  890.81  890.09  889.49  889.37   888.4  888.73  887.78  886.31  885.16
  885.46  884.52  883.39  883.21  883.63  882.79  881.59  881.36  882.02  880.42
  880.81  880.14     880     880     880     880     880     880  880.57  881.32
  882.63  882.32  883.37  884.08  886.81  886.63  889.36  889.29  892.43  895.69
  896.63  898.25  900.62  903.83  914.83  917.72  920.38  921.46  922.23  924.45
  847.93  847.93  847.93  847.93  847.93  847.93  847.93  847.93  847.93  847.93
  847.93  847.93  847.93  847.93  847.93  847.93  847.93  847.93  847.93  847.93
  847.93  847.93  847.93  847.93  847.93  847.93  847.93  847.93  847.93  847.93
  847.93  847.93  847.93  847.93     878     878  847.93  847.93  847.93  847.93
  847.93  847.93  847.93  847.93  847.93  847.93  847.93  847.93  847.93  847.93
  847.93  847.93  847.93  847.93  847.93  847.93  847.93  847.93  847.93  847.93
Abutment Skew #Up #Dn= , 2 , 2
    4980  4981.5
     878   875.8
    4980  4981.5
     878   873.7
Abutment Skew #Up #Dn= , 2 , 2
  5018.5    5020
  871.83     878
  5018.5    5020
  871.79     878
BR Coef= 1 , 1 , 0 ,1.25, 0 ,,,0.8,0,2,0,
WSPro=,,,, 1 ,,,, 0 ,,,, 0 ,,,,-1 ,-1 ,-1 , 0 , 0 , 0 , 0 , 0
BC Design=,, 0 ,, 0 ,,,,,,
BC HTab HWMax=925.68

Type RM Length L Ch R = 1 ,1450    ,452,452,452
BEGIN DESCRIPTION:
Hunting_Crk_XS4
END DESCRIPTION:
XS GIS Cut Line= 6
       1154502.2       616801.46      1154397.48       616848.58
      1154325.93       617204.63      1154243.89       617363.46
      1154130.45       617466.43      1153523.07       617817.25
#Sta/Elev= 30
  4229.3   911.9  4301.2  890.23  4342.1  888.85  4369.6  890.65  4379.3  888.52
  4401.4  890.64  4453.4  890.15  4522.3  885.79  4533.6  887.97  4606.4  886.16
  4659.3  887.89    4747  876.15  4977.3  875.92    4985  870.68  4986.5  867.68
  5013.5  867.68    5015  870.68  5037.3  877.02  5108.1  875.13    5199  876.88
  5303.8  883.12  5325.8  890.96  5379.4  895.82  5459.4  900.58  5510.2   898.7
  5541.4  904.17  5561.5  903.49  5573.8  907.77  5631.5  913.94  5746.9  931.29
#Mann= 3 ,-1 , 0
  4229.3     .09       0    4985     .05       0    5015     .09       0
#XS Ineff= 2 , 0
       0    4959     880    5041       0     880
Permanent Ineff=
       F       F
Bank Sta=4985,5015
Exp/Cntr=0.5,0.3

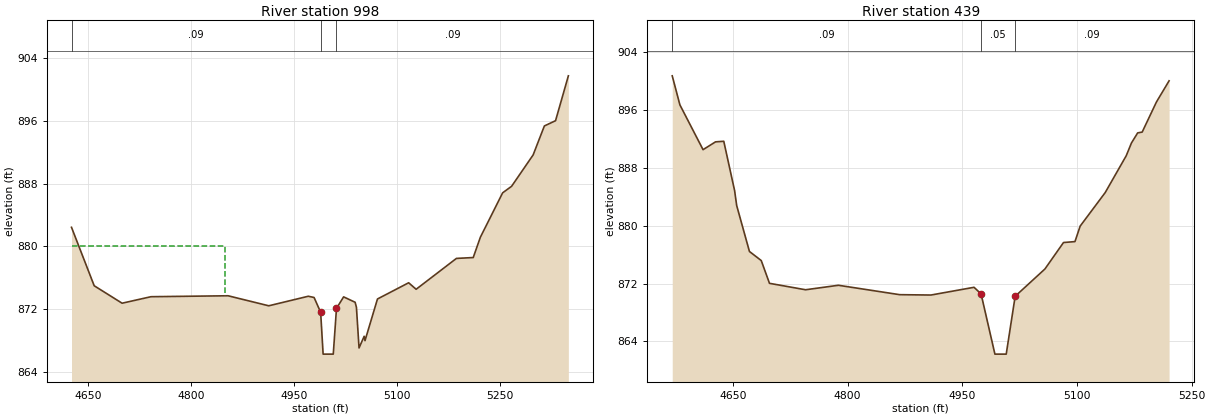
Type RM Length L Ch R = 1 ,998     ,559,559,559
BEGIN DESCRIPTION:
Hunting_Crk_XS6
END DESCRIPTION:
XS GIS Cut Line= 6
 1154337.9836638  617034.5367016      1153964.62       617068.56
      1153819.99       617051.91      1153748.11       617049.28
      1153708.67       617020.35 1153632.1425656  616989.1393967
#Sta/Elev= 30
  4625.5  882.44  4658.6  874.98  4699.3  872.75  4741.4  873.58  4853.9   873.7
  4913.3  872.42    4971  873.64  4979.4  873.48    4989  871.59  4992.6  866.25
  5007.4  866.25  5012.1  872.09  5022.5  873.56  5039.3  872.87  5041.2  872.23
    5045  867.04  5052.5  868.53  5053.7  867.97  5071.9  873.29  5117.4  875.36
  5128.3  874.53  5187.1  878.47  5211.6  878.58    5222  881.17  5254.5  886.84
  5267.6  887.68    5299  891.68  5315.4  895.38  5331.7  896.05  5350.4  901.78
#Mann= 3 ,-1 , 0
  4625.5     .09       0    4989     .05       0  5012.1     .09       0
#XS Ineff= 2 , 0
       0    4850     880               0
Permanent Ineff=
       F       F
Bank Sta=4989,5012.1
Exp/Cntr=0.3,0.1

Type RM Length L Ch R = 1 ,439     ,0,0,0
BEGIN DESCRIPTION:
Hunting_Crk_XS1
END DESCRIPTION:
XS GIS Cut Line= 6
       1154526.6       616727.99      1154390.83       616654.67
      1154149.17       616594.94      1154081.29       616597.65
      1153972.67       616603.08      1153904.79       616619.37
#Sta/Elev= 30
  4570.6  900.72  4580.6  896.71  4610.9  890.51  4627.2  891.59    4638  891.67
  4652.2  884.84  4654.9  882.78  4671.6  876.43    4687  875.18  4697.8  872.03
    4745  871.14  4787.9  871.76  4868.1  870.46  4908.9  870.41  4965.3  871.48
  4974.5  870.57  4992.6  862.24  5007.4  862.24  5019.1  870.24    5058  874.01
  5082.3  877.67  5097.3   877.8  5104.1  879.94  5136.8  884.57  5164.4  889.68
  5171.1  891.42  5179.3  892.83  5185.2  892.94  5203.9  897.11  5220.4  900.03
#Mann= 3 ,-1 , 0
  4570.6     .09       0  4974.5     .05       0  5019.1     .09       0
Bank Sta=4974.5,5019.1
Exp/Cntr=0.3,0.1

Chan Stop Cuts=-1
Use User Specified Reach Order=0
User Specified Reach Order=Hunting Creek   ,Reach-1