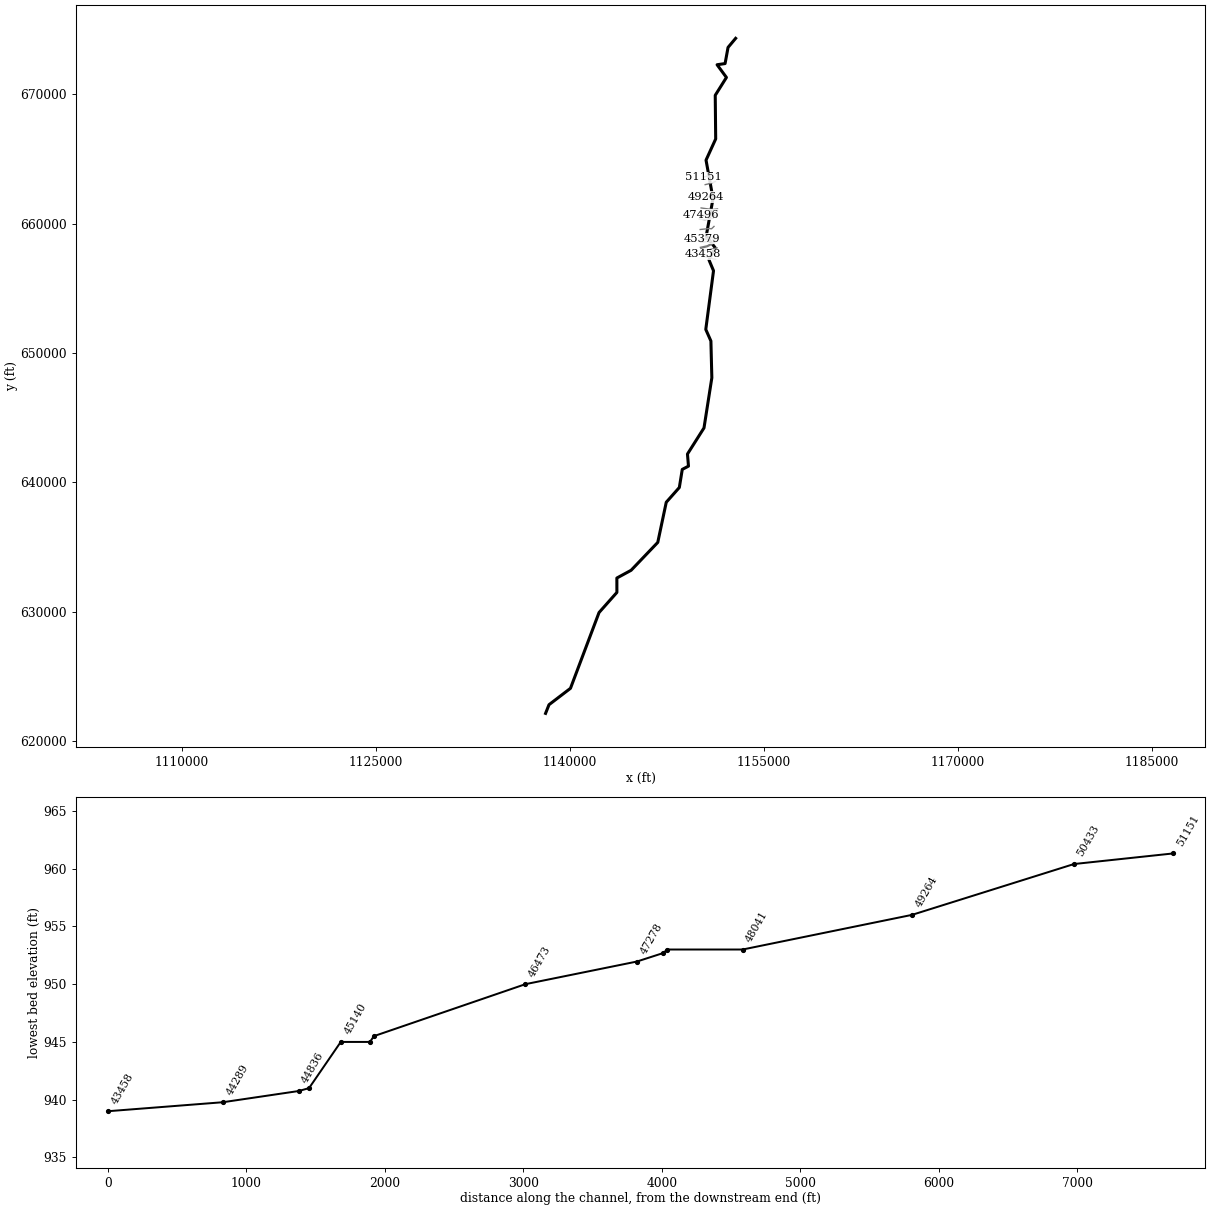
--- lds_cane_crk.prj (project) ---

Proj Title=Cane Creek Limited Detail Study
Current Plan=p01
Default Exp/Contr=0.3,0.1
English Units
Geom File=g01
Flow File=f01
Plan File=p01
Y Axis Title=Elevation
X Axis Title(PF)=Main Channel Distance
X Axis Title(XS)=Station
BEGIN DESCRIPTION:
Cane Creek
END DESCRIPTION:
DSS Export Rating Curves= 0
DSS Export Rating Curve Sorted= 0
DSS Export Volume Flow Curves= 0
DXF OffsetX= 0
DXF OffsetY= 0
DXF ScaleX= 1
DXF ScaleY= 10

--- lds_cane_crk.p01 (plan) ---

Plan Title=Floodway Run
Program Version=3.13
Short Identifier=Floodway
Geom File=g01
Flow File=f01
Subcritical Flow
K Sum by GR= 0
Std Step Tol= 0.01
Critical Tol= 0.01
Num of Std Step Trials= 20
Max Error Tol= 0.3
Flow Tol Ratio= 0.001
Split Flow NTrial= 30
Split Flow Tol= 0.02
Split Flow Ratio= 0.02
Log Output Level= 0
Friction Slope Method= 1
Unsteady Friction Slope Method= 2
Unsteady Bridges Friction Slope Method= 1
Parabolic Critical Depth
Global Vel Dist= 0 , 0 , 0
Global Log Level= 0
CheckData=True
Encroach Param=-1 ,10,10, 2
Encroach River=Cane Creek
Encroach Reach=Reach-1
Encroach Node=51151
       1  4955.4  5085.4
Encroach Node=50433
       1    4925  5271.6
Encroach Node=49264
       1    4900    5180
Encroach Node=48041
       1    4900    5170
Encroach Node=47496
       1    4900    5120
Encroach Node=47469
       1    4950    5120
Encroach Node=47278
       1  4962.1 5213.11
Encroach Node=46473
       1 4954.37 5274.41
Encroach Node=45379
       1    4930    5070
Encroach Node=45351
       1    4945    5075
Encroach Node=45140
       1    4935    5035
Encroach Node=44911
       1    4905    5070
Encroach Node=44836
       1    4934    5070
Encroach Node=44289
       1    4970  5152.9
Encroach Node=43458
       1  4970.3  5186.7
Encroach Node=43145
       1  4954.7    5050
Encroach Node=43104
       1  4953.7  5044.9
Encroach Node=42611
       4      .7
Encroach Node=41993
       1 4875.84    5024
Encroach Node=41581
       1    4785    5029
Encroach Node=41556
       1    4800  5030.4
Encroach Node=41227
       1 4784.09  5026.1
Encroach Node=40551
       1    4850    5030
Encroach Node=40282
       1    4920    5039
Encroach Node=40247
       1    4900  5026.7
Encroach Node=39874
       1    4880    5024
Encroach Node=39332
       1 4795.55    5020
Encroach Node=39300
       1  4796.4    5041
Encroach Node=38944
       1 4921.04 5117.85
Encroach Node=38333
       4      .7
Encroach Node=37622
       4      .7
Encroach Node=37412
       1    4870    5070
Encroach Node=37339
       1    4840    5060
Encroach Node=36712
       1 4924.32 5071.91
Encroach Node=36105
       4      .7
Encroach Node=35650
       4      .7
Encroach Node=35036
       1  4962.2    5200
Encroach Node=34998
       1  4973.7    5200
Encroach Node=34373
       1    4930    5090
Encroach Node=33217
       1  4967.8  5251.6
Encroach Node=32570
       1    4950  5164.5
Encroach Node=32528
       1    4950  5164.5
Encroach Node=32044
       1    4920    5180
Encroach Node=31619
       1    4950    5290
Encroach Node=31208
       1    4900    5220
Encroach Node=31175
       1    4910    5200
Encroach Node=30730
       1    4885    5200
Encroach Node=29694
       1    4800    5050
Encroach Node=28910
       1    4800    5100
Encroach Node=28500
       1  4936.5  5063.5
Encroach Node=28409
       1  4909.5  5027.2
Encroach Node=27871
       4      .7
Encroach Node=27124
       4      .7
Encroach Node=26548
       4      .7
Encroach Node=25802
       4      .7
Encroach Node=24714
       4      .7
Encroach Node=23624
       4      .7
Encroach Node=22071
       1    4669  5037.5
Encroach Node=20764
       4      .7
Encroach Node=19225
       4      .7
Encroach Node=17749
       4      .7
Encroach Node=16809
       4      .7
Encroach Node=16021
       4      .7
Encroach Node=15278
       4      .7
Encroach Node=14082
       1 4511.58  5029.1
Encroach Node=12866
       4      .7
Encroach Node=12054
       4      .7
Encroach Node=11150
       1 4829.52 5150.84
Encroach Node=10143
       1 4909.58 5318.72
Encroach Node=9758
       13991.9994198.001
Encroach Node=9669
       1    3992    4198
Encroach Node=8981
       4      .7
Encroach Node=7732
       4      .7
Encroach Node=6748
       1 4614.77 5214.73
Encroach Node=5723
       4      .7
Encroach Node=5264
       1    4900    5087
Encroach Node=5196
       1    4921  5038.6
Encroach Node=4434
       4      .7
Encroach Node=3688
       4      .7
Encroach Node=2835
       1    4630    5050
Encroach Node=2422
       4      .7
Encroach Node=1882
       4      .7
Encroach Node=1315
       4      .7
BEGIN DESCRIPTION:
Floodway Run
END DESCRIPTION:
Computation Interval=1HOUR
Output Interval=1HOUR
Run HTab= 0
Run UNet= 0
Run PostProcess= 0
UNET Theta= 1
UNET Theta Warmup= 1
UNET ZTol= 0.02
UNET ZSATol= 0.05
UNET MxIter= 20
UNET MaxInSteps= 0
UNET DtIC= 0
UNET DtMin= 0
UNET MaxCRTS= 20
UNET WFStab= 2
UNET SFStab= 1
UNET WFX= 1
UNET SFX= 1
UNET DSS MLevel= 4
UNET DZMax Abort= 100
UNET Convert EG Bridges=-1
UNET Use Existing IB Tables=-1
UNET Froude Reduction=False
UNET Froude Limit= 1
UNET Froude Power= 10
Instantaneous Interval=1HOUR
Write IC File= 0
Echo Input=False
Echo Output=False
Write Detailed= 0
Detailed Automatic Start=False, 10

--- lds_cane_crk.f01 (steady flow) ---

Flow Title=Floodway
Program Version=3.13
Number of Profiles= 2
Profile Names=100-year,100-FW
River Rch & RM=Cane Creek,Reach-1         ,51151
    3320    3320
River Rch & RM=Cane Creek,Reach-1         ,45379
    3540    3540
River Rch & RM=Cane Creek,Reach-1         ,43145
    3750    3750
River Rch & RM=Cane Creek,Reach-1         ,40551
    3960    3960
River Rch & RM=Cane Creek,Reach-1         ,34373
    4450    4450
River Rch & RM=Cane Creek,Reach-1         ,33217
    4930    4930
River Rch & RM=Cane Creek,Reach-1         ,31208
    5100    5100
River Rch & RM=Cane Creek,Reach-1         ,27124
    5280    5280
River Rch & RM=Cane Creek,Reach-1         ,26548
    5500    5500
River Rch & RM=Cane Creek,Reach-1         ,20764
    5650    5650
River Rch & RM=Cane Creek,Reach-1         ,19225
    5790    5790
River Rch & RM=Cane Creek,Reach-1         ,14082
    6100    6100
River Rch & RM=Cane Creek,Reach-1         ,11150
    6250    6250
River Rch & RM=Cane Creek,Reach-1         ,6748
    6410    6410
River Rch & RM=Cane Creek,Reach-1         ,3688
    6510    6510
Boundary for River Rch & Prof#=Cane Creek,Reach-1         , 1
Up Type= 0
Dn Type= 3
Dn Slope=0.002
Boundary for River Rch & Prof#=Cane Creek,Reach-1         , 2
Up Type= 0
Dn Type= 3
Dn Slope=0.002
DSS Import GetInterval= 0
DSS Import GetPeak= 0
DSS Import FillOption= 0

--- lds_cane_crk.g01 (geometry) ---

Geom Title=Existing Conditions
Program Version=3.13

River Reach=Cane Creek      ,Reach-1
Reach XY= 30
      1152811.63       674338.44      1152224.63       673637.06
       1151995.5       672387.06       1151377.5       672296.75
      1152099.63       671314.13      1151235.13       669932.19
      1151269.75       666557.19      1150523.25       664918.31
        1151065.       661946.06      1150536.88       659046.63
      1151227.88       658144.75      1150752.13       657195.06
        1151102.       656362.63      1150503.75       651822.13
      1150899.88       650927.94      1150972.25       648083.81
      1150365.63        644204.5      1149088.25       642186.25
      1149166.63       641250.13      1148686.75       640997.38
      1148459.63       639597.38      1147449.25       638456.75
        1146793.       635351.75      1144732.13       633194.63
       1143631.5       632595.63      1143634.13       631482.81
      1142254.75       629927.81      1140046.25       624065.44
      1138386.25       622797.19      1138121.38       622127.69

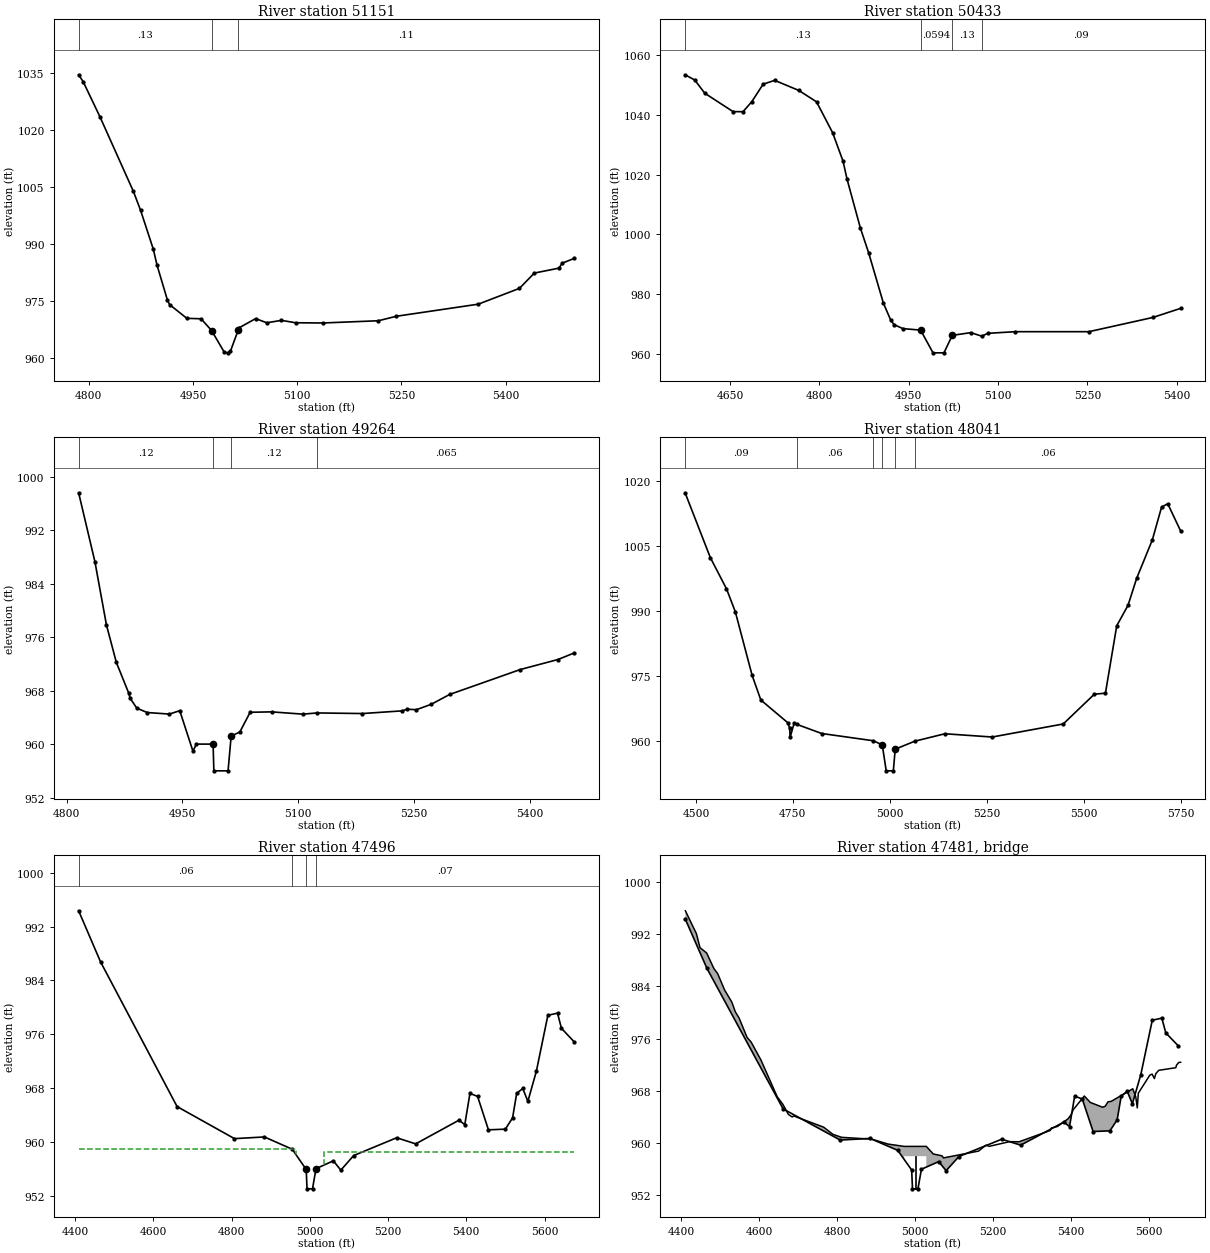
Type RM Length L Ch R = 1 ,51151   ,718,718,718
BEGIN DESCRIPTION:
Cane_Creek_XS-106      AMEC 51150.93
END DESCRIPTION:
XS GIS Cut Line= 3
      1150991.37         663897.      1150850.21       663775.44
 1150351.4497065  663605.5833056
#Sta/Elev= 30
  4785.4 1034.63 4792.03 1032.78 4815.94 1023.61 4864.09 1003.94 4874.52  998.92
  4892.8  988.69 4898.32  984.38 4913.05  975.32 4916.18  974.06 4941.08  970.42
 4961.59   970.3  4976.8  967.19 4994.96   961.5 4999.97  961.32 5003.78  961.71
 5015.16  967.36 5016.79  967.97 5040.14  970.34 5056.13  969.25 5077.32  969.88
 5097.67  969.25  5136.6  969.19 5216.83  969.78  5242.5  970.96  5360.6  974.15
 5419.84  978.32 5441.21  982.35 5476.61  983.65 5481.53  984.96 5498.59  986.22
#Mann= 3 , 0 , 0
  4785.4     .13       0  4976.8    .045       0 5015.16     .11       0
Bank Sta=4976.8,5015.16
Exp/Cntr=0.3,0.1

Type RM Length L Ch R = 1 ,50433   ,1169,1169,1169
BEGIN DESCRIPTION:
Cane_Creek_XS-105
END DESCRIPTION:
XS GIS Cut Line= 3
      1151252.33       663266.15      1150854.94       663114.21
      1150458.81       663022.15
#Sta/Elev= 30
  4574.5 1053.35  4590.7  1051.6  4607.6 1047.17    4655 1041.04  4671.7    1041
  4686.4 1044.33  4705.6 1050.21  4724.9 1051.48  4765.4 1048.12  4795.2 1044.31
  4822.2 1033.99  4839.7 1024.48  4846.4 1018.49  4868.9 1002.07  4882.8  993.78
  4907.5     977  4919.9  971.29  4925.8  969.77  4940.5  968.49    4970     968
  4990.8   960.4  5009.2   960.4  5023.1  966.24 5054.39  967.16 5072.66  965.96
 5082.77  966.92  5128.7  967.47  5252.5  967.47    5360  972.23  5406.6  975.27
#Mann= 4 ,-1 , 0
  4574.5     .13       0    4970   .0594       0  5023.1     .13       0
 5072.66     .09       0
Bank Sta=4970,5023.1
Exp/Cntr=0.3,0.1

Type RM Length L Ch R = 1 ,49264   ,1223,1223,1223
BEGIN DESCRIPTION:
Cane_Creek_XS-103
END DESCRIPTION:
XS GIS Cut Line= 4
      1151161.66       662050.65      1151010.36       662045.05
      1150950.96       662062.98      1150522.43       662069.85
#Sta/Elev= 30
  4815.6  997.59  4836.7  987.27  4851.7  977.79  4864.4  972.24  4880.6  967.59
  4882.3  966.86    4891  965.37  4904.5  964.72  4933.3  964.49  4946.6     965
  4963.7  958.94  4968.2     960  4989.8     960  4990.8     956  5009.2     956
  5013.2  961.19  5024.5  961.82  5037.8  964.76  5065.6  964.82  5106.2  964.48
  5124.6  964.66  5183.3  964.57  5234.6  964.97  5241.5  965.22    5253  965.14
  5272.4  965.95  5296.2  967.42  5387.7  971.15  5436.6  972.65  5457.6  973.63
#Mann= 4 ,-1 , 0
  4815.6     .12       0  4989.8    .059       0  5013.2     .12       0
  5124.6    .065       0
Bank Sta=4989.8,5013.2
Exp/Cntr=0.3,0.1

Type RM Length L Ch R = 1 ,48041   ,545,545,545
BEGIN DESCRIPTION:
Cane_Creek_XS-101
END DESCRIPTION:
XS GIS Cut Line= 4
      1151410.81       661142.29      1150994.15       661098.89
      1150807.52       661124.93      1150143.45       661220.42
#Sta/Elev= 30
    4472 1017.21  4537.1 1002.24  4578.7  995.05  4601.6  989.72  4644.9  975.05
  4667.4  969.35  4736.8  964.12  4741.9   962.8  4742.8  960.72  4753.2  963.96
  4759.9  963.74  4824.5  961.62  4957.4  959.95  4980.6     959  4990.8     953
  5009.2     953    5014     958  5064.6  959.85  5142.1  961.56  5264.2  960.81
  5447.4  963.82  5527.7   970.7  5556.3  970.93  5585.5  986.51  5614.6  991.23
    5637  997.49  5677.3 1006.33  5701.1  1013.9    5717 1014.68  5750.3 1008.39
#Mann= 6 ,-1 , 0
    4472     .09       0  4759.9     .06       0  4957.4     .07       0
  4980.6     .04       0    5014     .07       0  5064.6     .06       0
Bank Sta=4980.6,5014
Exp/Cntr=0.5,0.3

Type RM Length L Ch R = 1 ,47496   ,27,27,27
BEGIN DESCRIPTION:
Cane_Creek_XS-100
END DESCRIPTION:
XS GIS Cut Line= 6
       1151219.7       660599.26      1151105.81       660739.52
      1151047.07        660757.5      1150943.98       660652.01
       1150819.3       660590.87      1150098.83       660680.78
#Sta/Elev= 30
  4409.3  994.37  4465.3  986.77  4660.9  965.24  4807.5  960.47  4884.1  960.72
  4955.2  958.89  4990.9  955.88    4993     953    5007     953  5015.9     956
  5060.3  957.17  5079.3  955.78  5112.2  957.95  5222.1   960.6  5270.7  959.69
  5381.5  963.22  5396.1  962.54  5409.3  967.19  5428.8  966.76  5456.6  961.78
  5499.8  961.88  5518.3  963.56  5528.8  967.21  5544.3  967.93  5557.4  966.02
  5579.1   970.5  5608.5  978.82  5633.1  979.14  5643.2  976.88  5675.7  974.87
#Mann= 4 ,-1 , 0
  4409.3     .06       0  4955.2     .07       0  4990.9     .04       0
  5015.9     .07       0
#XS Ineff= 2 , 0
       0  4964.5  958.92  5035.5       0  958.52
Permanent Ineff=
       F       F
Bank Sta=4990.9,5015.9
Exp/Cntr=0.5,0.3

Type RM Length L Ch R = 3 ,47481   ,,,
BEGIN DESCRIPTION:
Cane_Creek_XS-99
Structure ID: Cane Creek Cove
Approximate Survey Structure
END DESCRIPTION:
Bridge Culvert--1,0,-1,-1, 0
Deck Dist Width WeirC Skew NumUp NumDn MinLoCord MaxHiCord MaxSubmerge Is_Ogee
7,16,3,0, 60, 60, , , , 0, 1,1,,
    4410  4438.3  4447.6  4464.7  4483.3  4492.8  4510.7  4529.3  4538.2  4547.9
  4568.3  4579.1  4604.3  4645.8  4660.1  4674.4  4684.3  4687.7  4765.1  4788.8
    4811  4888.9  4929.9  4971.5  4971.5  5028.5  5028.5  5046.3  5068.9  5072.7
  5162.6  5181.5    5190  5242.6  5266.8  5346.4  5349.7  5365.2  5392.2  5399.8
  5405.9  5434.1  5449.4  5480.8  5487.5  5495.1  5502.6  5558.4  5566.1    5570
  5572.7  5602.1  5608.1  5613.9  5617.7  5625.2  5668.9  5670.5  5676.4  5681.3
  995.58  992.08  989.93  989.11  986.72  985.97  983.45  981.59  980.11  979.16
   976.2  975.45  972.69   967.1  965.96   964.4     964  964.17  962.44  961.34
  960.89   960.6  959.86   959.5   959.5   959.5   959.5  958.34  958.05  957.74
  958.78  959.69  959.51  960.23  960.21  961.93  962.32  962.55  963.72  964.32
  965.14  967.21  966.23   965.5  965.64  966.34  966.38  968.32  967.09  965.39
  967.65   970.4  970.57  969.88  970.65  971.15  971.55  971.92  972.35  972.38
     931     931     931     931     931     931     931     931     931     931
     931     931     931     931     931     931     931     931     931     931
     931     931     931     931     958     958     931     931     931     931
     931     931     931     931     931     931     931     931     931     931
     931     931     931     931     931     931     931     931     931     931
     931     931     931     931     931     931     931     931     931     931
    4410  4438.3  4447.6  4464.7  4483.3  4492.8  4510.7  4529.3  4538.2  4547.9
  4568.3  4579.1  4604.3  4645.8  4660.1  4674.4  4684.3  4687.7  4765.1  4788.8
    4811  4888.9  4929.9  4971.5  4971.5  5028.5  5028.5  5046.3  5068.9  5072.7
  5162.6  5181.5    5190  5242.6  5266.8  5346.4  5349.7  5365.2  5392.2  5399.8
  5405.9  5434.1  5449.4  5480.8  5487.5  5495.1  5502.6  5558.4  5566.1    5570
  5572.7  5602.1  5608.1  5613.9  5617.7  5625.2  5668.9  5670.5  5676.4  5681.3
  995.58  992.08  989.93  989.11  986.72  985.97  983.45  981.59  980.11  979.16
   976.2  975.45  972.69   967.1  965.96   964.4     964  964.17  962.44  961.34
  960.89   960.6  959.86   959.5   959.5   959.5   959.5  958.34  958.05  957.74
  958.78  959.69  959.51  960.23  960.21  961.93  962.32  962.55  963.72  964.32
  965.14  967.21  966.23   965.5  965.64  966.34  966.38  968.32  967.09  965.39
  967.65   970.4  970.57  969.88  970.65  971.15  971.55  971.92  972.35  972.38
     931     931     931     931     931     931     931     931     931     931
     931     931     931     931     931     931     931     931     931     931
     931     931     931     931     958     958     931     931     931     931
     931     931     931     931     931     931     931     931     931     931
     931     931     931     931     931     931     931     931     931     931
     931     931     931     931     931     931     931     931     931     931
Pier Skew, UpSta & Num, DnSta & Num=  ,5000, 2 ,5000, 2 , 0 , 0 , 0 ,,
     1.5     1.5
     950     958
     1.5     1.5
     950     958
BR Coef= 1 , 1 , 0 ,1.25, 0 ,,,0.8,0,2,0,
WSPro=,,,, 1 ,,,, 0 ,,,, 0 ,,,,-1 ,-1 ,-1 , 0 , 0 , 0 , 0 , 0
BC Design=,, 0 ,, 0 ,,,,,,
BC HTab HWMax=994.37

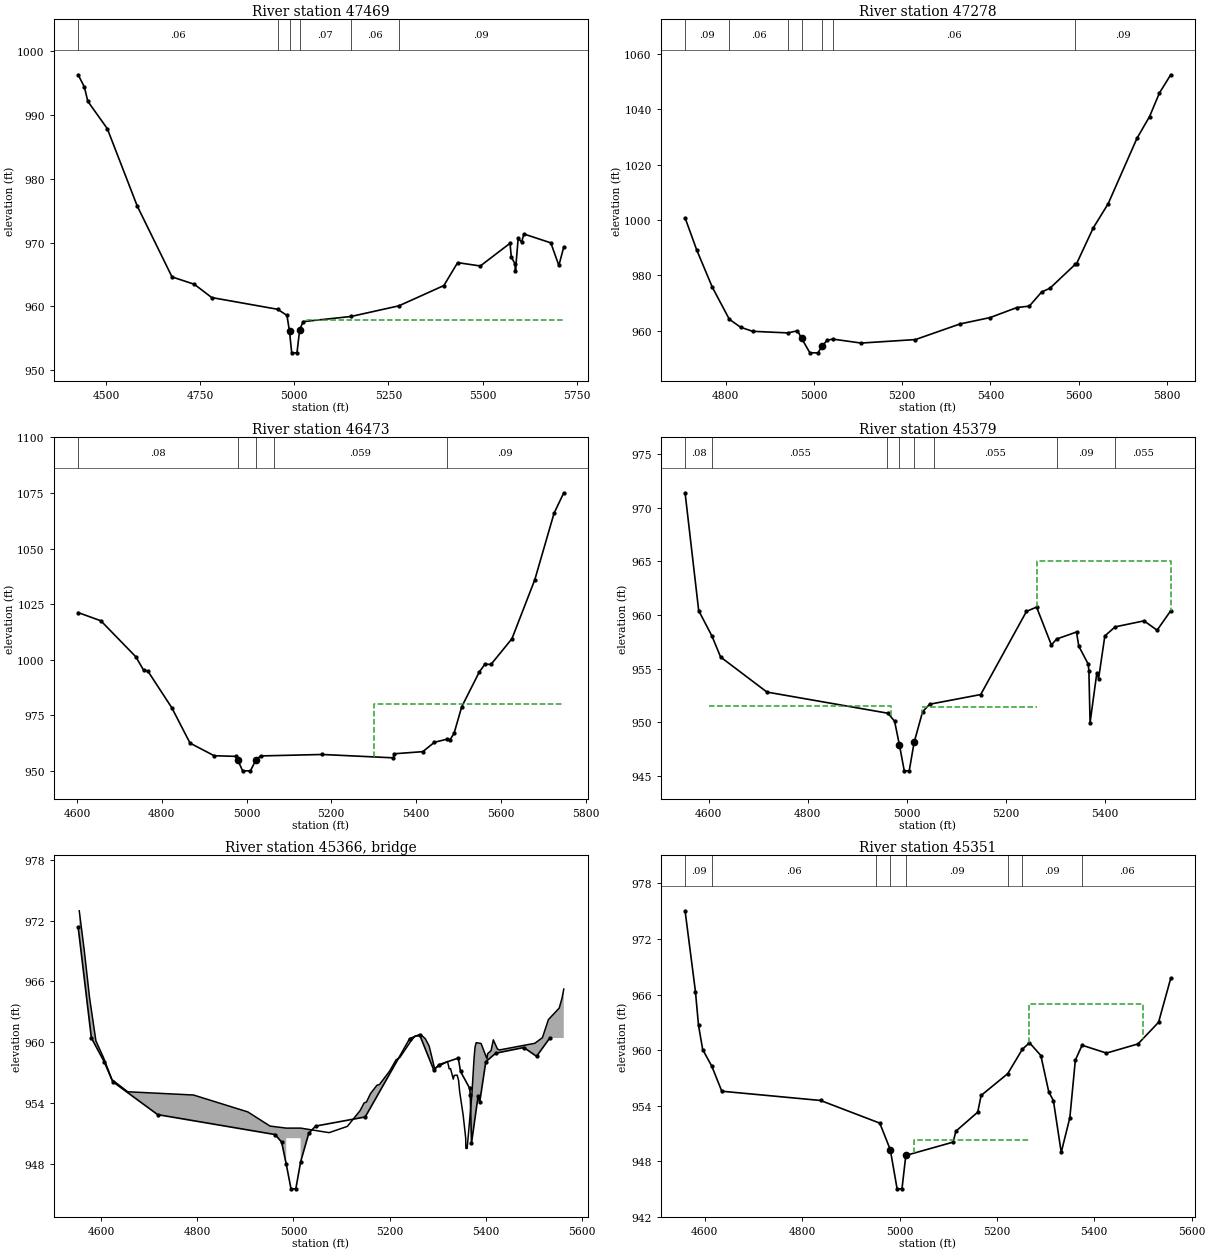
Type RM Length L Ch R = 1 ,47469   ,191,191,191
BEGIN DESCRIPTION:
Cane_Creek_XS-98
END DESCRIPTION:
XS GIS Cut Line= 6
      1151206.51       660566.89      1151049.47       660726.33
      1150965.55       660629.23      1150800.12       660565.69
      1150404.52       660604.05      1150058.07       660593.27
#Sta/Elev= 30
  4425.6  996.31  4442.1  994.41  4451.3  992.15  4503.1  987.86  4582.5  975.74
    4675  964.61  4734.4  963.45  4780.5  961.37  4955.7  959.53  4980.4  958.57
  4987.2  956.05    4993   952.7    5007   952.7  5014.2  956.34  5023.6   957.6
  5150.3   958.4  5277.7  960.07  5397.2  963.25  5433.9  966.85  5494.1  966.32
    5573  969.88  5576.5  967.74  5586.6  966.61  5587.5  965.57  5594.7  970.64
    5604  970.09  5609.8  971.34  5681.4  969.95  5702.8   966.4  5715.9  969.32
#Mann= 6 ,-1 , 0
  4425.6     .06       0  4955.7     .07       0  4987.2     .04       0
  5014.2     .07       0  5150.3     .06       0  5277.7     .09       0
#XS Ineff= 2 , 0
       0  4967.5  957.89  5032.5       0  957.89
Permanent Ineff=
       F       F
Bank Sta=4987.2,5014.2
Exp/Cntr=0.5,0.3

Type RM Length L Ch R = 1 ,47278   ,805,805,805
BEGIN DESCRIPTION:
Cane_Creek_XS-97
END DESCRIPTION:
XS GIS Cut Line= 5
      1151087.46       660419.64      1150861.77        660393.6
      1150748.92       660363.21      1150436.42       660315.47
      1149998.05       660363.21
#Sta/Elev= 30
  4707.8 1000.81  4734.1  989.22  4769.6  975.69    4808  964.14  4833.5  961.23
    4861  959.75  4941.1  959.17  4962.7  959.95  4972.1  957.19  4990.8  951.96
  5009.2  951.96  5018.6  954.46  5029.9  956.48  5042.2  956.94  5106.9   955.5
  5230.1  956.76  5331.4  962.42  5399.3  964.71  5460.4  968.36  5488.4  968.86
  5516.2  973.96  5535.1  975.33  5592.4  983.97  5595.5  984.21  5633.3  997.15
  5667.1 1005.89  5732.4 1029.56  5760.9 1037.42  5783.5 1046.01    5809 1052.56
#Mann= 7 ,-1 , 0
  4707.8     .09       0    4808     .06       0  4941.1     .09       0
  4972.1     .05       0  5018.6     .09       0  5042.2     .06       0
  5592.4     .09       0
Bank Sta=4972.1,5018.6
Exp/Cntr=0.3,0.1

Type RM Length L Ch R = 1 ,46473   ,1094,1094,1094
BEGIN DESCRIPTION:
Cane_Creek_XS-96
END DESCRIPTION:
XS GIS Cut Line= 4
      1151139.55        659790.3      1150948.57       659608.01
       1150735.9       659625.37      1150071.84       659551.58
#Sta/Elev= 30
  4602.8 1021.21  4656.4 1017.51  4738.9 1001.31    4757  995.38  4767.3  994.87
  4823.7   978.4  4866.8  962.47 4923.68   956.8 4974.58  956.51    4979     955
  4990.8     950  5009.2     950  5022.5     955 5033.43  956.71 5178.51  957.36
  5346.4  955.85  5348.4  957.68  5415.8  958.63  5443.2  962.84  5471.9   964.2
  5479.9  963.93  5489.6  966.88  5507.5  978.77  5549.2  994.53  5562.4  997.98
  5576.7  997.89  5626.1 1009.44    5680 1035.99  5725.5 1065.94  5748.4 1075.11
#Mann= 5 ,-1 , 0
  4602.8     .08       0    4979    .055       0  5022.5     .08       0
 5065.62    .059       0  5471.9     .09       0
#XS Ineff= 2 , 0
       0                    5300       0     980
Permanent Ineff=
       F       F
Bank Sta=4979,5022.5
Exp/Cntr=0.5,0.3

Type RM Length L Ch R = 1 ,45379   ,28,28,28
BEGIN DESCRIPTION:
Cane_Creek_XS-94
END DESCRIPTION:
XS GIS Cut Line= 6
       1151129.4        659005.9      1150663.86       658831.32
      1150625.07       658820.54      1150595.97       658821.62
      1150502.22       658841.02      1150184.32        658842.1
#Sta/Elev= 30
  4552.5  971.38    4580  960.41  4606.6  958.06  4624.3  956.09 4717.82  952.83
 4962.15  950.86  4975.5  950.11  4985.2  947.91    4995   945.5    5005   945.5
  5014.9  948.15 5031.99     951 5046.22   951.7 5149.28   952.6  5241.7  960.34
  5262.1  960.74  5291.9  957.22  5302.7  957.77  5342.7  958.42  5347.3   957.1
  5366.3  955.44  5367.7  954.79  5370.1  949.99  5383.8  954.63  5387.3  954.09
  5399.9  958.06  5420.7   958.9    5479  959.46  5505.4  958.59  5532.9   960.4
#Mann= 8 ,-1 , 0
  4552.5     .08       0  4606.6    .055       0 4960.71     .08       0
  4985.2     .04       0  5014.9     .08       0 5054.09    .055       0
  5302.7     .09       0  5420.7    .055       0
#XS Ineff= 3 ,-1
    4600    4968   951.5    5030  5262.1   951.4  5262.1    5600     965
Permanent Ineff=
       T       T       F
Bank Sta=4985.2,5014.9
Exp/Cntr=0.5,0.3

Type RM Length L Ch R = 3 ,45366   ,,,
BEGIN DESCRIPTION:
Cane_Creek_XS-93
Structure ID: Private Rd off of US 64#4
Approximate Survey Structure
END DESCRIPTION:
Bridge Culvert--1,0,-1,-1, 0
Deck Dist Width WeirC Skew NumUp NumDn MinLoCord MaxHiCord MaxSubmerge Is_Ogee
5.5,15,3,0, 60, 60, , , , 0, 1,1,,
  4554.8  4565.1  4576.2  4589.5  4605.1  4622.8  4655.6  4792.3  4905.2  4951.4
    4985    4985    5015    5015  5074.2  5112.1  5138.6    5147  5151.8  5160.5
  5173.7  5178.8  5200.2  5213.3  5221.3  5245.2  5253.3  5267.9  5274.3  5282.2
  5293.4  5320.3  5323.9  5326.6  5332.3  5334.3  5340.3  5343.3  5345.5  5352.9
  5358.1  5358.5  5361.1  5370.8  5375.4  5377.5  5379.9  5390.1  5402.2  5403.7
  5410.9  5415.5    5424  5428.1  5501.9  5517.6    5530  5552.5  5558.4    5562
  972.97  969.12   964.4  960.11  958.48  956.29  955.09  954.77   953.1   951.7
   951.5   951.5   951.5   951.5  951.05  951.67  953.23  953.99  954.08  954.93
  955.74   955.8  957.15  958.24  958.48  960.17  960.61   960.6  960.32   959.6
   957.4  958.08  957.35  957.37  956.34  956.71  956.73  956.22  955.11  952.76
  950.51   949.5  949.48  954.72  958.34   959.5  959.94  959.86  958.35  958.85
  959.16  960.22  959.32  959.22  959.88  960.44  962.22  963.36  964.35  965.24
  922.99  922.99  922.99  922.99  922.99  922.99  922.99  922.99  922.99  922.99
  922.99   950.5   950.5  922.99  922.99  922.99  922.99  922.99  922.99  922.99
  922.99  922.99  922.99  922.99  922.99  922.99  922.99  922.99  922.99  922.99
  922.99  922.99  922.99  922.99  922.99  922.99  922.99  922.99  922.99  922.99
  922.99  922.99  922.99  922.99  922.99  922.99  922.99  922.99  922.99  922.99
  922.99  922.99  922.99  922.99  922.99  922.99  922.99  922.99  922.99  922.99
  4554.8  4565.1  4576.2  4589.5  4605.1  4622.8  4655.6  4792.3  4905.2  4951.4
    4985    4985    5015    5015  5074.2  5112.1  5138.6    5147  5151.8  5160.5
  5173.7  5178.8  5200.2  5213.3  5221.3  5245.2  5253.3  5267.9  5274.3  5282.2
  5293.4  5320.3  5323.9  5326.6  5332.3  5334.3  5340.3  5343.3  5345.5  5352.9
  5358.1  5358.5  5361.1  5370.8  5375.4  5377.5  5379.9  5390.1  5402.2  5403.7
  5410.9  5415.5    5424  5428.1  5501.9  5517.6    5530  5552.5  5558.4    5562
  972.97  969.12   964.4  960.11  958.48  956.29  955.09  954.77   953.1   951.7
   951.5   951.5   951.5   951.5  951.05  951.67  953.23  953.99  954.08  954.93
  955.74   955.8  957.15  958.24  958.48  960.17  960.61   960.6  960.32   959.6
   957.4  958.08  957.35  957.37  956.34  956.71  956.73  956.22  955.11  952.76
  950.51   949.5  949.48  954.72  958.34   959.5  959.94  959.86  958.35  958.85
  959.16  960.22  959.32  959.22  959.88  960.44  962.22  963.36  964.35  965.24
  922.99  922.99  922.99  922.99  922.99  922.99  922.99  922.99  922.99  922.99
  922.99   950.5   950.5  922.99  922.99  922.99  922.99  922.99  922.99  922.99
  922.99  922.99  922.99  922.99  922.99  922.99  922.99  922.99  922.99  922.99
  922.99  922.99  922.99  922.99  922.99  922.99  922.99  922.99  922.99  922.99
  922.99  922.99  922.99  922.99  922.99  922.99  922.99  922.99  922.99  922.99
  922.99  922.99  922.99  922.99  922.99  922.99  922.99  922.99  922.99  922.99
Abutment Skew #Up #Dn= , 2 , 2
    4985  4986.5
     948  947.33
    4985  4986.5
     948  946.91
Abutment Skew #Up #Dn= , 2 , 2
  5013.5    5015
  947.57     948
  5013.5    5015
  948.86     948
BR Coef= 1 , 1 , 0 ,1.25, 0 ,,,0.8,0,2,0,
WSPro=,,,, 1 ,,,, 0 ,,,, 0 ,,,,-1 ,-1 ,-1 , 0 , 0 , 0 , 0 , 0
BC Design=,, 0 ,, 0 ,,,,,,
BC HTab HWMax=971.38

Type RM Length L Ch R = 1 ,45351   ,211,211,211
BEGIN DESCRIPTION:
Cane_Creek_XS-92
END DESCRIPTION:
XS GIS Cut Line= 6
      1151136.94       658973.57      1150750.08       658837.79
      1150660.63       658796.84      1150607.83       658788.21
      1150478.51       658810.84      1150174.62       658802.22
#Sta/Elev= 30
  4559.5  975.05  4580.8  966.32  4587.1  962.67  4595.7  960.05  4614.6  958.23
  4634.9  955.55  4837.7  954.55 4959.43   952.1    4981  949.23    4995     945
    5005     945  5012.9  948.61 5110.15  950.05 5115.71  951.23 5160.65  953.29
  5167.5  955.09  5222.3  957.45  5252.2  960.08  5266.9  960.79  5290.2  959.41
  5306.6  955.46    5316  954.54  5332.1  948.94  5349.8  952.69  5361.1  958.91
  5374.9  960.52    5425  959.67  5489.8  960.66    5532     963    5557  967.75
#Mann= 8 ,-1 , 0
  4559.5     .09       0  4614.6     .06       0  4951.4     .09       0
    4981     .04       0  5012.9     .09       0  5222.3     .06       0
  5252.2     .09       0  5374.9     .06       0
#XS Ineff= 3 ,-1
    4600    4968   950.3    5030  5266.9   950.3  5266.9    5500     965
Permanent Ineff=
       T       T       F
Bank Sta=4981,5012.9
Exp/Cntr=0.5,0.3

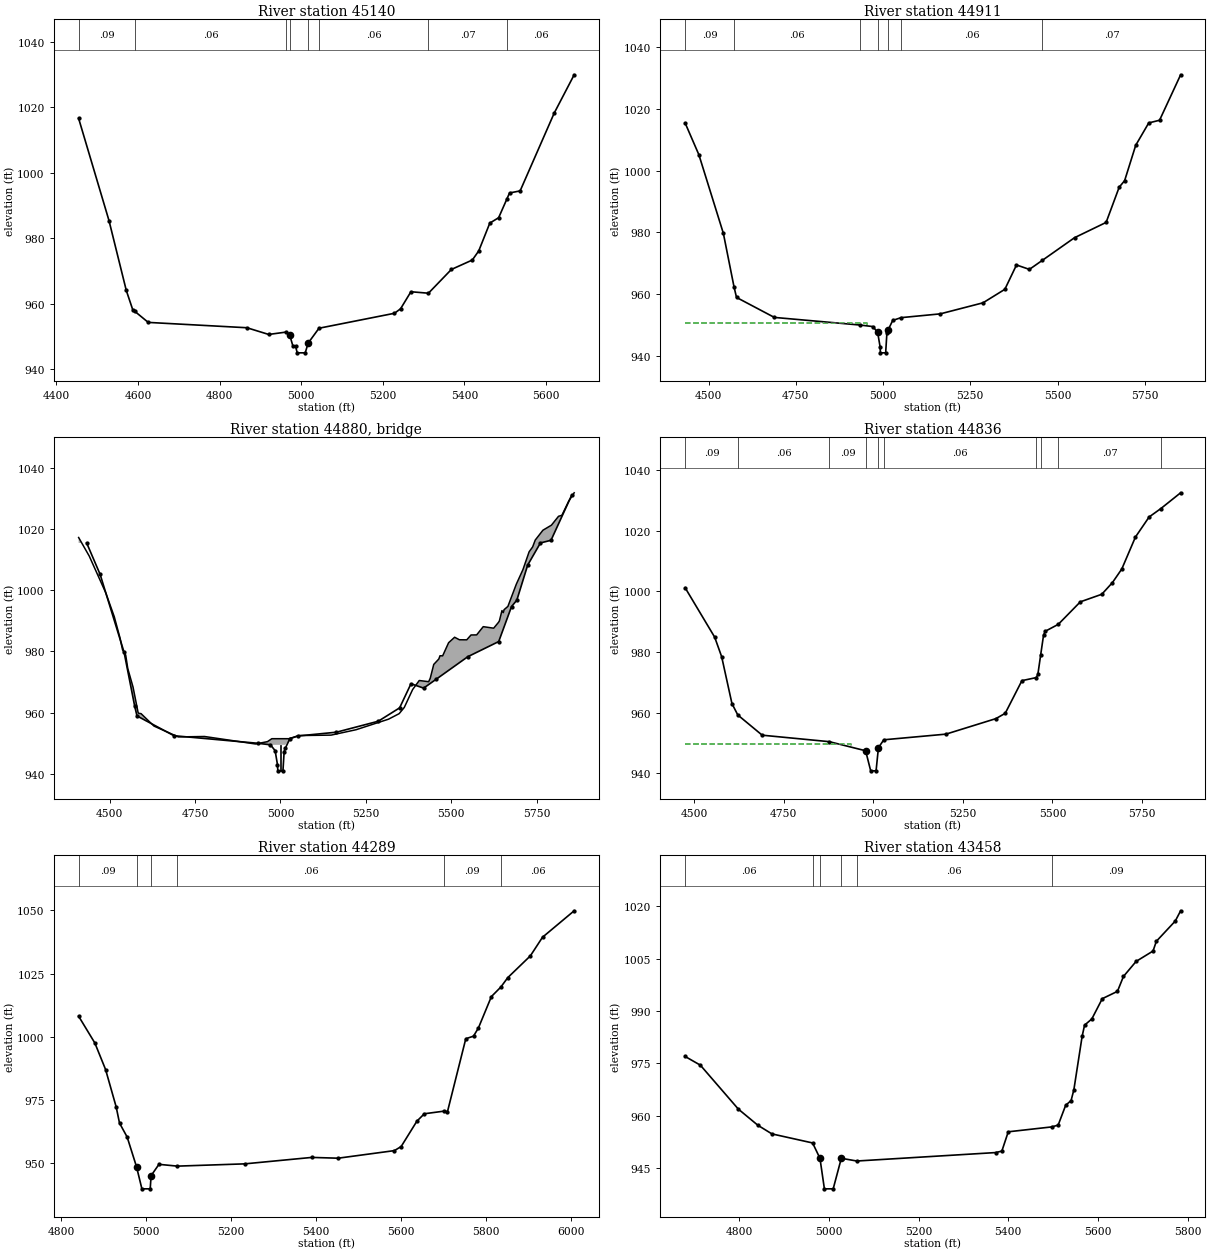
Type RM Length L Ch R = 1 ,45140   ,229,229,229
BEGIN DESCRIPTION:
Cane_Creek_XS-91
END DESCRIPTION:
XS GIS Cut Line= 4
       1151252.1        658875.3      1150853.93       658645.59
      1150693.14       658622.61      1150103.54       658569.02
#Sta/Elev= 30
  4454.6 1016.63    4529  985.41  4571.4  964.05  4587.3  958.13  4592.1  957.69
  4625.2   954.3 4866.91  952.67  4920.3  950.62  4963.5  951.35  4971.7   950.5
  4979.5  947.13  4986.1     947  4990.2     945  5009.8     945  5017.1     948
 5043.55  952.52  5228.5  957.09  5243.4  958.46  5268.8  963.67  5311.7  963.22
  5367.9  970.48  5419.2  973.36  5434.9  976.13  5462.1  984.65  5483.7  986.29
    5504  992.03  5510.4  993.85  5536.4  994.49  5619.9 1018.27  5668.8 1029.97
#Mann= 8 ,-1 , 0
  4454.6     .09       0  4592.1     .06       0  4963.5     .09       0
  4971.7     .04       0  5017.1     .09       0    5043     .06       0
  5311.7     .07       0    5504     .06       0
Bank Sta=4971.7,5017.1
Exp/Cntr=0.5,0.3

Type RM Length L Ch R = 1 ,44911   ,75,75,75
BEGIN DESCRIPTION:
Cane_Creek_XS-90
END DESCRIPTION:
XS GIS Cut Line= 6
      1151259.97        658840.1      1151158.59       658639.35
      1151081.53       658550.13      1150937.56       658475.11
      1150625.29       658292.61      1150085.92       658170.95
#Sta/Elev= 30
  4432.9 1015.44  4472.4 1005.14  4542.5   979.7  4573.2  962.29  4580.2  958.94
  4688.6  952.47  4934.3     950    4971   949.5  4984.6  947.59  4991.5     943
  4992.5     941  5007.5     941    5011   947.3  5014.6  948.43  5027.7  951.49
  5051.3  952.39    5164  953.62  5286.5   957.2    5349  961.57  5382.3  969.45
  5419.3  968.02  5456.3  970.94  5548.6  978.28  5639.1  983.23  5676.6  994.65
  5692.1  996.74  5723.9  1008.2  5761.2 1015.44  5792.2 1016.31  5852.6 1031.03
#Mann= 7 ,-1 , 0
  4432.9     .09       0  4573.2     .06       0  4934.3     .09       0
  4984.6    .045       0  5014.6     .09       0  5051.3     .06       0
  5456.3     .07       0
#XS Ineff= 2 , 0
       0    4953   950.5  5048.5       0   951.5
Permanent Ineff=
       F       F
Bank Sta=4984.6,5014.6
Exp/Cntr=0.5,0.3

Type RM Length L Ch R = 3 ,44880   ,,,
BEGIN DESCRIPTION:
Cane_Creek_XS-89
Structure ID: Private Dr off of US 64 #3
Approximate Survey Structure
END DESCRIPTION:
Bridge Culvert--1,0,-1,-1, 0
Deck Dist Width WeirC Skew NumUp NumDn MinLoCord MaxHiCord MaxSubmerge Is_Ogee
23.5,15,3,0, 60, 60, , , , 0, 1,1,,
  4409.4  4440.5  4488.7  4513.7  4530.5    4538  4547.2  4553.3  4568.7  4583.4
    4585  4592.2    4630    4701  4777.9  4927.2  4962.1    4975    4975    5025
    5025  5054.1  5148.5  5221.5  5316.4  5347.7  5362.7  5387.1  5406.5    5434
  5438.7  5448.9  5463.8  5467.2    5475  5492.4    5510    5524  5545.6    5558
  5574.5  5593.8  5624.3  5638.4  5640.9  5648.6  5652.5  5654.8    5666  5690.6
    5710  5728.1  5738.4  5746.1  5768.6  5793.4  5814.2    5824  5844.2    5860
 1017.22 1011.14  999.18  991.36  984.41  980.51  978.82  974.41  968.36   960.1
  959.81  959.68  955.62  952.08  952.22  949.77  950.54   951.5   951.5   951.5
   951.5  952.52  952.67  954.43  957.87  959.68  961.71  967.55  970.51  970.12
  971.25  975.76  977.54  978.59  978.57  982.85  984.64  983.82   983.8  985.38
  985.41   988.1   987.6   989.5  989.93  993.34  992.69  993.64  994.72 1001.97
 1006.73 1012.55 1014.14  1016.4 1019.61 1021.25 1024.15 1024.47 1029.12 1031.83
     921     921     921     921     921     921     921     921     921     921
     921     921     921     921     921     921     921     921   949.5   949.5
     921     921     921     921     921     921     921     921     921     921
     921     921     921     921     921     921     921     921     921     921
     921     921     921     921     921     921     921     921     921     921
     921     921     921     921     921     921     921     921     921     921
  4409.4  4440.5  4488.7  4513.7  4530.5    4538  4547.2  4553.3  4568.7  4583.4
    4585  4592.2    4630    4701  4777.9  4927.2  4962.1    4975    4975    5025
    5025  5054.1  5148.5  5221.5  5316.4  5347.7  5362.7  5387.1  5406.5    5434
  5438.7  5448.9  5463.8  5467.2    5475  5492.4    5510    5524  5545.6    5558
  5574.5  5593.8  5624.3  5638.4  5640.9  5648.6  5652.5  5654.8    5666  5690.6
    5710  5728.1  5738.4  5746.1  5768.6  5793.4  5814.2    5824  5844.2    5860
 1017.22 1011.14  999.18  991.36  984.41  980.51  978.82  974.41  968.36   960.1
  959.81  959.68  955.62  952.08  952.22  949.77  950.54   951.5   951.5   951.5
   951.5  952.52  952.67  954.43  957.87  959.68  961.71  967.55  970.51  970.12
  971.25  975.76  977.54  978.59  978.57  982.85  984.64  983.82   983.8  985.38
  985.41   988.1   987.6   989.5  989.93  993.34  992.69  993.64  994.72 1001.97
 1006.73 1012.55 1014.14  1016.4 1019.61 1021.25 1024.15 1024.47 1029.12 1031.83
     921     921     921     921     921     921     921     921     921     921
     921     921     921     921     921     921     921     921   949.5   949.5
     921     921     921     921     921     921     921     921     921     921
     921     921     921     921     921     921     921     921     921     921
     921     921     921     921     921     921     921     921     921     921
     921     921     921     921     921     921     921     921     921     921
Pier Skew, UpSta & Num, DnSta & Num=  ,5000, 2 ,5000, 2 , 0 , 0 , 0 ,,
       1       1
     940   949.5
       1       1
     940   949.5
BR Coef= 1 , 1 , 0 ,1.25, 0 ,,,0.8,0,2,0,
WSPro=,,,, 1 ,,,, 0 ,,,, 0 ,,,,-1 ,-1 ,-1 , 0 , 0 , 0 , 0 , 0
BC Design=,, 0 ,, 0 ,,,,,,
BC HTab HWMax=1031.03

Type RM Length L Ch R = 1 ,44836   ,547,547,547
BEGIN DESCRIPTION:
Cane_Creek_XS-88
END DESCRIPTION:
XS GIS Cut Line= 6
      1151361.36       658679.91       1150984.2       658414.28
      1150625.29       658231.78      1150495.52       658193.25
      1150308.97       658150.67      1150126.47       658087.81
#Sta/Elev= 30
  4474.2 1001.22  4556.8  984.89  4576.3  978.43    4605  962.98  4621.3   959.2
  4689.5  952.52  4876.9  950.38  4978.3  947.38  4992.5  940.75  5007.5  940.75
  5014.1  948.41  5029.1     951  5202.7  952.87  5342.1  957.99  5368.2  959.75
  5414.8  970.53  5454.9  971.54  5459.3  972.59  5467.2  979.07  5475.2  985.56
    5480  986.84  5516.3  989.12  5577.9  996.55  5637.8  999.05  5667.5  1002.9
  5693.7  1007.4  5731.8 1017.95    5770 1024.57  5802.8 1027.35    5858 1032.56
#Mann= 10 ,-1 , 0
  4474.2     .09       0  4621.3     .06       0  4876.9     .09       0
  4978.3     .05       0  5014.1     .09       0  5029.1     .06       0
  5454.9     .09       0  5467.2     .06       0  5516.3     .07       0
  5802.8     .06       0
#XS Ineff= 2 , 0
       0  4938.5   949.6  5061.5       0   949.6
Permanent Ineff=
       F       F
Bank Sta=4978.3,5014.1
Exp/Cntr=0.5,0.3

Type RM Length L Ch R = 1 ,44289   ,831,831,831
BEGIN DESCRIPTION:
Cane_Creek_XS-87
END DESCRIPTION:
XS GIS Cut Line= 5
      1151373.92       658134.48      1151139.55       658073.72
      1150827.05       657999.93      1150640.42       657973.89
      1150228.09       657921.81
#Sta/Elev= 30
  4841.2 1008.11  4879.4  997.52  4904.7     987  4929.6  972.23  4937.5  965.81
  4955.5  960.28  4977.6   948.5  4990.2  939.78  5009.8  939.78  5011.9     945
  5030.4  949.48  5073.7  948.77  5232.6  949.67  5390.4  952.22  5452.4  951.91
  5584.9  954.91  5600.9  956.53    5638  966.58  5655.5   969.5  5701.4  970.53
    5710  970.35  5753.1   999.2  5771.3 1000.23  5782.8 1003.45  5813.4 1015.89
  5835.6 1019.65    5852 1023.39  5905.2 1032.01  5933.8 1039.38  6008.4 1049.86
#Mann= 6 ,-1 , 0
  4841.2     .09       0  4977.6     .05       0  5011.9     .09       0
  5073.7     .06       0  5701.4     .09       0  5835.6     .06       0
Bank Sta=4977.6,5011.9
Exp/Cntr=0.3,0.1

Type RM Length L Ch R = 1 ,43458   ,313,313,313
BEGIN DESCRIPTION:
Cane_Creek_XS-86
END DESCRIPTION:
XS GIS Cut Line= 6
      1151269.76       657257.75      1151057.08       657270.77
      1150922.53       657366.25      1150653.44       657418.34
       1150401.7       657453.06      1150314.89       657631.01
#Sta/Elev= 30
  4679.8  976.97  4713.8  974.47  4798.5  961.86  4842.1  957.22  4873.2  954.76
  4963.9  952.16  4980.3  947.76  4990.2     939  5009.8     939  5027.9  947.76
  5062.5  946.98  5371.5   949.4  5385.6  949.82  5399.9  955.36  5496.6  956.76
  5511.1  957.28  5527.8  962.96  5539.9  964.32  5546.1  967.43  5564.5  982.74
  5569.9  985.94  5586.1  987.73  5609.4  993.54  5643.2  995.64  5656.6  999.92
  5684.8 1004.23  5722.5 1007.21  5729.9    1010    5772  1015.8    5784 1018.75
#Mann= 6 ,-1 , 0
  4679.8     .06       0  4963.9     .09       0  4980.3     .05       0
  5027.9     .09       0  5062.5     .06       0  5496.6     .09       0
Bank Sta=4980.3,5027.9
Exp/Cntr=0.5,0.3