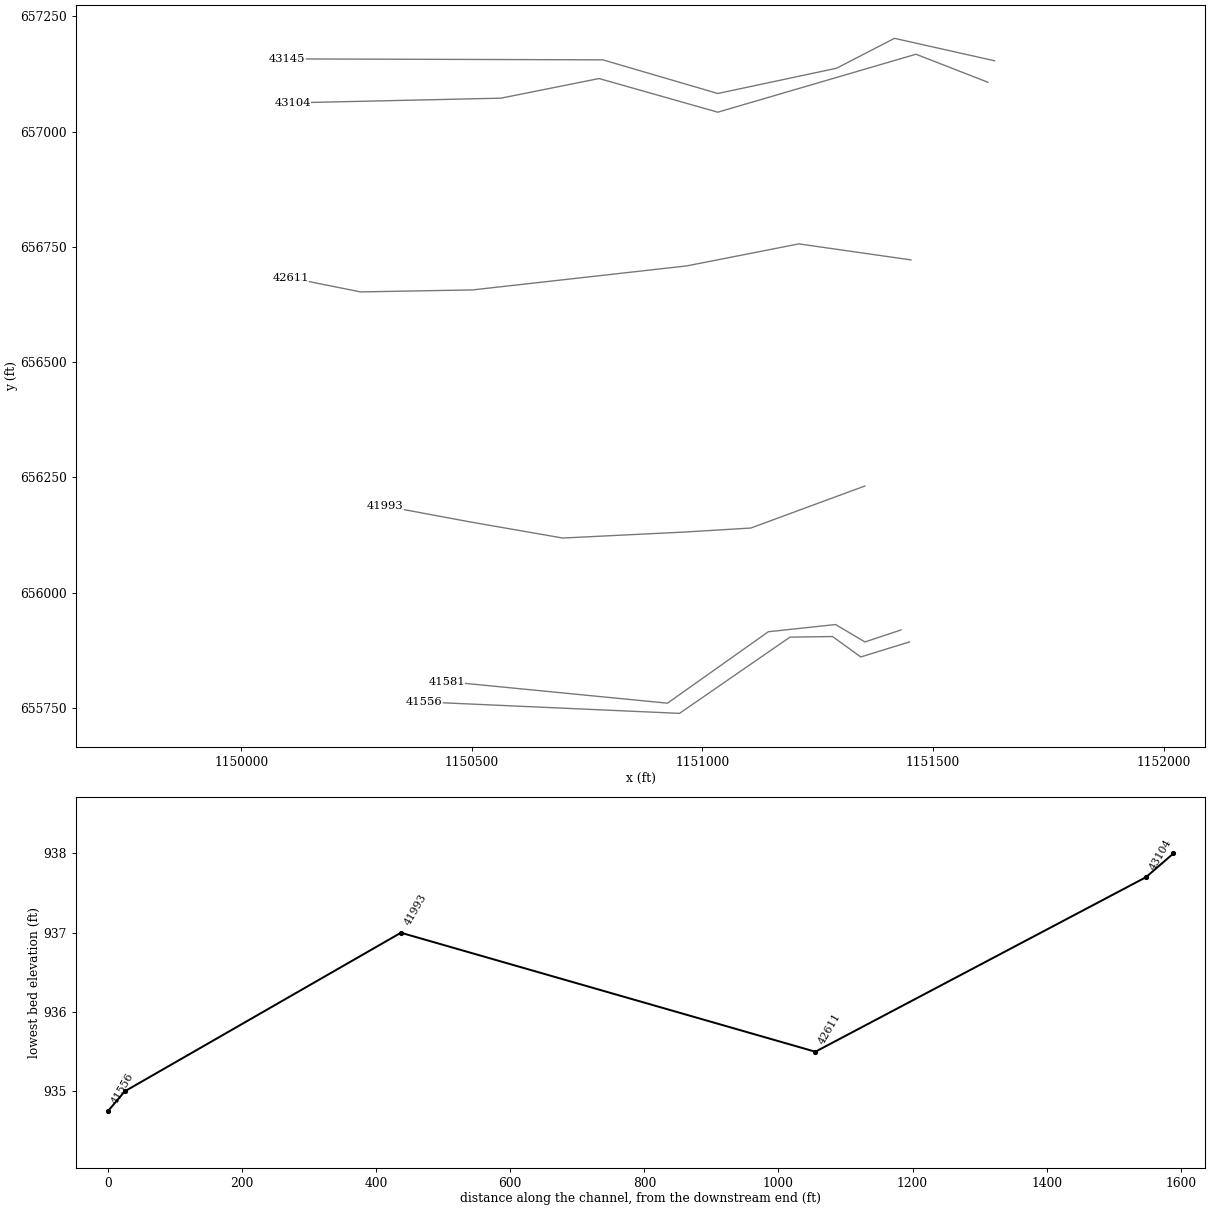
HEC-RAS study lds_cane_crk.prj: Cane Creek Limited Detail Study

--- lds_cane_crk.g01 (geometry) --- (continued)

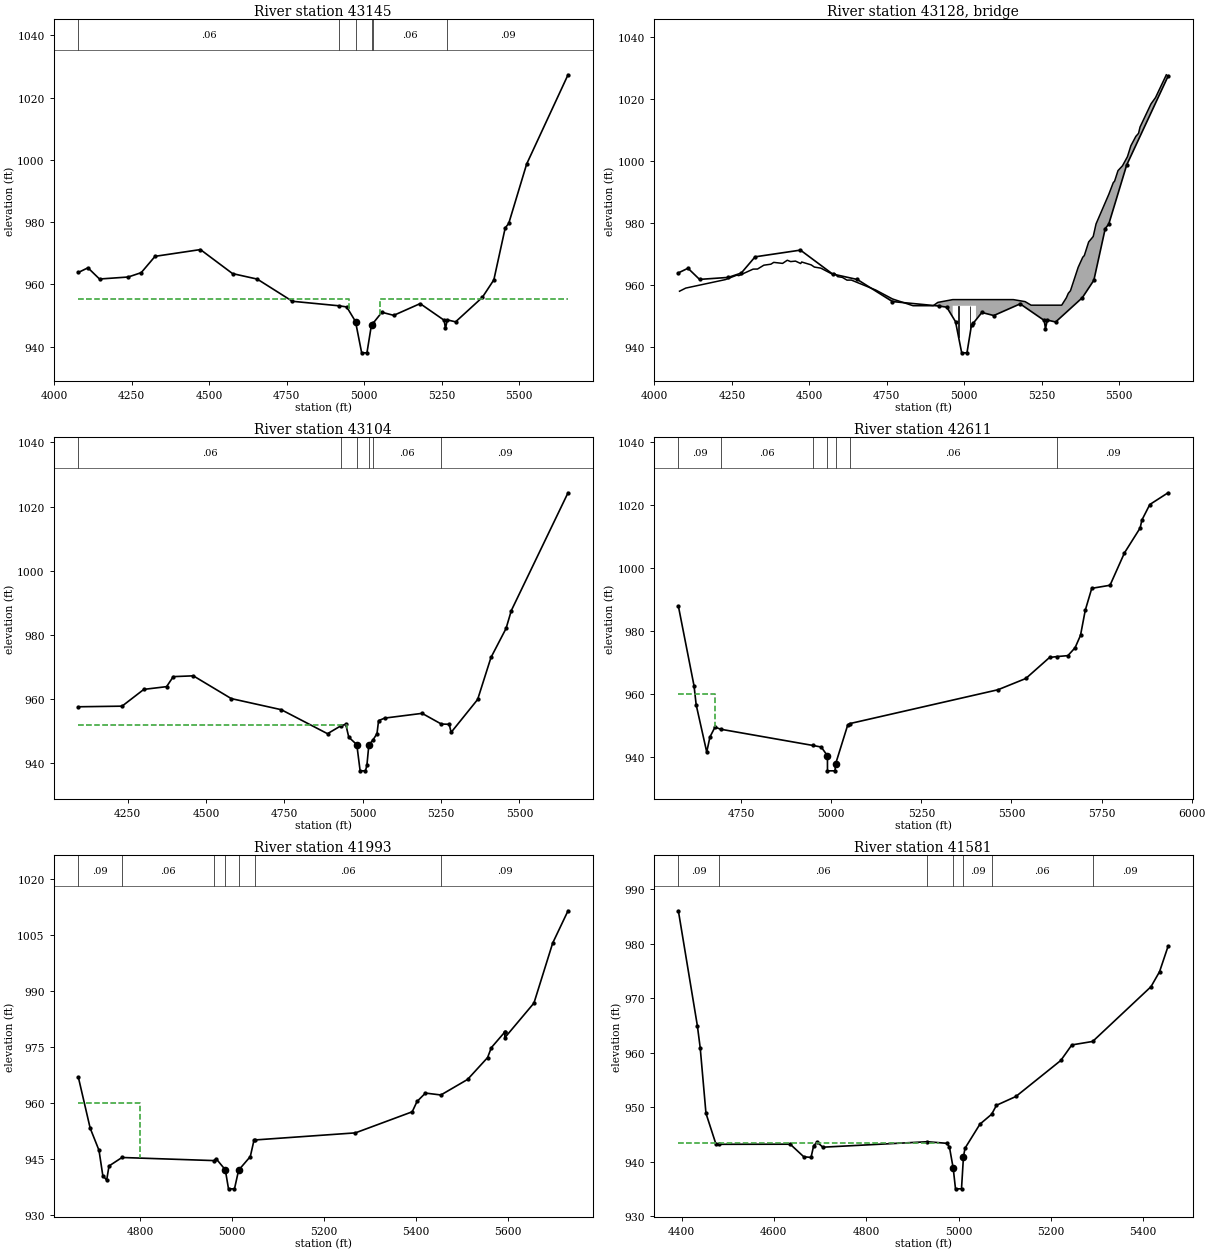
Type RM Length L Ch R = 1 ,43145   ,41,41,41
BEGIN DESCRIPTION:
Cane_Creek_XS-85
END DESCRIPTION:
XS GIS Cut Line= 6
      1151633.38       657153.63      1151416.42        657202.3
       1151290.7       657137.41      1151033.17       657082.66
      1150783.76       657155.66      1150098.39       657157.69
#Sta/Elev= 30
  4077.6  963.83  4108.6  965.33  4145.9  961.73  4238.4  962.37  4280.4  963.77
  4325.1  969.02  4471.4  971.19    4575  963.47  4654.7   961.7    4768  954.57
  4919.2  953.11  4943.3  952.75  4971.6  948.07  4991.5     938  5008.5     938
  5023.2  947.08  5028.6  947.55  5056.6  951.04  5094.9  950.05  5180.1  953.82
  5257.6  948.47  5261.7  945.83  5267.8  948.59  5294.4  947.96  5380.6  955.82
  5417.8  961.45  5454.5  978.16  5465.8  979.58  5523.7   998.7  5657.1 1027.37
#Mann= 6 ,-1 , 0
  4077.6     .06       0  4919.2     .09       0  4971.6    .052       0
  5023.2     .09       0  5028.6     .06       0  5267.8     .09       0
#XS Ineff= 2 , 0
       0    4950   955.2    5050       0   955.2
Permanent Ineff=
       F       F
Bank Sta=4971.6,5023.2
Exp/Cntr=0.5,0.3

Type RM Length L Ch R = 3 ,43128   ,,,
BEGIN DESCRIPTION:
Cane_Creek_XS-84
Structure ID: Cane Creek Mtn Rd
Approximate Survey Structure
END DESCRIPTION:
Bridge Culvert--1,0,-1,-1, 0
Deck Dist Width WeirC Skew NumUp NumDn MinLoCord MaxHiCord MaxSubmerge Is_Ogee
5.5,23,3,0, 60, 60, , , , 0, 1,1,,
  4081.3  4101.4  4229.5  4266.2  4272.4  4318.7    4333  4353.3    4376  4385.2
  4413.7    4429  4439.7  4455.4    4472  4475.4    4506  4516.3    4537  4576.3
  4581.4  4591.3  4606.5  4621.5  4635.6  4714.1  4768.4  4834.5  4899.4  4914.5
  4962.5  4962.5  5037.5  5037.5    5158    5196  5215.3    5314  5329.1  5335.3
  5342.3  5367.2  5381.9    5387    5401  5415.7  5424.8  5466.1  5480.3  5484.6
  5495.6    5510    5526  5537.1  5553.2  5561.9  5566.7  5602.1  5616.6  5651.5
  957.91  958.92  961.67   963.1  962.94  965.05  965.08  966.32  966.64  967.23
   966.9  967.92  967.48  967.64  966.86  967.35  966.42  965.71  965.37  963.31
  963.68  962.62  962.38  961.49  961.51   958.3  955.41  953.22  953.22   954.3
   955.2   955.2   955.2   955.2   955.2  954.55   953.4   953.4   955.8  957.23
  958.07  965.65  968.89  969.44  973.83   975.6  979.66  989.25  992.98  993.46
  996.87  998.43 1001.35  1004.9 1007.94 1008.92 1010.96 1018.44 1020.47 1027.84
   915.9   915.9   915.9   915.9   915.9   915.9   915.9   915.9   915.9   915.9
   915.9   915.9   915.9   915.9   915.9   915.9   915.9   915.9   915.9   915.9
   915.9   915.9   915.9   915.9   915.9   915.9   915.9   915.9   915.9   915.9
   915.9   953.2   953.2   915.9   915.9   915.9   915.9   915.9   915.9   915.9
   915.9   915.9   915.9   915.9   915.9   915.9   915.9   915.9   915.9   915.9
   915.9   915.9   915.9   915.9   915.9   915.9   915.9   915.9   915.9   915.9
  4081.3  4101.4  4229.5  4266.2  4272.4  4318.7    4333  4353.3    4376  4385.2
  4413.7    4429  4439.7  4455.4    4472  4475.4    4506  4516.3    4537  4576.3
  4581.4  4591.3  4606.5  4621.5  4635.6  4714.1  4768.4  4834.5  4899.4  4914.5
  4962.5  4962.5  5037.5  5037.5    5158    5196  5215.3    5314  5329.1  5335.3
  5342.3  5367.2  5381.9    5387    5401  5415.7  5424.8  5466.1  5480.3  5484.6
  5495.6    5510    5526  5537.1  5553.2  5561.9  5566.7  5602.1  5616.6  5651.5
  957.91  958.92  961.67   963.1  962.94  965.05  965.08  966.32  966.64  967.23
   966.9  967.92  967.48  967.64  966.86  967.35  966.42  965.71  965.37  963.31
  963.68  962.62  962.38  961.49  961.51   958.3  955.41  953.22  953.22   954.3
   955.2   955.2   955.2   955.2   955.2  954.55   953.4   953.4   955.8  957.23
  958.07  965.65  968.89  969.44  973.83   975.6  979.66  989.25  992.98  993.46
  996.87  998.43 1001.35  1004.9 1007.94 1008.92 1010.96 1018.44 1020.47 1027.84
   915.9   915.9   915.9   915.9   915.9   915.9   915.9   915.9   915.9   915.9
   915.9   915.9   915.9   915.9   915.9   915.9   915.9   915.9   915.9   915.9
   915.9   915.9   915.9   915.9   915.9   915.9   915.9   915.9   915.9   915.9
   915.9   953.2   953.2   915.9   915.9   915.9   915.9   915.9   915.9   915.9
   915.9   915.9   915.9   915.9   915.9   915.9   915.9   915.9   915.9   915.9
   915.9   915.9   915.9   915.9   915.9   915.9   915.9   915.9   915.9   915.9
Pier Skew, UpSta & Num, DnSta & Num=  ,4981.3, 2 ,4981.3, 2 , 0 , 0 , 0 ,0,0
       1       1
  942.39   953.2
       1       1
  940.65   953.2
Pier Skew, UpSta & Num, DnSta & Num=  ,5018.8, 2 ,5018.8, 2 , 0 , 0 , 0 ,0,0
       1       1
  944.37   953.2
       1       1
  942.45   953.2
BR Coef= 1 , 1 , 0 ,1.25, 0 ,,,0.8,0,2,0,
WSPro=,,,, 1 ,,,, 0 ,,,, 0 ,,,,-1 ,-1 ,-1 , 0 , 0 , 0 , 0 , 0
BC Design=,, 0 ,, 0 ,,,,,,
BC HTab HWMax=1027.37

Type RM Length L Ch R = 1 ,43104   ,493,493,493
BEGIN DESCRIPTION:
Cane_Creek_XS-83
END DESCRIPTION:
XS GIS Cut Line= 6
      1151619.19       657106.99      1151463.05       657167.82
      1151033.17        657042.1      1150775.65        657115.1
      1150562.74       657072.52      1150110.56       657062.38
#Sta/Elev= 30
  4092.2  957.66  4231.7  957.85  4301.3  963.08  4373.8  963.93  4395.2  967.05
  4459.1   967.3  4580.2  960.21  4739.8  956.75  4887.4  949.27  4931.2  951.79
  4945.7  952.18 4955.24  948.19  4980.9  945.86  4991.5   937.7  5008.5   937.7
  5013.1  939.38  5019.3  945.75 5032.79  947.36 5045.31  949.29  5050.4  953.34
  5069.8  954.13  5189.3  955.61  5250.6  952.28  5275.9   952.2  5281.9  949.68
  5366.5  959.93  5409.1  973.02  5457.3  982.08    5474  987.63    5655 1024.33
#Mann= 6 ,-1 , 0
  4092.2     .06       0  4931.2     .09       0  4980.9     .05       0
  5019.3     .09       0 5032.79     .06       0  5250.6     .09       0
#XS Ineff= 2 , 0
       0    4950     952    5050       0     952
Permanent Ineff=
       F       F
Bank Sta=4980.9,5019.3
Exp/Cntr=0.5,0.3

Type RM Length L Ch R = 1 ,42611   ,618,618,618
BEGIN DESCRIPTION:
Cane_Creek_XS-82
END DESCRIPTION:
XS GIS Cut Line= 6
      1151452.05       656721.72      1151208.99       656756.44
      1150965.94        656708.7      1150501.53       656656.62
      1150258.47       656652.28      1150106.56       656682.66
#Sta/Elev= 30
  4575.9  987.93  4619.4  962.53  4625.3  956.51  4654.6  941.48  4663.5  946.27
  4677.6  949.43  4693.1  948.74  4948.5  943.59  4972.3  943.07  4989.5   940.3
  4989.6   935.5  5010.4   935.5  5012.1  937.69  5045.5  949.99  5051.2  950.52
  5462.7   961.3  5539.9  964.88  5605.6  971.56  5625.9  971.85  5656.6  972.15
  5676.6  974.67  5691.6  978.61  5704.8  986.59  5722.8  993.56  5773.5  994.54
  5813.6 1004.85  5857.1 1012.77  5861.8 1015.26  5883.9 1020.23  5934.5 1023.96
#Mann= 7 ,-1 , 0
  4575.9     .09       0  4693.1     .06       0  4948.5     .09       0
  4989.5     .05       0  5012.1     .09       0  5051.2     .06       0
  5625.9     .09       0
#XS Ineff= 2 , 0
       0  4677.6     960               0
Permanent Ineff=
       F       F
Bank Sta=4989.5,5012.1
Exp/Cntr=0.3,0.1

Type RM Length L Ch R = 1 ,41993   ,412,412,412
BEGIN DESCRIPTION:
Cane_Creek_XS-81
END DESCRIPTION:
XS GIS Cut Line= 6
      1151352.22       656231.27      1151104.82       656140.12
       1150961.6       656131.44      1150696.84       656118.42
      1150497.19       656153.14      1150310.55       656187.87
#Sta/Elev= 30
  4665.5  966.89  4691.2  953.25  4710.4  947.32  4718.7  940.56  4727.1  939.33
  4732.2  943.12 4760.42  945.39 4960.39  944.56  4964.9  945.08    4985  942.11
    4992     937    5005     937    5014     942  5039.4  945.64  5047.5  950.07
  5050.4  950.09  5267.9  951.98  5391.4  957.62  5401.9  960.38  5420.2  962.63
  5453.8  962.12  5511.8  966.28  5555.3  972.13  5563.4  974.78  5592.3  978.91
  5592.6  978.94  5592.7  977.44  5656.1  986.72  5696.9  1002.8  5730.2 1011.42
#Mann= 7 ,-1 , 0
  4665.5     .09       0 4760.42     .06       0 4960.39     .09       0
    4985     .04       0    5014     .09       0  5050.4     .06       0
  5453.8     .09       0
#XS Ineff= 2 , 0
       0    4800     960               0
Permanent Ineff=
       F       F
Bank Sta=4985,5014
Exp/Cntr=0.5,0.3

Type RM Length L Ch R = 1 ,41581   ,25,25,25
BEGIN DESCRIPTION:
Cane_Creek_XS-80
END DESCRIPTION:
XS GIS Cut Line= 6
      1151430.57       655919.08      1151352.44       655893.03
      1151288.64       655930.79      1151142.81       655915.17
      1150924.06       655760.22      1150444.89        655807.1
#Sta/Elev= 30
  4393.1  986.01  4434.2  964.95  4440.4  960.89  4452.9  948.85  4474.6  943.18
  4480.4  943.17  4635.4  943.19  4664.7  940.89  4680.5  940.76  4686.3  942.95
  4693.9  943.56  4706.1  942.64 4932.53  943.64  4975.1  943.35 4980.43  942.64
  4988.6  938.75  4993.5     935  5006.5     935  5010.7  940.83 5014.04  942.44
 5046.48  946.87 5071.74  948.68  5082.3  950.33  5124.3  951.94  5221.6  958.55
  5245.5   961.4  5290.7  962.04    5417  972.08  5435.6  974.84    5454  979.49
#Mann= 7 ,-1 , 0
  4393.1     .09       0  4480.4     .06       0 4932.53     .09       0
  4988.6     .04       0  5010.7     .09       0 5071.74     .06       0
  5290.7     .09       0
#XS Ineff= 2 , 0
       0    4958   943.5    5042       0     945
Permanent Ineff=
       F       F
Bank Sta=4988.6,5010.7
Exp/Cntr=0.5,0.3

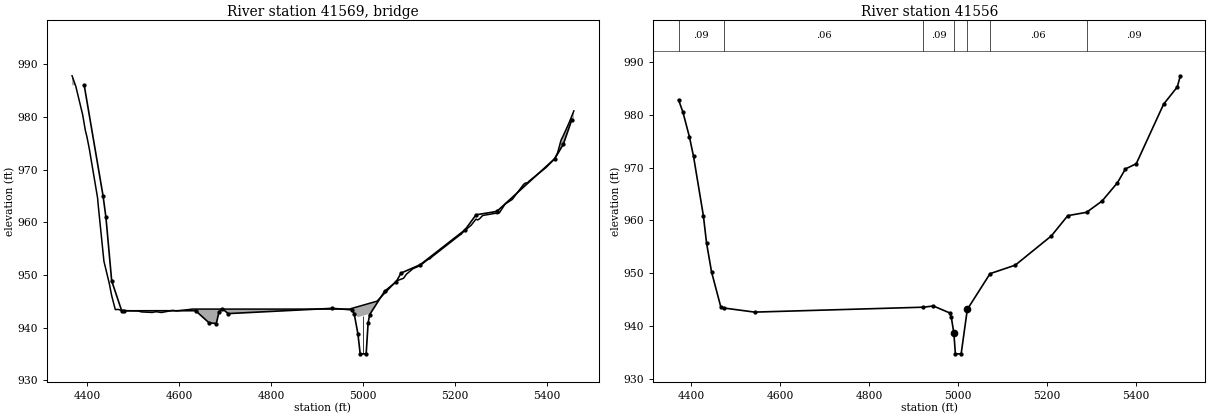
Type RM Length L Ch R = 3 ,41569   ,,,
BEGIN DESCRIPTION:
Cane_Creek_XS-79
Structure ID: Private Rd off of US 64 #2
Approximate Survey Structure
END DESCRIPTION:
Bridge Culvert--1,0,-1,-1, 0
Deck Dist Width WeirC Skew NumUp NumDn MinLoCord MaxHiCord MaxSubmerge Is_Ogee
4.5,15,3,0, 60, 60, 943.5, , , 0, 1,1,,
  4366.7  4374.9  4389.7  4395.6    4399  4404.3  4422.2  4423.4    4436  4447.7
  4452.8  4460.7  4467.6  4473.9  4509.9    4518  4541.2  4549.3  4561.2  4585.6
  4593.7  4628.8    4970    4970    5030    5030  5067.5  5073.9  5087.8  5093.8
  5108.1  5123.3  5140.3  5145.3  5149.9  5210.3  5212.6  5216.6    5235  5245.3
  5249.3  5253.3  5259.9  5288.3  5291.8    5296    5307  5309.8    5324  5348.9
    5352  5358.4  5359.4  5397.7    5416  5422.8  5430.3  5435.4  5448.4  5458.3
   987.8  985.77  980.42  977.41  976.23  973.88  964.61  963.38  952.58  948.35
  946.07  943.41  943.43  943.22  943.15  942.96  942.86     943  942.85  943.25
  943.14   943.5   943.5   943.5     945     945   948.4   948.9  949.35   950.1
  951.16  951.73  952.89  953.05  953.44  957.57  957.66  958.06  959.44  960.58
  960.42  960.66  961.27   961.7  961.59  961.75  963.22  963.51   964.3  967.16
   967.4  967.52  967.69  970.37     972  973.14  975.55  976.45  978.98  981.13
     912     912     912     912     912     912     912     912     912     912
     912     912     912     912     912     912     912     912     912     912
     912     912     912   941.5     943     912     912     912     912     912
     912     912     912     912     912     912     912     912     912     912
     912     912     912     912     912     912     912     912     912     912
     912     912     912     912     912     912     912     912     912     912
  4366.7  4374.9  4389.7  4395.6    4399  4404.3  4422.2  4423.4    4436  4447.7
  4452.8  4460.7  4467.6  4473.9  4509.9    4518  4541.2  4549.3  4561.2  4585.6
  4593.7  4628.8    4970    4970    5030    5030  5067.5  5073.9  5087.8  5093.8
  5108.1  5123.3  5140.3  5145.3  5149.9  5210.3  5212.6  5216.6    5235  5245.3
  5249.3  5253.3  5259.9  5288.3  5291.8    5296    5307  5309.8    5324  5348.9
    5352  5358.4  5359.4  5397.7    5416  5422.8  5430.3  5435.4  5448.4  5458.3
   987.8  985.77  980.42  977.41  976.23  973.88  964.61  963.38  952.58  948.35
  946.07  943.41  943.43  943.22  943.15  942.96  942.86     943  942.85  943.25
  943.14   943.5   943.5   943.5     945     945   948.4   948.9  949.35   950.1
  951.16  951.73  952.89  953.05  953.44  957.57  957.66  958.06  959.44  960.58
  960.42  960.66  961.27   961.7  961.59  961.75  963.22  963.51   964.3  967.16
   967.4  967.52  967.69  970.37     972  973.14  975.55  976.45  978.98  981.13
     912     912     912     912     912     912     912     912     912     912
     912     912     912     912     912     912     912     912     912     912
     912     912     912   941.5     943     912     912     912     912     912
     912     912     912     912     912     912     912     912     912     912
     912     912     912     912     912     912     912     912     912     912
     912     912     912     912     912     912     912     912     912     912
Pier Skew, UpSta & Num, DnSta & Num=  ,5000, 2 ,5000, 2 , 0 , 0 , 0 ,,
       1       1
     930   942.7
       1       1
     930   942.7
BR Coef= 1 , 1 , 0 ,1.25, 0 ,,,0.8,0,2,0,
WSPro=,,,, 1 ,,,, 0 ,,,, 0 ,,,,-1 ,-1 ,-1 , 0 , 0 , 0 , 0 , 0
BC Design=,, 0 ,, 0 ,,,,,,
BC HTab HWMax=986.01

Type RM Length L Ch R = 1 ,41556   ,329,329,329
BEGIN DESCRIPTION:
Cane_Creek_XS-78
END DESCRIPTION:
XS GIS Cut Line= 6
       1151448.8       655893.03      1151343.33       655860.48
      1151282.13       655904.75      1151189.68       655903.45
       1150950.1       655738.09      1150396.71       655762.83
#Sta/Elev= 30
  4370.9  982.84  4380.8   980.5  4395.5  975.78  4404.6  972.14  4426.8  960.88
  4433.9  955.73  4445.2  950.24  4465.7  943.71  4472.5  943.43  4541.8  942.65
 4921.57  943.58 4943.99  943.81 4980.85  942.49 4984.38  941.64  4990.1  938.68
  4993.5  934.75  5006.5  934.75  5020.4  943.18  5071.5  949.93  5128.2  951.54
  5209.4  957.08  5246.3  960.91  5288.5  961.54  5323.4  963.68  5357.8  967.12
    5376  969.76  5400.3  970.74  5461.8  982.01  5492.6  985.28  5499.4  987.39
#Mann= 7 ,-1 , 0
  4370.9     .09       0  4472.5     .06       0 4921.57     .09       0
  4990.1     .05       0  5020.4     .09       0  5071.5     .06       0
  5288.5     .09       0
#XS Ineff= 2 , 0
       0    4960     943    5040       0     943
Permanent Ineff=
       F       F
Bank Sta=4990.1,5020.4
Exp/Cntr=0.5,0.3