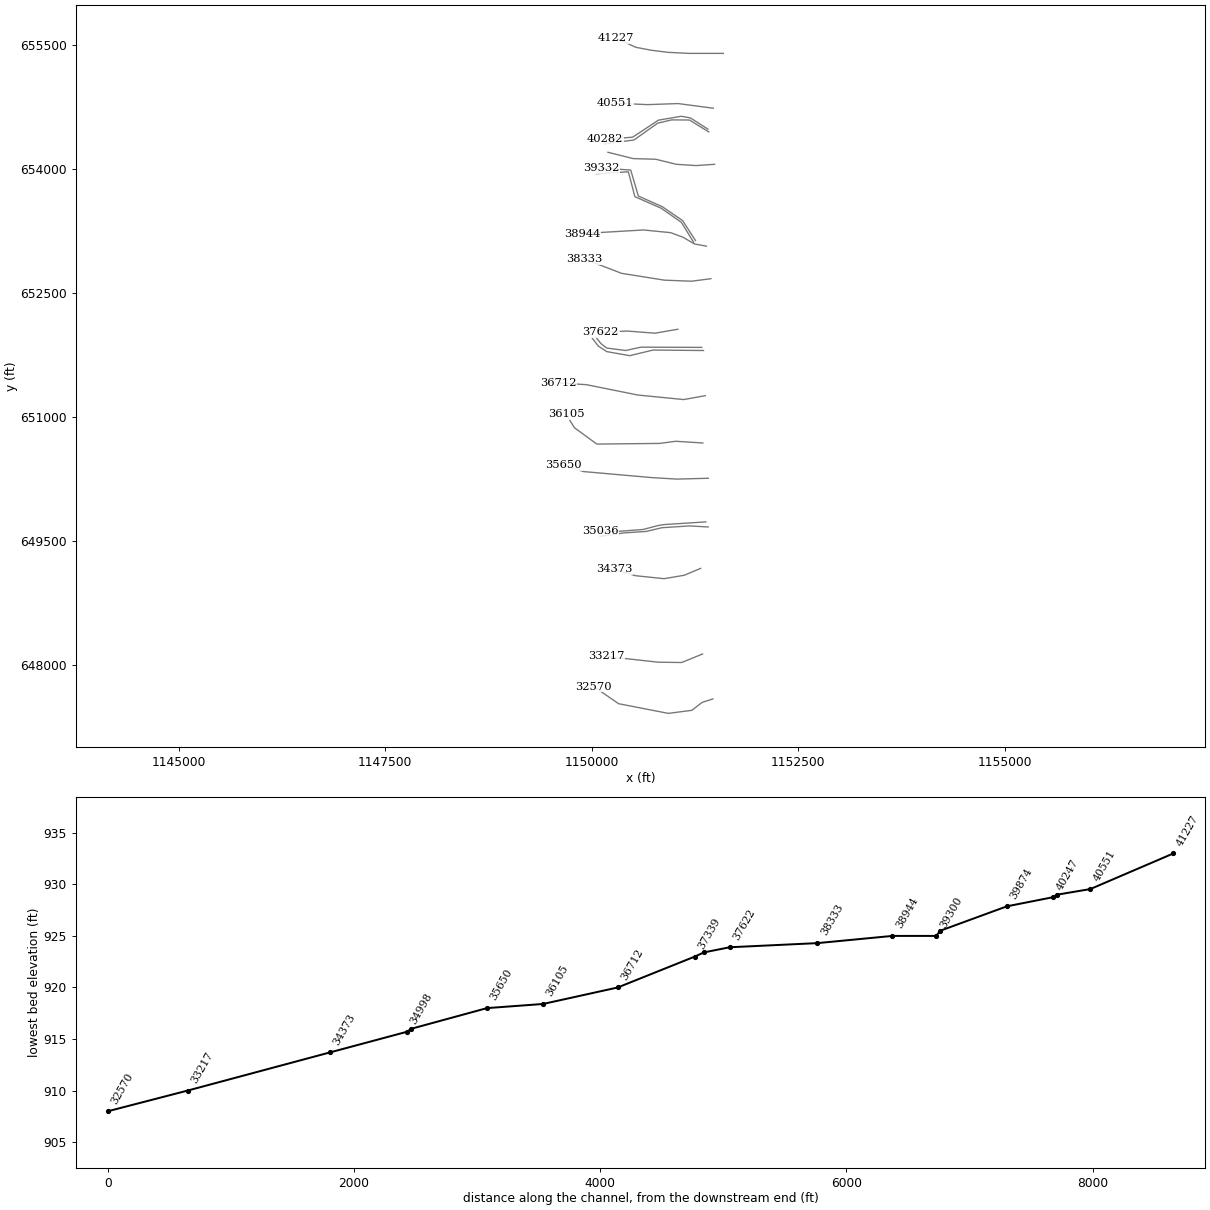
HEC-RAS study lds_cane_crk.prj: Cane Creek Limited Detail Study

--- lds_cane_crk.g01 (geometry) --- (continued)

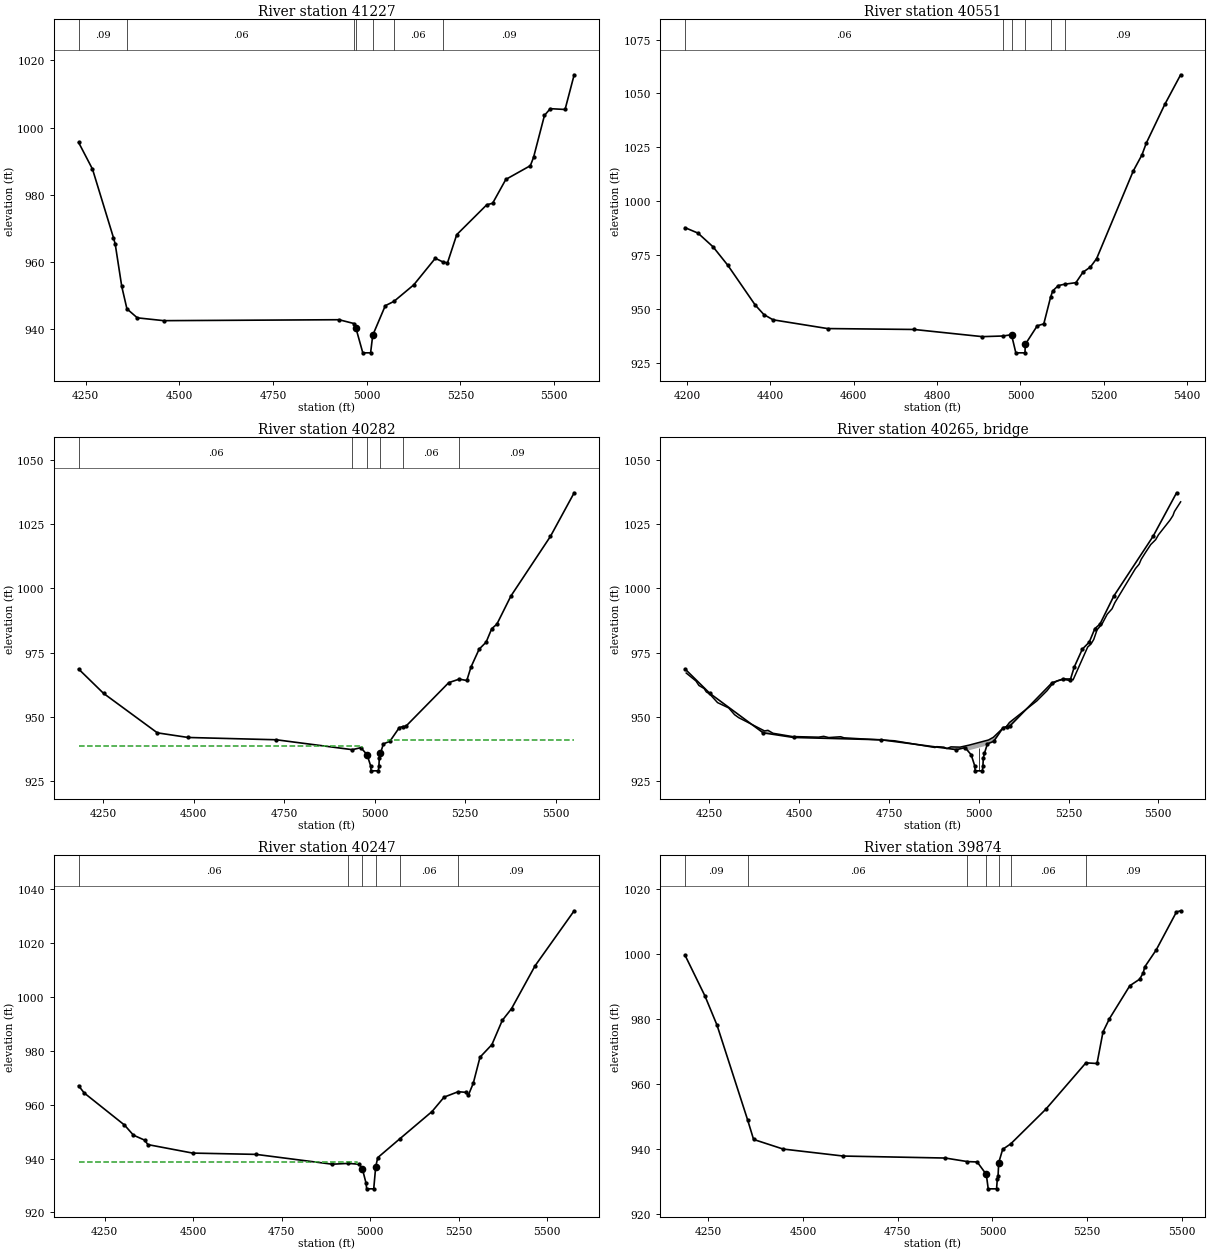
Type RM Length L Ch R = 1 ,41227   ,676,676,676
BEGIN DESCRIPTION:
Cane_Creek_XS-77
END DESCRIPTION:
XS GIS Cut Line= 6
      1151590.94       655402.28      1151178.61       655402.28
      1150918.19        655415.3       1150714.2       655441.34
      1150531.91       655476.06      1150297.53       655584.57
#Sta/Elev= 30
  4231.2  995.56  4268.2  987.64  4324.2  967.23  4328.8  965.37  4346.3  952.74
  4360.1  946.08  4387.8  943.41  4458.4  942.57  4926.2  942.85  4967.2  941.68
    4971  940.45  4989.6     933  5010.4     933  5016.1  938.23  5049.6  947.02
  5072.7   948.3  5125.7  953.23  5183.1  961.12  5202.6  960.08  5215.5  959.73
  5240.3  968.15  5320.6  977.05    5336  977.48  5371.3  984.58  5436.7  988.66
  5445.2   991.1  5474.4 1003.61  5489.9 1005.62  5529.4 1005.38  5553.7  1015.7
#Mann= 7 ,-1 , 0
  4231.2     .09       0  4360.1     .06       0  4967.2     .09       0
    4971     .05       0  5016.1     .09       0  5072.7     .06       0
  5202.6     .09       0
Bank Sta=4971,5016.1
Exp/Cntr=0.3,0.1

Type RM Length L Ch R = 1 ,40551   ,269,269,269
BEGIN DESCRIPTION:
Cane_Creek_XS-76
END DESCRIPTION:
XS GIS Cut Line= 4
      1151469.41       654738.21      1151044.06       654794.64
      1150675.14       654781.62      1150284.51       654798.98
#Sta/Elev= 30
  4195.3  987.64  4226.2  985.13  4262.5  978.74    4298  970.14  4363.3   951.8
  4384.3  947.32  4406.4  944.87  4537.2  940.81  4744.7  940.39  4908.7  937.06
  4958.5  937.36  4978.6  937.97    4989  929.54    5011  929.54  5011.6  933.46
  5040.4  942.09  5056.1     943  5072.4  955.37  5077.5  958.29    5091  960.78
  5106.5  961.41  5133.2  962.12    5150  966.94    5168  969.39  5182.9  973.29
  5270.9 1014.01  5291.7 1021.45  5302.1 1026.93  5346.4 1044.85  5384.5 1058.63
#Mann= 6 ,-1 , 0
  4195.3     .06       0  4958.5     .09       0  4978.6     .05       0
  5011.6     .09       0  5072.4     .06       0  5106.5     .09       0
Bank Sta=4978.6,5011.6
Exp/Cntr=0.5,0.3

Type RM Length L Ch R = 1 ,40282   ,35,35,35
BEGIN DESCRIPTION:
Cane_Creek_XS-75
END DESCRIPTION:
XS GIS Cut Line= 6
      1151405.31       654484.67      1151193.85       654620.61
      1151083.08       654640.75      1150806.16       654593.76
        1150494.       654387.33      1150163.37       654360.48
#Sta/Elev= 30
  4182.2  968.57  4250.9  959.13  4399.6  943.77  4484.6  941.97  4727.9  941.08
  4937.8  937.23  4961.7     938  4978.7  935.28  4988.5     931    4990     929
    5010     929  5011.5     931  5012.6  934.06  5015.8  935.87  5023.9  939.48
  5041.7  940.48  5067.9  945.83  5078.3  946.23  5085.8  946.31  5204.3  963.28
  5233.2  964.65  5254.2  964.12  5265.8  969.37  5288.3  976.31  5307.5  979.02
  5323.1  984.27  5337.2  986.01    5376  996.96  5485.1 1020.13  5550.7 1037.09
#Mann= 6 ,-1 , 0
  4182.2     .06       0  4937.8     .09       0  4978.7     .05       0
  5015.8     .09       0  5078.3     .06       0  5233.2     .09       0
#XS Ineff= 2 , 0
       0  4963.5  938.82  5036.5       0     941
Permanent Ineff=
       F       F
Bank Sta=4978.7,5015.8
Exp/Cntr=0.5,0.3

Type RM Length L Ch R = 3 ,40265   ,,,
BEGIN DESCRIPTION:
Cane_Creek_XS-74
Structure ID: Private Rd off of US 64
Approximate Survey Structure
END DESCRIPTION:
Bridge Culvert--1,0,-1,-1, 0
Deck Dist Width WeirC Skew NumUp NumDn MinLoCord MaxHiCord MaxSubmerge Is_Ogee
9.5,15,3,0, 60, 60, , , , 0, 1,1,,
  4185.3  4212.4  4220.7    4235  4241.4  4250.3  4272.6  4303.6  4319.9  4331.6
  4403.4  4412.9  4426.9    4481    4554  4568.1  4582.2  4615.4  4624.7  4764.5
  4878.2  4882.5  4902.7  4911.1  4922.5  4947.7    4973    4973    5027    5027
  5040.5  5063.1  5076.1  5085.3  5161.5  5189.8  5204.6  5218.2  5239.7  5258.2
  5262.4  5303.2  5312.2    5320  5329.3  5343.4  5357.6  5371.1  5378.7  5436.1
  5446.4  5452.2  5463.1  5478.8  5492.5  5500.4  5532.4  5540.6  5544.7    5562
  967.02  963.93  962.18  961.01  959.66  958.92  955.52  953.45  950.83  949.66
  944.52  944.76  943.61  942.34   942.1  942.42  941.94  942.26  941.84   940.7
  938.06   938.4  938.22  937.66  938.32  938.22     939     939     941     941
  942.04  945.06  946.05   947.8  956.18  960.13  962.75  963.96  964.75  964.71
  964.33  977.14  978.25  980.06  983.82  986.15  989.89  992.01  994.35 1007.62
 1009.33 1011.23 1013.65 1016.97 1018.87  1020.8 1026.46 1028.24 1029.79 1033.57
     909     909     909     909     909     909     909     909     909     909
     909     909     909     909     909     909     909     909     909     909
     909     909     909     909     909     909     909     937     939     909
     909     909     909     909     909     909     909     909     909     909
     909     909     909     909     909     909     909     909     909     909
     909     909     909     909     909     909     909     909     909     909
  4185.3  4212.4  4220.7    4235  4241.4  4250.3  4272.6  4303.6  4319.9  4331.6
  4403.4  4412.9  4426.9    4481    4554  4568.1  4582.2  4615.4  4624.7  4764.5
  4878.2  4882.5  4902.7  4911.1  4922.5  4947.7    4973    4973    5027    5027
  5040.5  5063.1  5076.1  5085.3  5161.5  5189.8  5204.6  5218.2  5239.7  5258.2
  5262.4  5303.2  5312.2    5320  5329.3  5343.4  5357.6  5371.1  5378.7  5436.1
  5446.4  5452.2  5463.1  5478.8  5492.5  5500.4  5532.4  5540.6  5544.7    5562
  967.02  963.93  962.18  961.01  959.66  958.92  955.52  953.45  950.83  949.66
  944.52  944.76  943.61  942.34   942.1  942.42  941.94  942.26  941.84   940.7
  938.06   938.4  938.22  937.66  938.32  938.22     939     939     941     941
  942.04  945.06  946.05   947.8  956.18  960.13  962.75  963.96  964.75  964.71
  964.33  977.14  978.25  980.06  983.82  986.15  989.89  992.01  994.35 1007.62
 1009.33 1011.23 1013.65 1016.97 1018.87  1020.8 1026.46 1028.24 1029.79 1033.57
     909     909     909     909     909     909     909     909     909     909
     909     909     909     909     909     909     909     909     909     909
     909     909     909     909     909     909     909     937     939     909
     909     909     909     909     909     909     909     909     909     909
     909     909     909     909     909     909     909     909     909     909
     909     909     909     909     909     909     909     909     909     909
Pier Skew, UpSta & Num, DnSta & Num=  ,5000, 2 ,5000, 2 , 0 , 0 , 0 ,,
       1       1
     920     939
       1       1
     920     939
BR Coef= 1 , 1 , 0 ,1.25, 0 ,,,0.8,0,2,0,
WSPro=,,,, 1 ,,,, 0 ,,,, 0 ,,,,-1 ,-1 ,-1 , 0 , 0 , 0 , 0 , 0
BC Design=,, 0 ,, 0 ,,,,,,
BC HTab HWMax=1037.09

Type RM Length L Ch R = 1 ,40247   ,373,373,373
BEGIN DESCRIPTION:
Cane_Creek_XS-73
END DESCRIPTION:
XS GIS Cut Line= 6
      1151415.38       654451.11       1151182.1       654595.44
      1150967.28       654597.12      1150796.09       654556.84
      1150510.78       654353.77      1150151.62       654306.77
#Sta/Elev= 30
  4176.4  967.03  4192.1  964.37  4305.9  952.45  4331.3  948.68  4362.7  946.85
  4372.1  945.18  4498.5  942.03  4677.4  941.55  4892.9   937.9  4938.6  938.21
  4969.5  937.87  4977.8  936.23  4988.5  930.75    4990  928.75    5010  928.75
  5015.5  936.89  5021.3  940.34  5082.8  947.24  5174.6  957.46  5208.8  962.82
  5248.6  964.83  5269.6  964.61  5277.4  963.57  5291.2  967.98  5310.2  977.65
  5343.8  982.32  5373.1  991.32  5399.2  995.67  5465.8 1011.61  5576.2 1032.04
#Mann= 6 ,-1 , 0
  4176.4     .06       0  4938.6     .09       0  4977.8     .05       0
  5015.5     .09       0  5082.8     .06       0  5248.6     .09       0
#XS Ineff= 2 , 0
       0  4962.5  938.77  5037.5       0  941.82
Permanent Ineff=
       F       F
Bank Sta=4977.8,5015.5
Exp/Cntr=0.5,0.3

Type RM Length L Ch R = 1 ,39874   ,542,542,542
BEGIN DESCRIPTION:
Cane_Creek_XS-72
END DESCRIPTION:
XS GIS Cut Line= 6
      1151485.64         654059.      1151263.59       654043.69
      1151022.39         654059.      1150773.54       654120.26
      1150501.71       654127.91      1150195.43       654204.48
#Sta/Elev= 30
  4188.7  999.51    4241  987.08    4273  978.09  4353.7  949.05  4369.5  943.03
  4447.4  940.08  4606.5  937.93  4875.8  937.32  4933.6  936.24  4959.9  936.11
  4983.9   932.3    4989  927.87    5011  927.87  5013.1  931.03    5015   931.8
  5016.6  935.86  5027.1  939.98  5048.6  941.69  5140.9  952.28  5246.9  966.53
  5276.2  966.33    5292  976.01    5309  980.07  5362.8  990.19  5388.7  992.19
  5398.6   994.2  5401.7  995.87  5432.4 1001.16    5486 1012.84    5497 1013.19
#Mann= 7 ,-1 , 0
  4188.7     .09       0  4353.7     .06       0  4933.6     .09       0
  4983.9     .05       0  5016.6     .09       0  5048.6     .06       0
  5246.9     .09       0
Bank Sta=4983.9,5016.6
Exp/Cntr=0.5,0.3

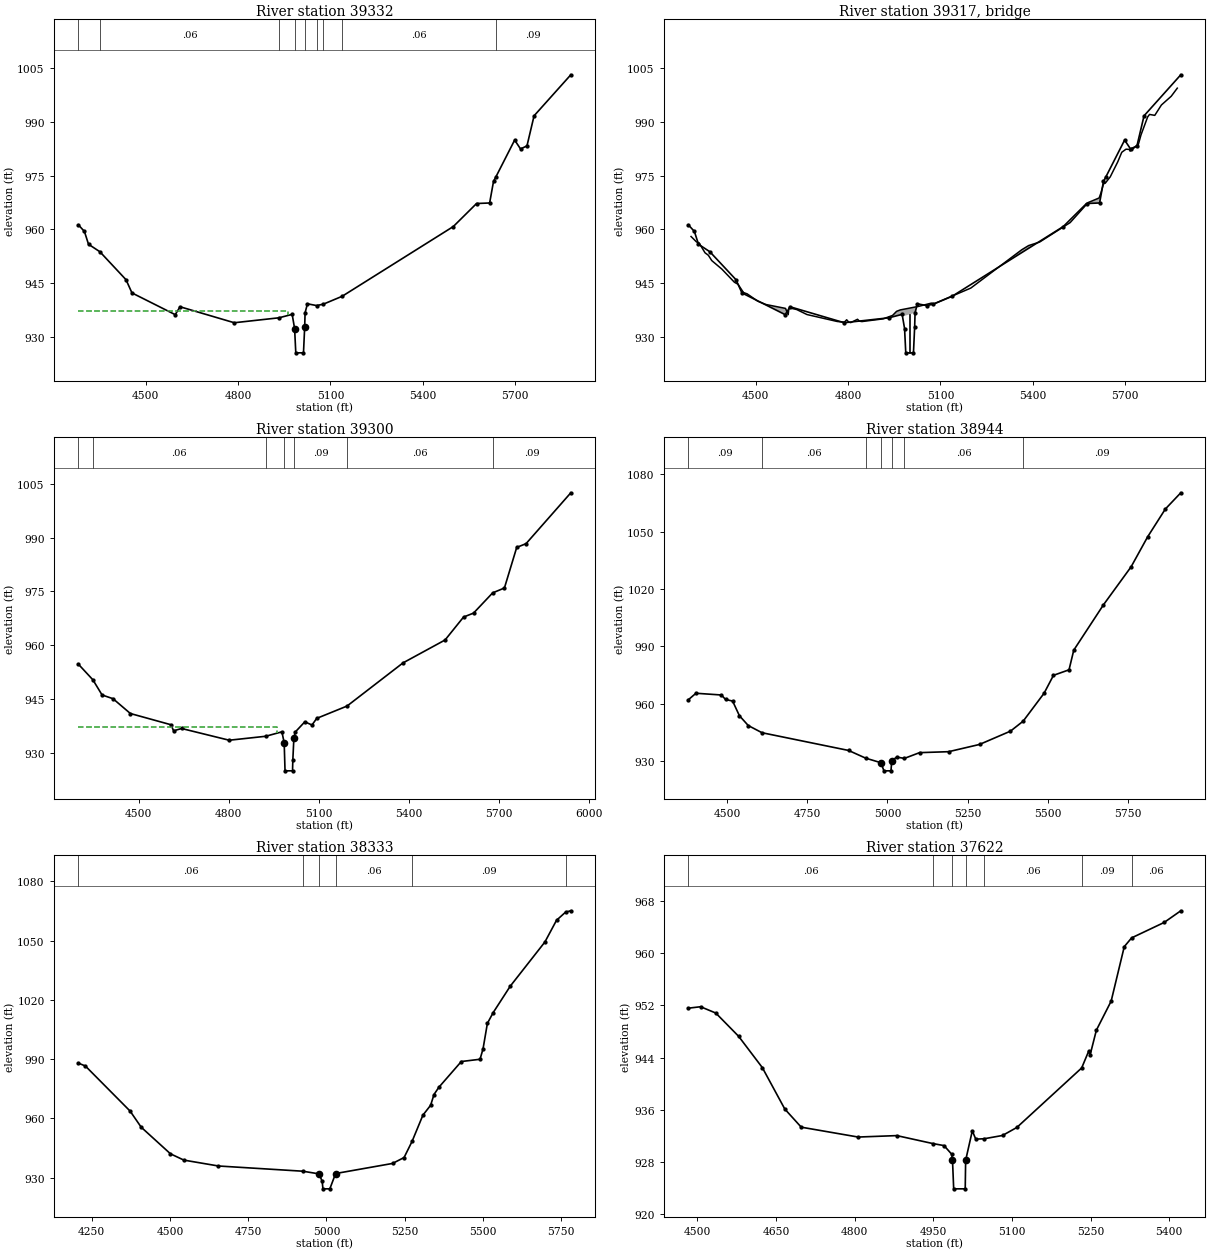
Type RM Length L Ch R = 1 ,39332   ,32,32,32
BEGIN DESCRIPTION:
Cane_Creek_XS-70
END DESCRIPTION:
XS GIS Cut Line= 6
      1151254.24       653135.93      1151099.28       653377.27
      1150851.59        653546.2      1150563.25       653674.49
      1150470.53        653989.5      1150118.68       654013.64
#Sta/Elev= 30
  4281.4  961.23  4300.7  959.42    4314  955.84  4350.9  953.75  4435.9  945.93
  4455.2  942.24  4595.7  936.17  4611.5  938.37  4787.6  933.91  4932.8  935.29
  4975.7  936.25  4983.6   932.3  4987.5   925.5  5012.5   925.5  5016.4  932.79
  5017.7  936.69  5025.3   939.2  5055.1  938.71  5077.1   939.1  5137.9  941.29
  5499.3  960.79  5574.8  967.22  5617.3  967.37  5629.9  973.39  5637.7  974.67
  5698.6  984.95  5717.7  982.47  5738.6  983.32  5761.7  991.73  5881.1 1003.19
#Mann= 9 ,-1 , 0
  4281.4     .09       0  4350.9     .06       0  4932.8     .09       0
  4983.6     .05       0  5016.4     .09       0  5055.1     .06       0
  5077.1     .09       0  5137.9     .06       0  5637.7     .09       0
#XS Ineff= 2 , 0
       0    4962  937.11    5038       0   937.5
Permanent Ineff=
       F       F
Bank Sta=4983.6,5016.4
Exp/Cntr=0.5,0.3

Type RM Length L Ch R = 3 ,39317   ,,,
BEGIN DESCRIPTION:
Cane_Creek_XS-69
Structure ID: US 64
Approximate Survey Structure
END DESCRIPTION:
Bridge Culvert--1,0,-1,-1, 0
Deck Dist Width WeirC Skew NumUp NumDn MinLoCord MaxHiCord MaxSubmerge Is_Ogee
8,14,3,0, 60, 60, , , , 0, 1,1,,
  4289.9  4307.8  4315.4  4335.4  4346.1  4357.1    4390  4430.8  4442.3  4460.2
  4472.2  4506.5  4533.3  4596.8  4605.4  4607.5  4610.1  4633.1  4666.5  4764.7
    4788  4795.5  4802.1  4808.7  4830.8  4836.7    4845  4913.9  4944.6  4957.7
    4970    4970    5030    5030  5070.9  5079.3  5198.7  5364.5  5386.6  5422.3
  5521.7  5580.1  5615.7  5621.7  5629.7  5635.6  5651.9  5676.2  5689.3  5703.1
  5713.5  5716.3  5743.2  5751.7  5773.5  5779.6  5796.5  5818.1    5850  5869.7
     958  956.47  956.25  953.44  952.76  951.28  948.89  945.22  944.67  942.35
  941.98  939.94     939  937.92  936.16  937.71  938.05   937.6   936.2  934.26
  934.07  934.74  934.09  933.95  934.88  934.36  934.24  934.99  935.95   937.1
   937.5   937.5   938.5   938.5   939.4  939.21  943.59  954.31  955.47  956.45
   961.9  967.49  968.77  970.19  972.68   972.9  974.68  978.85  981.54   982.4
  982.34  981.86  983.74  986.37  991.43  992.11  991.85  994.75  997.19  999.45
   905.5   905.5   905.5   905.5   905.5   905.5   905.5   905.5   905.5   905.5
   905.5   905.5   905.5   905.5   905.5   905.5   905.5   905.5   905.5   905.5
   905.5   905.5   905.5   905.5   905.5   905.5   905.5   905.5   905.5   905.5
   905.5   935.5     937   905.5   905.5   905.5   905.5   905.5   905.5   905.5
   905.5   905.5   905.5   905.5   905.5   905.5   905.5   905.5   905.5   905.5
   905.5   905.5   905.5   905.5   905.5   905.5   905.5   905.5   905.5   905.5
  4289.9  4307.8  4315.4  4335.4  4346.1  4357.1    4390  4430.8  4442.3  4460.2
  4472.2  4506.5  4533.3  4596.8  4605.4  4607.5  4610.1  4633.1  4666.5  4764.7
    4788  4795.5  4802.1  4808.7  4830.8  4836.7    4845  4913.9  4944.6  4957.7
    4970    4970    5030    5030  5070.9  5079.3  5198.7  5364.5  5386.6  5422.3
  5521.7  5580.1  5615.7  5621.7  5629.7  5635.6  5651.9  5676.2  5689.3  5703.1
  5713.5  5716.3  5743.2  5751.7  5773.5  5779.6  5796.5  5818.1    5850  5869.7
     958  956.47  956.25  953.44  952.76  951.28  948.89  945.22  944.67  942.35
  941.98  939.94     939  937.92  936.16  937.71  938.05   937.6   936.2  934.26
  934.07  934.74  934.09  933.95  934.88  934.36  934.24  934.99  935.95   937.1
   937.5   937.5   938.5   938.5   939.4  939.21  943.59  954.31  955.47  956.45
   961.9  967.49  968.77  970.19  972.68   972.9  974.68  978.85  981.54   982.4
  982.34  981.86  983.74  986.37  991.43  992.11  991.85  994.75  997.19  999.45
   905.5   905.5   905.5   905.5   905.5   905.5   905.5   905.5   905.5   905.5
   905.5   905.5   905.5   905.5   905.5   905.5   905.5   905.5   905.5   905.5
   905.5   905.5   905.5   905.5   905.5   905.5   905.5   905.5   905.5   905.5
   905.5   935.5     937   905.5   905.5   905.5   905.5   905.5   905.5   905.5
   905.5   905.5   905.5   905.5   905.5   905.5   905.5   905.5   905.5   905.5
   905.5   905.5   905.5   905.5   905.5   905.5   905.5   905.5   905.5   905.5
Pier Skew, UpSta & Num, DnSta & Num=  ,5000, 2 ,5000, 2 , 0 , 0 , 0 ,,
       1       1
     920   936.7
       1       1
     920   936.7
BR Coef= 1 , 1 , 0 ,1.25, 0 ,,,0.8,0,2,0,
WSPro=,,,, 1 ,,,, 0 ,,,, 0 ,,,,-1 ,-1 ,-1 , 0 , 0 , 0 , 0 , 0
BC Design=,, 0 ,, 0 ,,,,,,
BC HTab HWMax=1003.19

Type RM Length L Ch R = 1 ,39300   ,356,356,356
BEGIN DESCRIPTION:
Cane_Creek_XS-68
END DESCRIPTION:
XS GIS Cut Line= 6
      1151232.13       653114.65      1151083.48       653356.96
       1150837.1       653528.01      1150521.48       653666.47
      1150442.07       653967.83      1150053.15       653945.44
#Sta/Elev= 30
  4298.8  954.69  4346.9  950.36  4377.5  946.14    4414   945.1  4471.9  940.97
  4607.4  937.84  4615.9  936.15  4642.6   936.8  4801.4  933.53    4923  934.63
  4977.1  935.87  4984.7  932.81  4987.5     925  5012.5     925  5013.5     928
    5017  934.11  5021.6  935.82  5053.5  938.66  5077.4  937.77  5093.2  939.62
  5194.2  943.05  5380.9  955.08  5521.1  961.46  5582.7  967.85    5616  968.95
  5679.8  974.59    5719  975.95    5760  987.26  5791.1   988.3  5940.4 1002.48
#Mann= 7 ,-1 , 0
  4298.8     .09       0  4346.9     .06       0    4923     .09       0
  4984.7     .05       0    5017     .09       0  5194.2     .06       0
  5679.8     .09       0
#XS Ineff= 2 , 0
       0    4960   937.1    5040       0   937.1
Permanent Ineff=
       F       F
Bank Sta=4984.7,5017
Exp/Cntr=0.5,0.3

Type RM Length L Ch R = 1 ,38944   ,611,611,611
BEGIN DESCRIPTION:
Cane_Creek_XS-67
END DESCRIPTION:
XS GIS Cut Line= 6
      1151386.88       653067.82      1151242.31       653094.29
      1151103.84       653175.74      1150953.41       653231.18
      1150624.71       653263.75      1149886.87       653220.35
#Sta/Elev= 30
  4378.5   962.2  4401.9  965.55  4481.5  964.64  4494.3   962.3  4516.4  961.47
  4537.6  953.82  4565.3  948.67  4608.2  944.92  4878.5  935.66  4931.9  931.63
  4979.3  929.26    4989     925    5011     925  5013.2  930.35    5029  932.19
  5052.7   931.5  5100.2  934.51  5190.9  935.01  5287.4  938.79  5384.1  945.75
  5423.7  950.97    5489  965.56  5518.3  974.92  5566.9   977.8  5581.7  988.09
  5674.5  1011.8  5760.7 1031.63  5812.4 1047.32  5867.7 1061.85  5915.9 1070.33
#Mann= 7 ,-1 , 0
  4378.5     .09       0  4608.2     .06       0  4931.9     .09       0
  4979.3     .05       0  5013.2     .09       0  5052.7     .06       0
  5423.7     .09       0
Bank Sta=4979.3,5013.2
Exp/Cntr=0.3,0.1

Type RM Length L Ch R = 1 ,38333   ,711,711,711
BEGIN DESCRIPTION:
Cane_Creek_XS-66
END DESCRIPTION:
XS GIS Cut Line= 5
      1151440.69       652673.47      1151206.31       652643.09
      1150876.45       652656.11      1150359.96       652738.58
      1149908.57       652912.19
#Sta/Elev= 30
  4207.9  987.94  4229.9  986.51    4373  963.65  4408.3  955.51  4501.8  942.04
  4544.6  938.85  4655.1  935.87  4924.5  933.23  4976.6  931.88  4986.6  928.09
    4989   924.3    5011   924.3  5029.5  932.05  5211.3  937.16  5248.2  940.15
  5273.8  948.34  5308.4  961.61  5333.1  966.63  5343.8  972.06  5359.3  975.72
  5431.1  988.77  5490.9  989.92  5500.5  995.16  5514.4 1008.09  5533.1 1013.59
  5587.7 1026.98  5698.2 1049.31  5735.3  1060.3  5764.5 1064.46    5781 1065.11
#Mann= 6 ,-1 , 0
  4207.9     .06       0  4924.5     .09       0  4976.6     .04       0
  5029.5     .06       0  5273.8     .09       0  5764.5     .06       0
Bank Sta=4976.6,5029.5
Exp/Cntr=0.3,0.1

Type RM Length L Ch R = 1 ,37622   ,210,210,210
BEGIN DESCRIPTION:
Cane_Creek_XS-65
END DESCRIPTION:
XS GIS Cut Line= 4
      1151041.38        652061.5       1150763.6       652013.75
      1150425.06       652039.79      1150107.99       652023.39
#Sta/Elev= 30
  4483.2  951.56  4506.4  951.78  4535.4  950.81  4578.8  947.26  4624.1  942.46
    4667  936.11  4698.3  933.34  4806.8  931.83  4880.5  932.05  4949.4  930.83
  4970.6  930.52    4985  929.22  4986.7  928.38    4989   923.9    5011   923.9
  5011.8  928.26  5024.5  932.78  5031.1  931.51  5047.3  931.57  5082.1  932.07
  5109.5   933.3  5233.1  942.41  5246.4  944.97  5249.2  944.41  5261.1  948.19
  5289.3  952.64  5314.3  960.98  5328.3  962.32  5390.3  964.68  5422.1  966.47
#Mann= 7 ,-1 , 0
  4483.2     .06       0  4949.4     .09       0  4986.7     .05       0
  5011.8     .09       0  5047.3     .06       0  5233.1     .09       0
  5328.3     .06       0
Bank Sta=4986.7,5011.8
Exp/Cntr=0.5,0.3

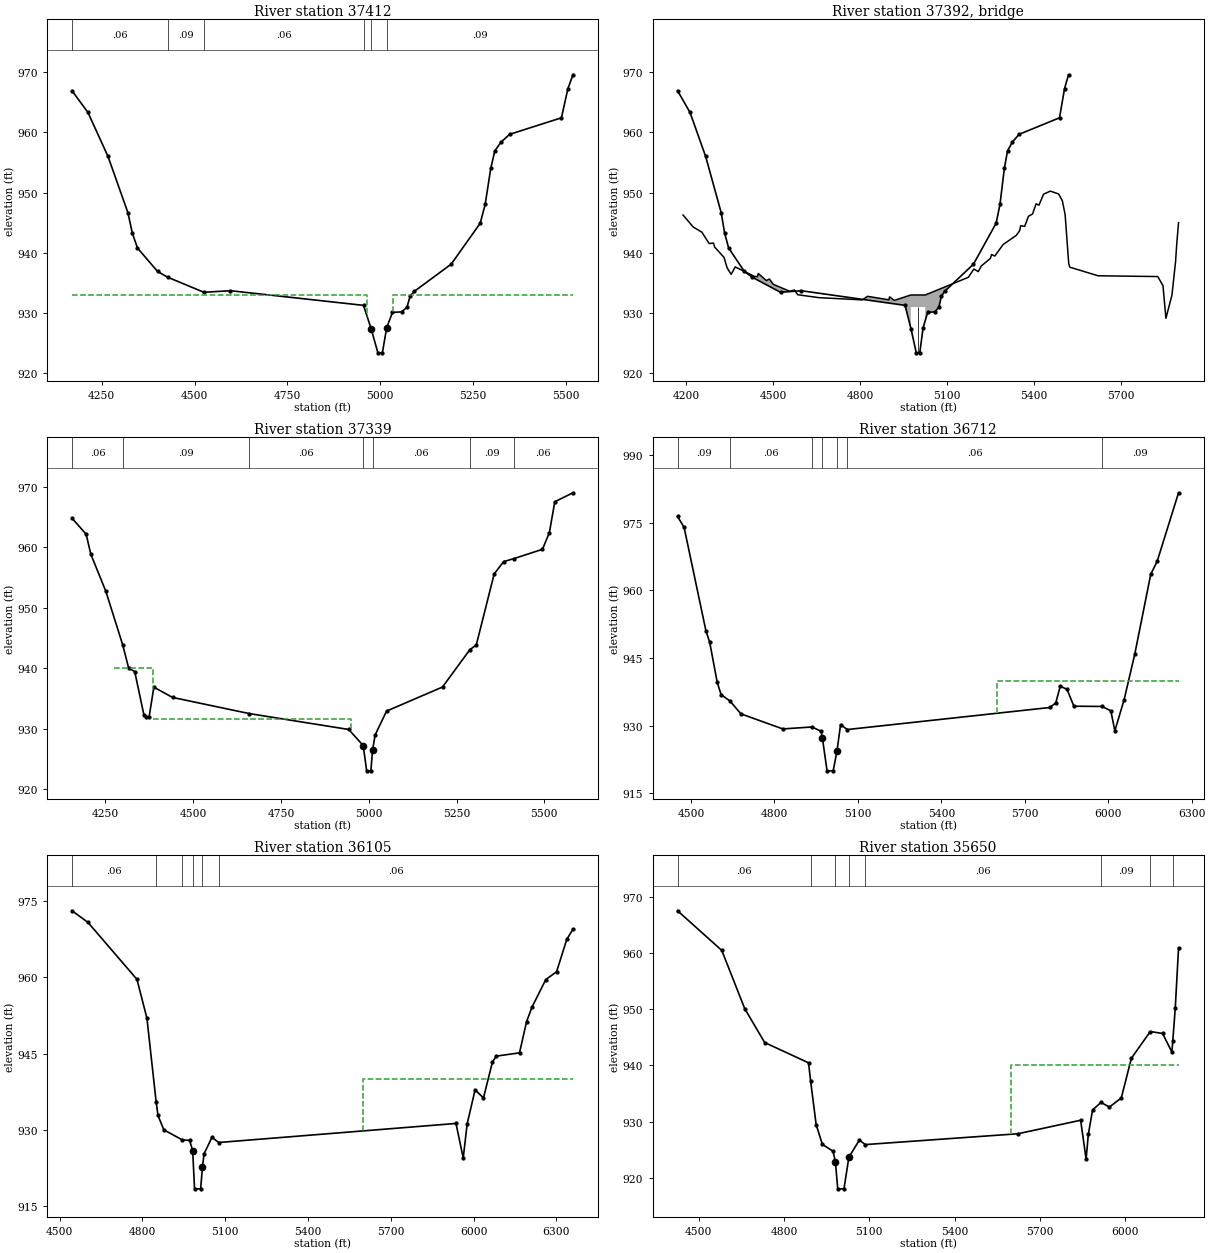
Type RM Length L Ch R = 1 ,37412   ,73,73,73
BEGIN DESCRIPTION:
Cane_Creek_XS-64
END DESCRIPTION:
XS GIS Cut Line= 6
      1151330.53       651841.69      1150595.16       651844.64
      1150409.83       651804.04      1150180.93       651833.59
      1150110.77       651887.57        1150046.       651968.52
#Sta/Elev= 30
    4170   966.9    4213  963.29  4266.9     956  4320.7  946.63  4332.4  943.27
  4346.3   940.8  4400.4  936.91  4427.3  935.96  4525.3  933.45 4596.89  933.71
  4955.2  931.28  4975.7   927.4    4994   923.4    5006   923.4  5017.6  927.56
 5033.16  930.11 5057.72   930.2 5072.04  930.94 5080.74  932.79    5092   933.6
  5191.4  938.12  5269.6  944.91    5283  948.05    5298  954.02    5309  956.93
  5325.6  958.37  5348.7  959.66  5488.4  962.41  5505.8  967.26  5519.5  969.55
#Mann= 6 ,-1 , 0
    4170     .06       0  4427.3     .09       0  4525.3     .06       0
  4955.2     .09       0  4975.7    .045       0  5017.6     .09       0
#XS Ineff= 2 , 0
       0    4965     933    5035       0     933
Permanent Ineff=
       F       F
Bank Sta=4975.7,5017.6
Exp/Cntr=0.5,0.3

Type RM Length L Ch R = 3 ,37392   ,,,
BEGIN DESCRIPTION:
Cane_Creek_XS-63
Structure ID: Cunningham Dr
Approximate Survey Structure
END DESCRIPTION:
Bridge Culvert--1,0,-1,-1, 0
Deck Dist Width WeirC Skew NumUp NumDn MinLoCord MaxHiCord MaxSubmerge Is_Ogee
12.5,15,3,0, 60, 60, , , , 0, 1,1,,
  4188.9  4224.3  4253.8  4278.9  4294.1    4298  4330.1  4341.1    4355    4369
  4435.3  4445.7  4448.7  4476.3  4486.9  4500.7  4556.7  4573.2  4585.1  4657.7
  4807.3  4825.9  4899.2  4901.9  4917.9    4975    4975    5025    5025  5173.8
  5192.8    5208  5218.5  5249.9  5253.9    5265  5293.4  5339.3  5350.7  5354.2
  5368.1  5381.3  5395.4  5407.5  5417.4  5433.5  5456.8  5485.3  5498.1  5507.8
  5520.2  5523.8  5621.4  5827.5  5845.6  5855.7  5876.5  5889.1  5893.1  5899.3
  946.27  944.27  943.43  941.54  941.62  940.95  939.25   937.5  936.42  937.66
  936.08  936.05  936.57   935.4  935.65  934.76  933.63  933.83  933.04  932.56
  932.19  932.78   932.2  932.69   932.1     933     933     933     933  935.94
  937.31  936.88  937.82  939.08  939.72  939.46  941.36   942.9  943.66   944.5
  944.39  946.07  946.45  948.13  947.91  949.74  950.24  949.77  948.66  946.35
  938.22  937.62  936.19  936.06  934.56  929.14  932.96  938.56  941.49     945
  900.35  900.35  900.35  900.35  900.35  900.35  900.35  900.35  900.35  900.35
  900.35  900.35  900.35  900.35  900.35  900.35  900.35  900.35  900.35  900.35
  900.35  900.35  900.35  900.35  900.35  900.35     931     931  900.35  900.35
  900.35  900.35  900.35  900.35  900.35  900.35  900.35  900.35  900.35  900.35
  900.35  900.35  900.35  900.35  900.35  900.35  900.35  900.35  900.35  900.35
  900.35  900.35  900.35  900.35  900.35  900.35  900.35  900.35  900.35  900.35
  4188.9  4224.3  4253.8  4278.9  4294.1    4298  4330.1  4341.1    4355    4369
  4435.3  4445.7  4448.7  4476.3  4486.9  4500.7  4556.7  4573.2  4585.1  4657.7
  4807.3  4825.9  4899.2  4901.9  4917.9    4975    4975    5025    5025  5173.8
  5192.8    5208  5218.5  5249.9  5253.9    5265  5293.4  5339.3  5350.7  5354.2
  5368.1  5381.3  5395.4  5407.5  5417.4  5433.5  5456.8  5485.3  5498.1  5507.8
  5520.2  5523.8  5621.4  5827.5  5845.6  5855.7  5876.5  5889.1  5893.1  5899.3
  946.27  944.27  943.43  941.54  941.62  940.95  939.25   937.5  936.42  937.66
  936.08  936.05  936.57   935.4  935.65  934.76  933.63  933.83  933.04  932.56
  932.19  932.78   932.2  932.69   932.1     933     933     933     933  935.94
  937.31  936.88  937.82  939.08  939.72  939.46  941.36   942.9  943.66   944.5
  944.39  946.07  946.45  948.13  947.91  949.74  950.24  949.77  948.66  946.35
  938.22  937.62  936.19  936.06  934.56  929.14  932.96  938.56  941.49     945
  900.35  900.35  900.35  900.35  900.35  900.35  900.35  900.35  900.35  900.35
  900.35  900.35  900.35  900.35  900.35  900.35  900.35  900.35  900.35  900.35
  900.35  900.35  900.35  900.35  900.35  900.35     931     931  900.35  900.35
  900.35  900.35  900.35  900.35  900.35  900.35  900.35  900.35  900.35  900.35
  900.35  900.35  900.35  900.35  900.35  900.35  900.35  900.35  900.35  900.35
  900.35  900.35  900.35  900.35  900.35  900.35  900.35  900.35  900.35  900.35
Pier Skew, UpSta & Num, DnSta & Num=  ,5000, 2 ,5000, 2 , 0 , 0 , 0 ,,
       1       1
     920     932
       1       1
     920     932
BR Coef= 1 , 1 , 0 ,1.25, 0 ,,,0.8,0,2,0,
WSPro=,,,, 1 ,,,, 0 ,,,, 0 ,,,,-1 ,-1 ,-1 , 0 , 0 , 0 , 0 , 0
BC Design=,, 0 ,, 0 ,,,,,,
BC HTab HWMax=969.55

Type RM Length L Ch R = 1 ,37339   ,627,627,627
BEGIN DESCRIPTION:
Cane_Creek_XS-62
END DESCRIPTION:
XS GIS Cut Line= 6
      1151352.12       651803.91      1150739.89       651809.34
      1150459.79       651741.34      1150180.93       651790.42
      1150078.39       651857.88      1150005.52       651952.33
#Sta/Elev= 30
  4155.1  964.77  4195.3  962.13  4208.5  958.83  4251.5  952.67  4299.5  943.81
  4316.5  939.95  4333.6  939.42  4359.5  932.31  4365.4  931.96  4374.6  931.93
  4388.1  936.84  4441.2  935.14  4660.4  932.46 4943.02  929.84  4984.2  927.18
    4994     923    5006     923  5010.9  926.47  5018.2  928.94  5050.7  932.88
    5210  936.86  5287.9  943.04  5306.1   943.8  5357.1  955.56  5383.8  957.59
  5412.4  958.08  5494.5  959.63  5514.2  962.37  5529.7   967.5  5581.5  968.98
#Mann= 7 ,-1 , 0
  4155.1     .06       0  4299.5     .09       0  4660.4     .06       0
  4984.2     .05       0  5010.9     .06       0  5287.9     .09       0
  5412.4     .06       0
#XS Ineff= 3 ,-1
    4275    4387     940    4387    4950   931.5    5055    5200   931.5
Permanent Ineff=
       F       T       T
Bank Sta=4984.2,5010.9
Exp/Cntr=0.5,0.3

Type RM Length L Ch R = 1 ,36712   ,607,607,607
BEGIN DESCRIPTION:
Cane_Creek_XS-61
END DESCRIPTION:
XS GIS Cut Line= 5
      1151372.54       651256.81      1151112.13       651209.93
      1150557.44       651264.62      1149937.65       651389.62
      1149591.29       651413.06
#Sta/Elev= 30
  4451.5  976.37    4475  973.94  4553.5  951.01    4567  948.49  4594.1  939.59
  4608.2  936.87  4639.6   935.5  4679.3  932.63  4829.8  929.29    4935  929.72
  4967.9  928.74  4972.4  927.23    4989     920    5011     920  5024.8   924.4
  5037.6  930.25  5061.8  929.15  5790.6  934.04  5811.5  935.07  5827.6  938.75
  5851.9  938.06  5876.5  934.32  5978.2  934.27  6009.5  933.29  6023.9  928.86
  6057.3  935.79  6095.6  945.88  6152.9  963.55    6176  966.41  6252.9  981.62
#Mann= 7 ,-1 , 0
  4451.5     .09       0  4639.6     .06       0    4935     .09       0
  4972.4     .05       0  5024.8     .09       0  5061.8     .06       0
  5978.2     .09       0
#XS Ineff= 2 , 0
       0                    5600       0     940
Permanent Ineff=
       F       F
Bank Sta=4972.4,5024.8
Exp/Cntr=0.3,0.1

Type RM Length L Ch R = 1 ,36105   ,455,455,455
BEGIN DESCRIPTION:
Cane_Creek_XS-60
END DESCRIPTION:
XS GIS Cut Line= 6
       1151343.9       650683.89      1151015.77       650704.72
      1150820.46       650678.68      1150060.04       650670.87
      1149789.21       650868.79      1149687.65       651032.85
#Sta/Elev= 30
  4545.2  973.13  4602.7  970.86  4780.4  959.63  4816.6  951.96  4849.8  935.56
  4856.7  932.84  4877.7  930.01  4943.8  928.06  4971.4  927.92  4982.3  925.88
    4989   918.4    5011   918.4  5017.8  922.71  5023.4  925.29  5052.2  928.54
  5076.6  927.52  5936.1  931.27  5962.3  924.46  5976.5  931.17  6005.3  937.89
  6035.6  936.29  6068.1  943.36  6082.1  944.52  6166.2  945.17  6191.7  951.29
  6211.2  954.15  6261.5   959.6  6300.5  961.13  6337.3  967.49  6359.9  969.52
#Mann= 6 ,-1 , 0
  4545.2     .06       0  4849.8     .06       0  4943.8     .09       0
  4982.3     .05       0  5017.8     .09       0  5076.6     .06       0
#XS Ineff= 2 , 0
       0                    5600       0     940
Permanent Ineff=
       F       F
Bank Sta=4982.3,5017.8
Exp/Cntr=0.3,0.1

Type RM Length L Ch R = 1 ,35650   ,614,614,614
BEGIN DESCRIPTION:
Cane_Creek_XS-59
END DESCRIPTION:
XS GIS Cut Line= 5
        1151409.       650256.81      1151028.79       650246.39
      1150723.76       650264.92      1149901.19       650337.54
      1149661.61       650413.06
#Sta/Elev= 30
  4425.4  967.58    4581  960.51  4661.5  950.15  4731.8  944.09  4886.2  940.47
  4893.5  937.26    4913  929.46  4934.8  925.94 4972.41  924.71  4980.8  922.82
    4989     918    5011     918  5028.2  923.63  5065.2  926.71  5085.6  925.89
  5622.8  927.82  5843.8  930.23    5863   923.3  5870.9  927.73  5885.8  932.06
  5915.4  933.41    5945  932.58  5986.9  934.21  6022.4  941.29  6088.9  946.05
  6132.3   945.7  6164.9  942.38    6168  944.35  6176.9  950.32  6188.3  960.93
#Mann= 8 ,-1 , 0
  4425.4     .06       0  4893.5     .09       0  4980.8     .05       0
  5028.2     .09       0  5085.6     .06       0  5915.4     .09       0
  6088.9     .06       0    6168     .09       0
#XS Ineff= 2 , 0
       0                    5600       0     940
Permanent Ineff=
       F       F
Bank Sta=4980.8,5028.2
Exp/Cntr=0.5,0.3

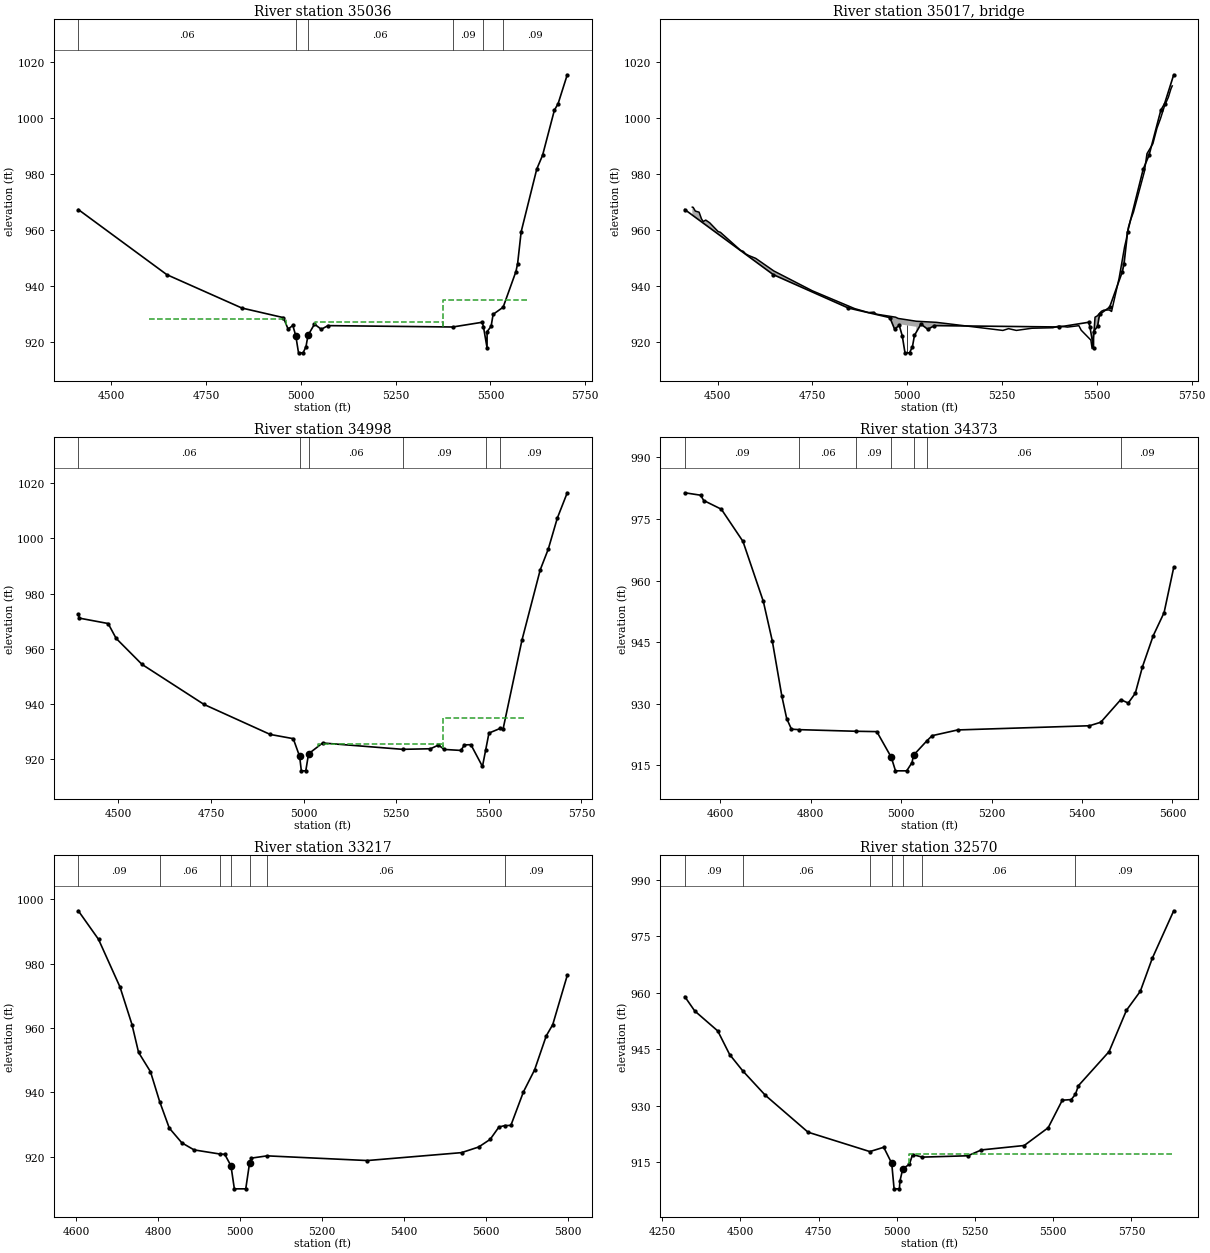
Type RM Length L Ch R = 1 ,35036   ,38,38,38
BEGIN DESCRIPTION:
Cane_Creek_XS-58
END DESCRIPTION:
XS GIS Cut Line= 6
       1151379.7       649728.22      1150872.98       649695.76
      1150797.24       649683.14      1150620.52       649636.26
      1150306.75       649612.81      1150099.37       649614.62
#Sta/Elev= 30
  4413.2  967.23  4646.8  943.94  4844.6  932.02  4954.1  928.59 4966.48  924.49
 4978.94  925.79  4986.8  922.07    4994     916    5006     916  5013.6  918.17
    5019  922.26  5036.1  926.26  5054.1  924.41  5071.5  925.73  5400.6  925.24
  5478.4  926.93  5481.7  925.34  5491.2   917.8  5491.3  923.57  5501.9  925.49
  5507.2  929.76  5533.6  932.31  5567.3  945.04  5571.8  947.88  5581.1  959.25
  5622.3   981.7  5637.6  986.62  5668.8 1002.76  5678.5 1005.05  5702.7 1015.41
#Mann= 6 ,-1 , 0
  4413.2     .06       0  4986.8    .054       0    5019     .06       0
  5400.6     .09       0  5481.7     .06       0  5533.6     .09       0
#XS Ineff= 3 ,-1
  4599.7  4962.2     928    5038    5375   926.9    5375    5600     935
Permanent Ineff=
       T       T       F
Bank Sta=4986.8,5019
Exp/Cntr=0.5,0.3

Type RM Length L Ch R = 3 ,35017   ,,,
BEGIN DESCRIPTION:
Cane_Creek_XS-57
Structure ID: Private Dr off of Cane Creek Rd #2
Approximate Survey Structure
END DESCRIPTION:
Bridge Culvert--1,0,-1,-1, 0
Deck Dist Width WeirC Skew NumUp NumDn MinLoCord MaxHiCord MaxSubmerge Is_Ogee
11.5,15,3,0, 60, 60, , , , 0, 1,1,,
  4433.1  4435.4    4441    4451  4457.2  4461.6  4468.6  4479.2  4501.1  4507.2
  4560.3  4567.9  4573.4  4582.3  4600.3    4648  4749.7  4861.2  4897.9  4912.6
  4918.1  4969.2    4976    4976    5024    5024  5076.6  5252.1  5267.1  5287.7
  5328.7  5384.1  5399.5  5422.5  5452.6  5458.7  5484.2  5487.5  5492.4  5495.2
  5501.2    5512  5518.3  5532.4  5538.8  5558.6  5573.2  5577.3  5583.4  5588.7
  5596.5  5625.3  5632.2  5647.8  5658.6  5667.6  5678.6  5688.6  5695.4  5698.8
  968.09  968.01  966.69  966.29  963.93  962.96  963.46  962.46  959.37  959.09
  952.66  952.26  951.42  950.77  949.78  945.28  938.18  931.82  930.39  930.57
  929.84  928.75   928.3   928.3   927.3   927.3  926.91  924.01  924.65  924.02
  924.79  924.97  925.59  925.21  925.71  924.09  920.56  917.52  923.62  928.75
  929.22  930.85  931.26  931.34   930.8  942.64  953.99  956.33  960.98  963.42
  966.29  980.77  987.22  990.77  996.36  999.65 1004.35 1007.38 1010.41 1011.43
  893.36  893.36  893.36  893.36  893.36  893.36  893.36  893.36  893.36  893.36
  893.36  893.36  893.36  893.36  893.36  893.36  893.36  893.36  893.36  893.36
  893.36  893.36  893.36   926.3   925.3  893.36  893.36  893.36  893.36  893.36
  893.36  893.36  893.36  893.36  893.36  893.36  893.36  893.36  893.36  893.36
  893.36  893.36  893.36  893.36  893.36  893.36  893.36  893.36  893.36  893.36
  893.36  893.36  893.36  893.36  893.36  893.36  893.36  893.36  893.36  893.36
  4433.1  4435.4    4441    4451  4457.2  4461.6  4468.6  4479.2  4501.1  4507.2
  4560.3  4567.9  4573.4  4582.3  4600.3    4648  4749.7  4861.2  4897.9  4912.6
  4918.1  4969.2    4976    4976    5024    5024  5076.6  5252.1  5267.1  5287.7
  5328.7  5384.1  5399.5  5422.5  5452.6  5458.7  5484.2  5487.5  5492.4  5495.2
  5501.2    5512  5518.3  5532.4  5538.8  5558.6  5573.2  5577.3  5583.4  5588.7
  5596.5  5625.3  5632.2  5647.8  5658.6  5667.6  5678.6  5688.6  5695.4  5698.8
  968.09  968.01  966.69  966.29  963.93  962.96  963.46  962.46  959.37  959.09
  952.66  952.26  951.42  950.77  949.78  945.28  938.18  931.82  930.39  930.57
  929.84  928.75   928.3   928.3   927.3   927.3  926.91  924.01  924.65  924.02
  924.79  924.97  925.59  925.21  925.71  924.09  920.56  917.52  923.62  928.75
  929.22  930.85  931.26  931.34   930.8  942.64  953.99  956.33  960.98  963.42
  966.29  980.77  987.22  990.77  996.36  999.65 1004.35 1007.38 1010.41 1011.43
  893.36  893.36  893.36  893.36  893.36  893.36  893.36  893.36  893.36  893.36
  893.36  893.36  893.36  893.36  893.36  893.36  893.36  893.36  893.36  893.36
  893.36  893.36  893.36   926.3   925.3  893.36  893.36  893.36  893.36  893.36
  893.36  893.36  893.36  893.36  893.36  893.36  893.36  893.36  893.36  893.36
  893.36  893.36  893.36  893.36  893.36  893.36  893.36  893.36  893.36  893.36
  893.36  893.36  893.36  893.36  893.36  893.36  893.36  893.36  893.36  893.36
Pier Skew, UpSta & Num, DnSta & Num=  ,5000, 2 ,5000, 2 , 0 , 0 , 0 ,,
       1       1
     915   926.7
       1       1
     915   926.7
BR Coef= 1 , 1 , 0 ,1.25, 0 ,,,0.8,0,2,0,
WSPro=,,,, 1 ,,,, 0 ,,,, 0 ,,,,-1 ,-1 ,-1 , 0 , 0 , 0 , 0 , 0
BC Design=,, 0 ,, 0 ,,,,,,
BC HTab HWMax=1015.41

Type RM Length L Ch R = 1 ,34998   ,625,625,625
BEGIN DESCRIPTION:
Cane_Creek_XS-56
END DESCRIPTION:
XS GIS Cut Line= 6
      1151408.55       649666.91      1151181.34       649679.54
      1150849.54        649657.9      1150658.39       649612.81
      1150384.29       649594.78      1150099.37       649553.31
#Sta/Elev= 30
  4392.1  972.41  4395.1  971.08  4472.6  969.13  4494.2  963.74    4564  954.31
  4731.4  939.78    4910   928.9  4972.2  927.37  4989.4  920.93    4994   915.7
    5006   915.7  5013.5  921.87  5051.4   925.8  5267.4   923.5  5342.4  923.71
    5364  925.04  5379.9  923.46  5424.7   923.1  5434.1   925.1  5451.6  925.19
  5482.8  917.28  5491.5  923.29  5500.3  929.39  5531.1  931.12  5538.4  930.85
  5589.4  963.11  5638.7  988.61  5660.4  996.12  5684.8 1007.36  5711.6 1016.55
#Mann= 6 ,-1 , 0
  4392.1     .06       0  4989.4    .054       0  5013.5     .06       0
  5267.4     .09       0  5491.5     .06       0  5531.1     .09       0
#XS Ineff= 3 ,-1
    4400  4962.5   925.5    5038    5375   925.5    5375    5600     935
Permanent Ineff=
       T       T       F
Bank Sta=4989.4,5013.5
Exp/Cntr=0.5,0.3

Type RM Length L Ch R = 1 ,34373   ,1156,1156,1156
BEGIN DESCRIPTION:
Cane_Creek_XS-55
END DESCRIPTION:
XS GIS Cut Line= 5
      1151317.28        649165.5      1151119.36       649082.17
      1150874.57        649040.5      1150525.61       649076.96
      1150270.22       649156.19
#Sta/Elev= 30
  4521.6  981.35  4556.6  980.76  4563.5  979.47  4602.5  977.35  4650.3  969.52
  4695.4   954.9  4715.2  945.28  4736.3  931.87    4747  926.42  4757.5  923.84
  4774.8  923.72  4899.4  923.33  4946.3  923.24  4978.3     917  4987.6   913.7
  5012.4   913.7  5024.1  915.69  5027.5   917.5  5057.2  921.03  5068.8  922.26
 5125.16  923.65  5416.6  924.67  5441.6  925.52  5485.8  931.02  5502.3  930.19
  5517.9  932.57  5533.8  939.02  5557.6  946.58  5581.6  952.19  5602.9  963.18
#Mann= 7 ,-1 , 0
  4521.6     .09       0  4774.8     .06       0  4899.4     .09       0
  4978.3    .054       0  5027.5     .09       0  5057.2     .06       0
  5485.8     .09       0
Bank Sta=4978.3,5027.5
Exp/Cntr=0.3,0.1

Type RM Length L Ch R = 1 ,33217   ,647,647,647
BEGIN DESCRIPTION:
Cane_Creek_XS-54
END DESCRIPTION:
XS GIS Cut Line= 4
      1151340.16        648128.6      1151087.48       648025.23
      1150804.16       648029.05      1150171.04       648099.14
#Sta/Elev= 30
  4605.2  996.48  4654.6  987.59    4707  972.76  4736.2  961.11  4752.3  952.43
  4781.4  946.42  4803.8  937.13  4827.3  928.89  4857.9  924.31  4887.8  922.11
  4951.7  920.81  4962.7  920.74  4977.8  917.16  4986.1     910  5013.9     910
  5023.1  917.93 5027.46  919.55    5066  920.26  5310.6   918.8  5540.6  921.26
  5582.4  923.01  5610.4  925.38  5631.8  929.22  5645.9  929.67    5661  929.73
  5691.7  940.17    5719  947.03  5747.3  957.56  5763.2  961.08  5798.6  976.38
#Mann= 7 ,-1 , 0
  4605.2     .09       0  4803.8     .06       0  4951.7     .09       0
  4977.8     .05       0  5023.1     .09       0    5066     .06       0
  5645.9     .09       0
Bank Sta=4977.8,5023.1
Exp/Cntr=0.5,0.3

Type RM Length L Ch R = 1 ,32570   ,42,42,42
BEGIN DESCRIPTION:
Cane_Creek_XS-53
END DESCRIPTION:
XS GIS Cut Line= 6
        1151465.        647584.2      1151335.04       647542.49
      1151209.91       647446.23      1150925.94       647409.33
      1150324.32       647526.45      1150024.31       647733.41
#Sta/Elev= 30
  4322.7  958.97  4354.5  955.17  4428.2  949.86  4466.1  943.61  4508.1  939.27
  4580.2   932.8  4716.6  923.02    4914  917.88  4958.4  919.02  4983.9  914.78
  4991.5     908  5008.5     908    5010     910  5019.3  913.34  5040.3  914.49
  5050.6  917.09  5081.6  916.41  5227.4  916.77  5270.6  918.32  5407.2  919.49
  5483.8   924.2  5528.9   931.5  5557.7  931.67    5571   933.1  5580.3  935.34
  5678.4  944.39    5734  955.36  5778.1  960.37  5816.4  969.12  5884.9  981.73
#Mann= 7 ,-1 , 0
  4322.7     .09       0  4508.1     .06       0    4914     .09       0
  4983.9     .05       0  5019.3     .09       0  5081.6     .06       0
    5571     .09       0
#XS Ineff= 2 , 0
       0    4960  917.08    5040       0  917.21
Permanent Ineff=
       F       F
Bank Sta=4983.9,5019.3
Exp/Cntr=0.5,0.3