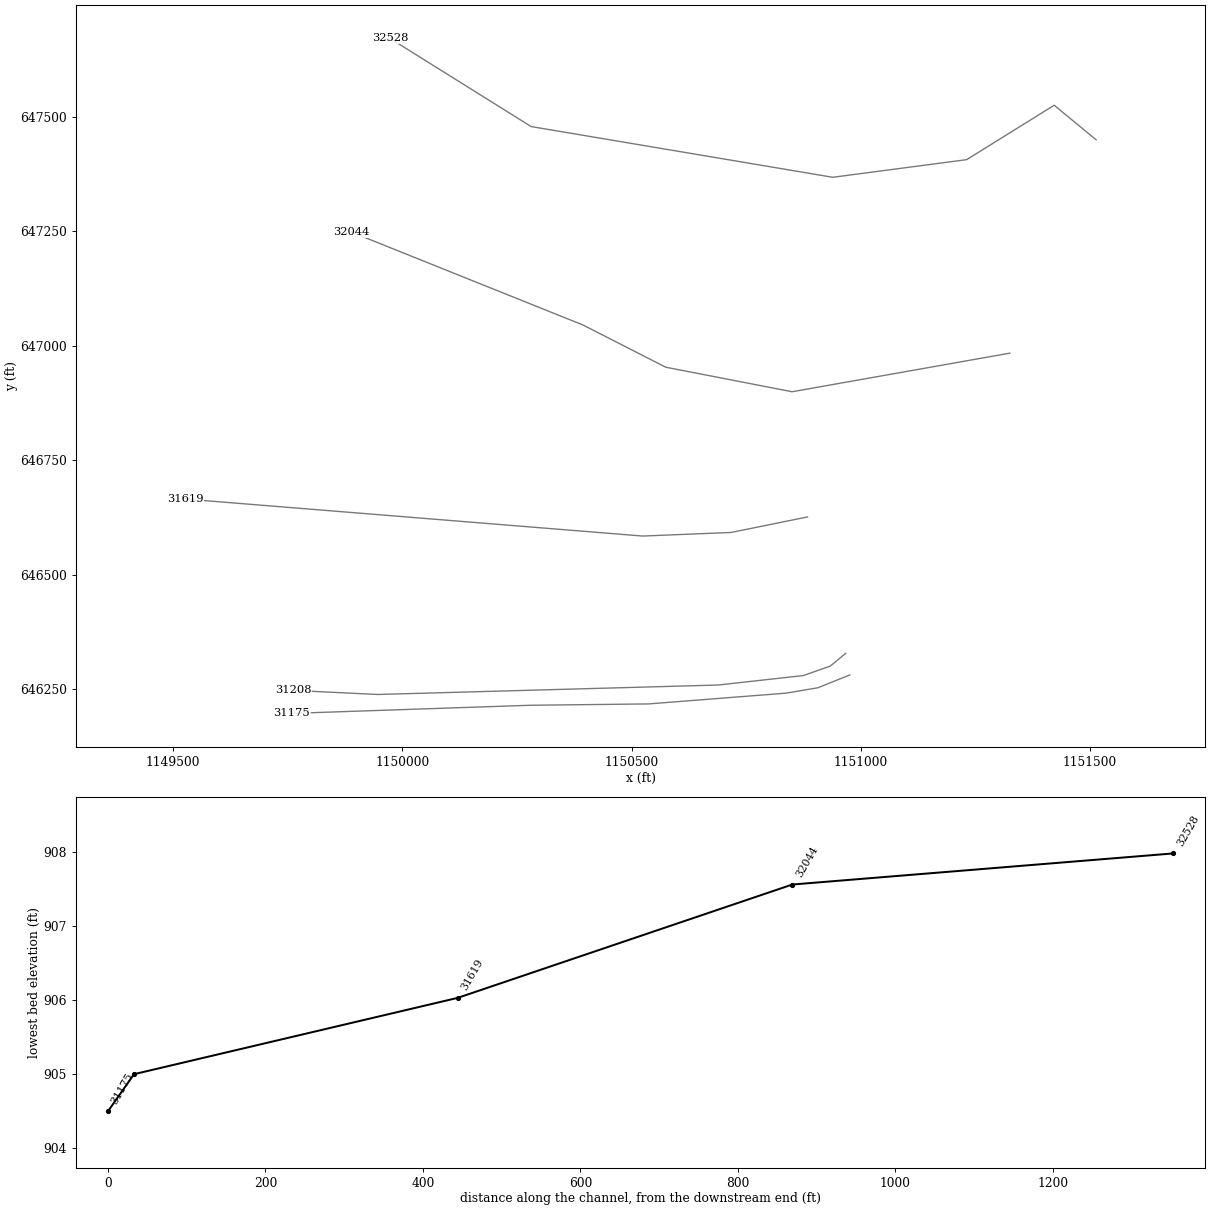
HEC-RAS study lds_cane_crk.prj: Cane Creek Limited Detail Study

--- lds_cane_crk.g01 (geometry) --- (continued)

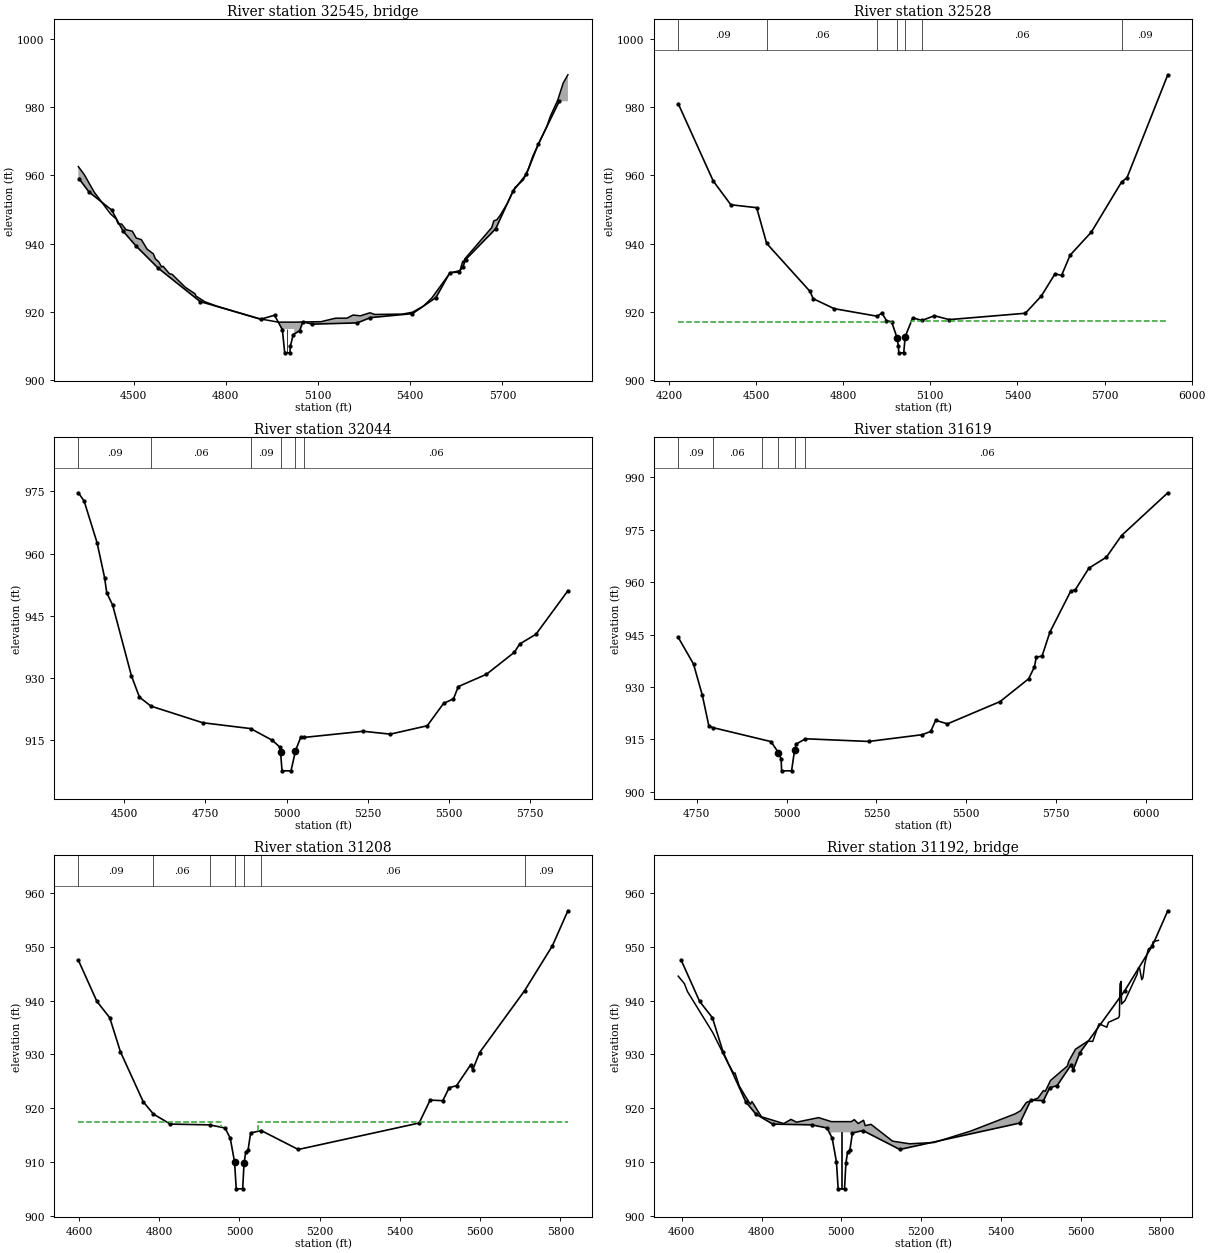
Type RM Length L Ch R = 3 ,32545   ,,,
BEGIN DESCRIPTION:
Cane_Creek_XS-52
Structure ID: Privat Dr off of Cane Creek Rd
Approximate Survey Structure
END DESCRIPTION:
Bridge Culvert--1,0,-1,-1, 0
Deck Dist Width WeirC Skew NumUp NumDn MinLoCord MaxHiCord MaxSubmerge Is_Ogee
17.5,15,3,0, 60, 60, , , , 0, 1,1,,
    4320  4339.2  4371.6  4424.7    4443  4449.8  4460.7  4475.2  4495.6  4508.4
  4525.3  4543.5  4564.4  4570.6  4581.4    4591  4595.9  4616.4  4625.1  4668.8
  4699.8    4703  4731.3  4771.3  4904.4  4972.4  4977.5  4977.5  5022.5  5022.5
  5109.7  5157.1  5193.9  5213.9  5237.8  5268.7  5284.7  5374.5  5407.2  5442.4
  5469.8  5529.4  5561.9  5570.7  5573.4    5577  5665.1  5671.9  5681.9  5692.9
  5716.1  5740.6  5768.1  5785.4  5799.1  5843.8    5856  5879.7  5897.7    5913
  962.58  960.25   955.1  948.74  947.24  945.75  945.77  944.09  943.66  941.65
  941.16  938.42  936.98  935.56  934.71  933.17  933.38  931.17  931.01  927.16
   925.3  924.63  922.99  921.66  918.06  916.97     917     917     917     917
  917.13  918.16  918.17  919.08  918.85  919.74  919.25  919.36   919.9  921.68
  924.03  931.41  932.11  934.83  934.47  935.48  944.71  946.67  947.01  948.35
  951.83  956.44  958.67  962.19   965.7  974.21  977.35  982.02  987.06  989.49
     888     888     888     888     888     888     888     888     888     888
     888     888     888     888     888     888     888     888     888     888
     888     888     888     888     888     888     888     915     915     888
     888     888     888     888     888     888     888     888     888     888
     888     888     888     888     888     888     888     888     888     888
     888     888     888     888     888     888     888     888     888     888
    4320  4339.2  4371.6  4424.7    4443  4449.8  4460.7  4475.2  4495.6  4508.4
  4525.3  4543.5  4564.4  4570.6  4581.4    4591  4595.9  4616.4  4625.1  4668.8
  4699.8    4703  4731.3  4771.3  4904.4  4972.4  4977.5  4977.5  5022.5  5022.5
  5109.7  5157.1  5193.9  5213.9  5237.8  5268.7  5284.7  5374.5  5407.2  5442.4
  5469.8  5529.4  5561.9  5570.7  5573.4    5577  5665.1  5671.9  5681.9  5692.9
  5716.1  5740.6  5768.1  5785.4  5799.1  5843.8    5856  5879.7  5897.7    5913
  962.58  960.25   955.1  948.74  947.24  945.75  945.77  944.09  943.66  941.65
  941.16  938.42  936.98  935.56  934.71  933.17  933.38  931.17  931.01  927.16
   925.3  924.63  922.99  921.66  918.06  916.97     917     917     917     917
  917.13  918.16  918.17  919.08  918.85  919.74  919.25  919.36   919.9  921.68
  924.03  931.41  932.11  934.83  934.47  935.48  944.71  946.67  947.01  948.35
  951.83  956.44  958.67  962.19   965.7  974.21  977.35  982.02  987.06  989.49
     888     888     888     888     888     888     888     888     888     888
     888     888     888     888     888     888     888     888     888     888
     888     888     888     888     888     888     888     915     915     888
     888     888     888     888     888     888     888     888     888     888
     888     888     888     888     888     888     888     888     888     888
     888     888     888     888     888     888     888     888     888     888
Pier Skew, UpSta & Num, DnSta & Num=  ,5000, 2 ,5000, 2 , 0 , 0 , 0 ,,
       1       1
     905     915
       1       1
     905     915
BR Coef= 1 , 1 , 0 ,1.25, 0 ,,,0.8,0,2,0,
WSPro=,,,, 1 ,,,, 0 ,,,, 0 ,,,,-1 ,-1 ,-1 , 0 , 0 , 0 , 0 , 0
BC Design=,, 0 ,, 0 ,,,,,,
BC HTab HWMax=981.73

Type RM Length L Ch R = 1 ,32528   ,484,484,484
BEGIN DESCRIPTION:
Cane_Creek_XS-51
END DESCRIPTION:
XS GIS Cut Line= 6
      1151513.13       647449.44      1151421.68       647524.84
      1151230.76       647406.12      1150938.78       647367.62
        1150281.       647478.32      1149972.97       647670.84
#Sta/Elev= 30
  4231.9  981.01  4352.6  958.33    4413  951.39    4502  950.53  4536.4  940.06
  4685.5  926.01  4696.8  923.85  4768.9  920.93    4917  918.71  4933.5  919.66
    4949  917.41  4966.9  917.07  4985.1  912.46    4990  909.98  4991.5  907.98
  5008.5  907.98  5013.4  912.75  5039.6  918.24  5071.7  917.47  5113.8  918.86
  5165.4  917.72  5427.3  919.58  5482.3  924.64  5529.6  931.16    5552  930.67
  5581.3   936.6  5654.8  943.41  5758.4  958.03  5777.5  959.36  5917.8  989.49
#Mann= 7 ,-1 , 0
  4231.9     .09       0  4536.4     .06       0    4917     .09       0
  4985.1     .05       0  5013.4     .09       0  5071.7     .06       0
  5758.4     .09       0
#XS Ineff= 2 , 0
       0    4968  917.09    5032       0  917.23
Permanent Ineff=
       F       F
Bank Sta=4985.1,5013.4
Exp/Cntr=0.5,0.3

Type RM Length L Ch R = 1 ,32044   ,425,425,425
BEGIN DESCRIPTION:
Cane_Creek_XS-50
END DESCRIPTION:
XS GIS Cut Line= 5
      1151324.84       646983.86      1150850.11       646899.64
      1150574.45       646953.24      1150394.51       647045.12
      1149889.14       647248.03
#Sta/Elev= 30
    4358  974.68  4375.8   972.7  4415.7  962.65    4439  954.17  4445.7   950.5
  4463.8  947.57  4521.6  930.53  4546.4  925.35    4582  923.18  4741.5  919.17
  4889.3  917.76    4956  914.94  4978.7  913.34  4981.6  912.07  4986.1  907.56
  5013.9  907.56  5027.6  912.42  5044.2  915.73  5053.3  915.62  5236.4  917.11
    5320  916.42  5433.8  918.44  5484.4  923.85  5514.8  924.93  5529.5  927.89
  5616.5  930.87  5702.6  936.18  5718.8  938.17  5769.1  940.53  5867.6  951.03
#Mann= 6 ,-1 , 0
    4358     .09       0    4582     .06       0  4889.3     .09       0
  4981.6     .05       0  5027.6     .09       0  5053.3     .06       0
Bank Sta=4981.6,5027.6
Exp/Cntr=0.3,0.1

Type RM Length L Ch R = 1 ,31619   ,411,411,411
BEGIN DESCRIPTION:
Cane_Creek_XS-49
END DESCRIPTION:
XS GIS Cut Line= 4
      1150883.68       646626.44      1150717.02       646592.59
      1150524.31       646584.77      1149526.91        646665.5
#Sta/Elev= 30
  4698.2  944.21  4740.8  936.56  4765.3  927.65  4783.7   918.8  4794.5   918.4
 4956.61  914.39  4977.4  911.22  4984.9  909.41  4986.1  906.03  5013.9  906.03
  5022.3  911.96  5027.2   913.7  5052.6   915.2  5228.5  914.43  5378.1  916.37
  5401.3  917.29  5415.3  920.48    5448  919.46  5594.6  925.83    5674  932.33
  5690.4  935.75  5695.4   938.5  5711.7  938.88  5733.5  945.71  5791.5  957.42
  5804.2  957.82  5842.1  963.99  5890.8  967.12  5932.9  973.31  6061.8  985.54
#Mann= 6 ,-1 , 0
  4698.2     .09       0  4794.5     .06       0  4930.2     .09       0
  4977.4     .05       0  5022.3     .09       0  5052.6     .06       0
Bank Sta=4977.4,5022.3
Exp/Cntr=0.5,0.3

Type RM Length L Ch R = 1 ,31208   ,33,33,33
BEGIN DESCRIPTION:
Cane_Creek_XS-48
END DESCRIPTION:
XS GIS Cut Line= 6
      1150967.18       646328.92       1150933.3       646300.93
      1150874.38       646280.31      1150688.79       646259.69
      1149946.41       646239.07      1149762.29       646247.91
#Sta/Elev= 30
  4598.4  947.54  4644.7  939.86  4676.6  936.84  4703.4  930.48  4760.2  921.19
  4785.7   918.9  4827.9  917.04 4925.58   916.9  4964.1  916.32  4977.1  914.39
  4987.7  910.02    4992     905    5008     905  5011.4  909.75  5015.5  911.77
  5021.5  912.24  5027.8  915.39  5054.2  915.84  5146.6  912.32  5447.8  917.24
  5475.2   921.5  5506.8   921.4  5522.7  923.81    5541  924.19  5575.9  928.03
  5581.5  927.16  5598.4  930.34  5710.9  941.88  5779.9   950.2  5818.6  956.72
#Mann= 7 ,-1 , 0
  4598.4     .09       0  4785.7     .06       0 4925.58     .09       0
  4987.7     .05       0  5011.4     .09       0  5054.2     .06       0
  5710.9     .09       0
#XS Ineff= 2 , 0
       0    4955   917.5    5045       0   917.5
Permanent Ineff=
       F       F
Bank Sta=4987.7,5011.4
Exp/Cntr=0.5,0.3

Type RM Length L Ch R = 3 ,31192   ,,,
BEGIN DESCRIPTION:
Cane_Creek_XS-47
Structure ID: Big Rock Rd
Approximate Survey Structure
END DESCRIPTION:
Bridge Culvert--1,0,-1,-1, 0
Deck Dist Width WeirC Skew NumUp NumDn MinLoCord MaxHiCord MaxSubmerge Is_Ogee
10,12,3,0, 60, 60, , , , 0, 1,1,,
    4591  4606.3  4614.2  4677.6  4716.6  4730.3  4733.3    4744    4758  4771.9
    4776  4799.7  4855.5  4873.8  4887.5    4943    4975    4975    5025    5025
  5032.6  5042.1  5055.7  5059.8  5074.4  5128.5  5171.1  5232.7  5324.9  5435.8
  5449.7  5463.8  5493.1  5506.8  5511.5  5524.5  5566.7  5570.3  5587.1  5617.8
  5630.3  5646.1  5665.7  5669.7  5695.1  5697.2  5698.8  5701.7  5702.7  5711.1
  5741.6  5744.6  5747.8  5753.3  5756.2  5760.9  5769.6  5778.4  5781.9  5795.1
  944.56  943.18  941.69  934.06  928.25  926.47  926.57  924.15  922.38  920.74
  921.24  918.41  917.14  917.92   917.4  918.25   917.5   917.5   917.5   917.5
  917.87  917.15  917.76  916.75     917  913.87  913.38  913.62  915.76  918.95
  919.54  921.06  921.89  923.28  923.15  925.16  927.84  928.74  930.97  932.47
  932.42   935.7  935.06  935.97  936.82  937.18   943.1   943.6  939.37  940.01
  944.88  946.07  946.06  943.91  944.26  946.86   949.6  950.06  950.97  951.22
     885     885     885     885     885     885     885     885     885     885
     885     885     885     885     885     885     885   915.5   915.5     885
     885     885     885     885     885     885     885     885     885     885
     885     885     885     885     885     885     885     885     885     885
     885     885     885     885     885     885     885     885     885     885
     885     885     885     885     885     885     885     885     885     885
    4591  4606.3  4614.2  4677.6  4716.6  4730.3  4733.3    4744    4758  4771.9
    4776  4799.7  4855.5  4873.8  4887.5    4943    4975    4975    5025    5025
  5032.6  5042.1  5055.7  5059.8  5074.4  5128.5  5171.1  5232.7  5324.9  5435.8
  5449.7  5463.8  5493.1  5506.8  5511.5  5524.5  5566.7  5570.3  5587.1  5617.8
  5630.3  5646.1  5665.7  5669.7  5695.1  5697.2  5698.8  5701.7  5702.7  5711.1
  5741.6  5744.6  5747.8  5753.3  5756.2  5760.9  5769.6  5778.4  5781.9  5795.1
  944.56  943.18  941.69  934.06  928.25  926.47  926.57  924.15  922.38  920.74
  921.24  918.41  917.14  917.92   917.4  918.25   917.5   917.5   917.5   917.5
  917.87  917.15  917.76  916.75     917  913.87  913.38  913.62  915.76  918.95
  919.54  921.06  921.89  923.28  923.15  925.16  927.84  928.74  930.97  932.47
  932.42   935.7  935.06  935.97  936.82  937.18   943.1   943.6  939.37  940.01
  944.88  946.07  946.06  943.91  944.26  946.86   949.6  950.06  950.97  951.22
     885     885     885     885     885     885     885     885     885     885
     885     885     885     885     885     885     885   915.5   915.5     885
     885     885     885     885     885     885     885     885     885     885
     885     885     885     885     885     885     885     885     885     885
     885     885     885     885     885     885     885     885     885     885
     885     885     885     885     885     885     885     885     885     885
Pier Skew, UpSta & Num, DnSta & Num=  ,5000, 2 ,5000, 2 , 0 , 0 , 0 ,,
       1       1
     900   915.5
       1       1
     900   915.5
BR Coef= 1 , 1 , 0 ,1.25, 0 ,,,0.8,0,2,0,
WSPro=,,,, 1 ,,,, 0 ,,,, 0 ,,,,-1 ,-1 ,-1 , 0 , 0 , 0 , 0 , 0
BC Design=,, 0 ,, 0 ,,,,,,
BC HTab HWMax=956.72

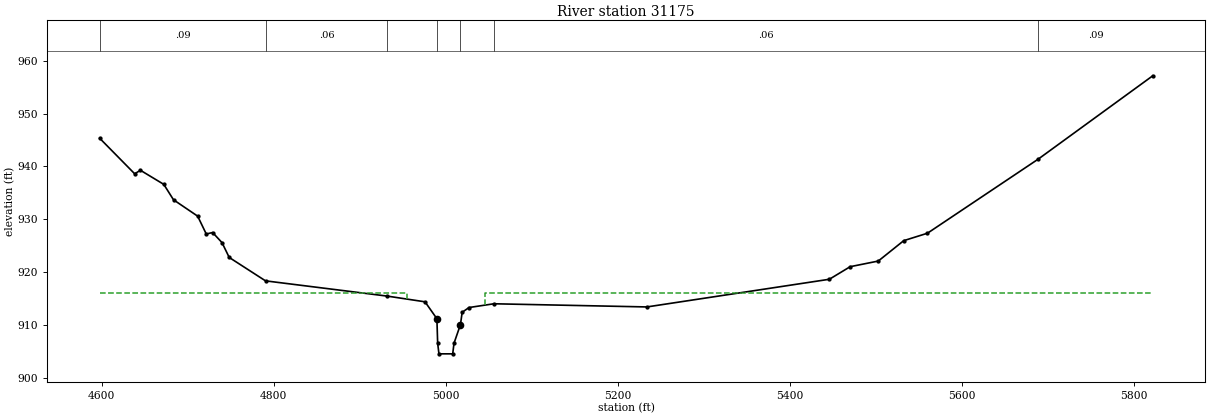
Type RM Length L Ch R = 1 ,31175   ,445,445,445
BEGIN DESCRIPTION:
Cane_Creek_XS-46
END DESCRIPTION:
XS GIS Cut Line= 6
      1150976.02       646281.78      1150906.79        646253.8
      1150837.56       646242.01      1150537.07       646218.45
      1150277.83        646215.5      1149759.34       646197.82
#Sta/Elev= 30
  4597.4  945.33  4638.1   938.6  4644.9  939.25    4672  936.59  4683.3  933.67
  4711.4  930.57  4721.4  927.19  4728.8  927.47  4739.7  925.56  4748.1  922.75
  4790.3  918.32 4931.97  915.43  4975.8  914.35  4989.6  911.15  4990.5   906.5
    4992   904.5    5008   904.5  5009.5   906.5    5017  910.04 5019.01  912.37
 5026.97  913.27  5055.9  913.98  5233.8  913.38    5446  918.62  5470.2     921
  5502.9  922.07  5532.5  925.93  5560.1  927.34    5689  941.38  5822.1  957.15
#Mann= 7 ,-1 , 0
  4597.4     .09       0  4790.3     .06       0 4931.97     .09       0
  4989.6     .05       0    5017     .09       0  5055.9     .06       0
    5689     .09       0
#XS Ineff= 2 , 0
       0    4955     916    5045       0     916
Permanent Ineff=
       F       F
Bank Sta=4989.6,5017
Exp/Cntr=0.5,0.3