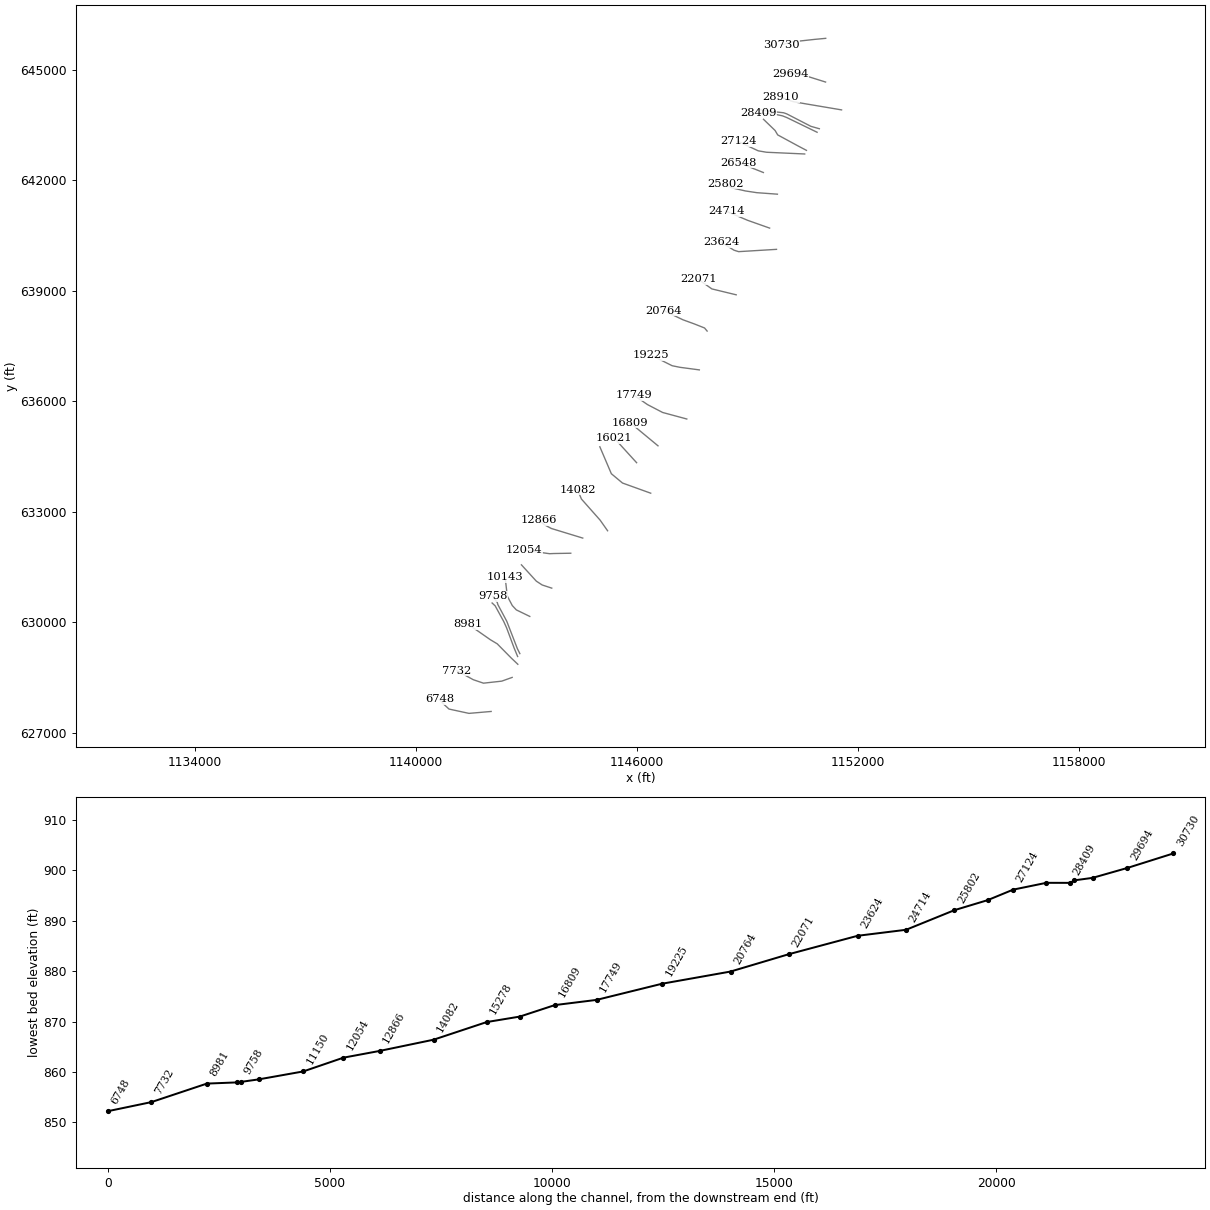
HEC-RAS study lds_cane_crk.prj: Cane Creek Limited Detail Study

--- lds_cane_crk.g01 (geometry) --- (continued)

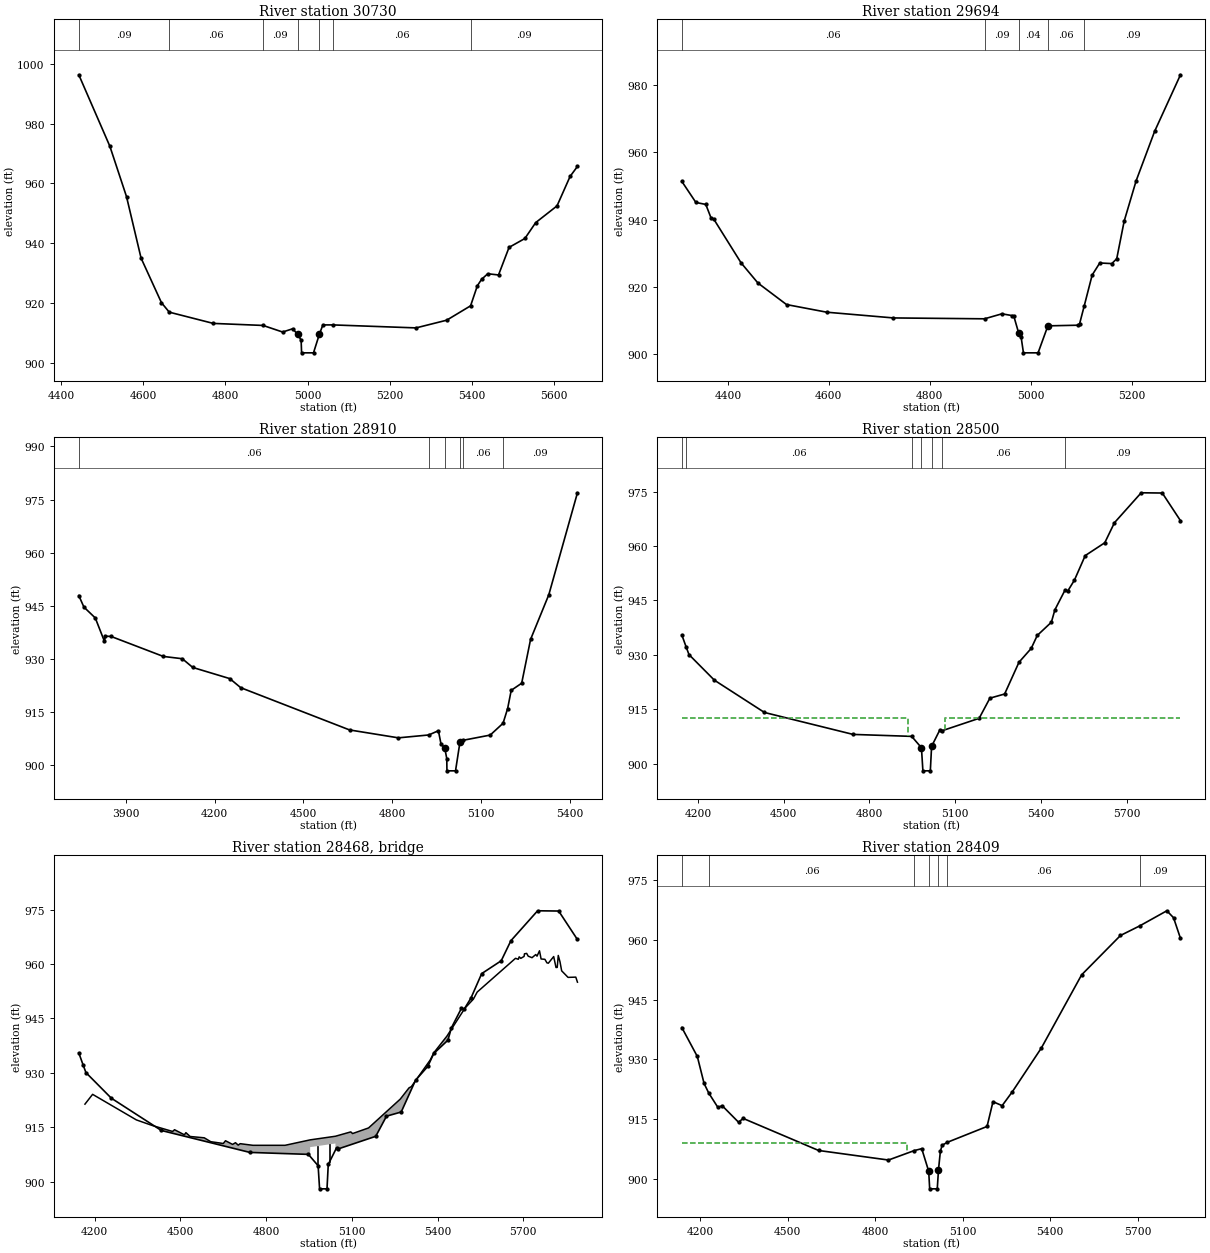
Type RM Length L Ch R = 1 ,30730   ,1036,1036,1036
BEGIN DESCRIPTION:
Cane_Creek_XS-45
END DESCRIPTION:
XS GIS Cut Line= 5
      1151121.93       645854.45      1150800.34       645823.82
      1150455.77       645785.53      1150222.23       645758.73
       1149923.6       645682.16
#Sta/Elev= 30
  4443.5  996.31  4519.1  972.41  4559.6  955.57    4595  935.02  4644.6  920.11
  4663.6  916.94  4770.7  913.18  4891.8   912.5  4939.3   910.3  4963.9  911.39
  4975.6  909.56  4984.4   907.6  4985.5  903.34  5014.5  903.34  5028.6  909.49
  5037.3  912.68  5061.2  912.68  5263.9  911.68  5338.4  914.25  5396.6  919.06
  5413.1  925.77  5423.5  927.94  5438.4  929.78  5464.6  929.38  5490.2   938.6
  5528.7  941.57    5555  946.88  5606.9  952.47  5638.7  962.33  5656.6  965.67
#Mann= 7 ,-1 , 0
  4443.5     .09       0  4663.6     .06       0  4891.8     .09       0
  4975.6     .05       0  5028.6     .09       0  5061.2     .06       0
  5396.6     .09       0
Bank Sta=4975.6,5028.6
Exp/Cntr=0.3,0.1

Type RM Length L Ch R = 1 ,29694   ,784,784,784
BEGIN DESCRIPTION:
Cane_Creek_XS-44
END DESCRIPTION:
XS GIS Cut Line= 4
       1151118.1        644667.6      1150593.59       644832.23
      1150417.48       644870.51      1150160.97       644897.31
#Sta/Elev= 30
  4308.7  951.35  4336.6  945.09  4356.2  944.51  4366.4  940.57  4371.9  940.17
  4426.2  927.15  4459.5  921.18  4516.1  914.79  4595.9  912.52  4727.9  910.82
  4908.4  910.56  4942.8  912.04 4963.44  911.51 4966.53  911.28  4975.9  906.42
  4980.8  905.22  4985.5  900.46  5014.5  900.46  5033.9  908.47  5093.2  908.66
  5096.6     909    5106  914.44  5121.6  923.54  5136.7  927.13  5160.6  926.95
  5170.3  928.39    5185  939.53  5208.8  951.55  5245.4  966.21  5296.6  982.99
#Mann= 5 ,-1 , 0
  4308.7     .06       0  4908.4     .09       0  4975.9     .04       0
  5033.9     .06       0    5106     .09       0
Bank Sta=4975.9,5033.9
Exp/Cntr=0.3,0.1

Type RM Length L Ch R = 1 ,28910   ,410,410,410
BEGIN DESCRIPTION:
Cane_Creek_XS-43
END DESCRIPTION:
XS GIS Cut Line= 4
      1151552.01       643911.28        1150565.       644077.94
      1150236.87       644135.23      1149905.99       644255.79
#Sta/Elev= 30
  3740.6  947.95  3757.9  944.69  3796.4  941.62  3827.5  934.99  3830.1   936.5
    3850   936.4  4026.4  930.77  4090.6  930.12    4126  927.66  4251.2  924.51
  4288.2  921.95  4656.2  910.03  4821.4   907.8    4924  908.61  4956.6  909.81
  4965.6  905.99  4977.9  905.01  4984.9  901.94  4985.5  898.49  5014.5  898.49
  5029.6  906.66  5039.5   907.1  5131.8  908.58  5175.2  911.91  5190.7  916.06
  5202.8   921.2  5238.2  923.21  5268.3  935.58  5329.9  948.16  5426.8  976.94
#Mann= 6 ,-1 , 0
  3740.6     .06       0    4924     .09       0  4977.9     .05       0
  5029.6     .09       0  5039.5     .06       0  5175.2     .09       0
Bank Sta=4977.9,5029.6
Exp/Cntr=0.5,0.3

Type RM Length L Ch R = 1 ,28500   ,91,91,91
BEGIN DESCRIPTION:
Cane_Creek_XS-42
END DESCRIPTION:
XS GIS Cut Line= 6
       1150948.8       643399.81      1150720.08       643464.54
       1150064.1       643803.32      1149977.79       643833.53
      1149490.12       643887.47      1149308.87       643924.15
#Sta/Elev= 30
  4143.9  935.47  4158.7  932.22    4169  930.04  4257.8  922.99  4432.9  914.09
  4742.9  908.04  4947.8   907.5  4981.9  904.37    4987     898    5013     898
  5017.4  904.74  5046.4   909.3  5052.8  909.02  5183.7  912.48  5221.3  918.03
  5272.8  919.18    5323  927.93  5365.8  931.75  5386.9  935.32  5436.3  938.97
  5448.6  942.39  5483.6  947.76  5493.1  947.51  5516.9  950.57  5554.6  957.33
    5623  960.87  5656.9   966.4  5750.4  974.65  5824.2  974.58  5887.8  966.96
#Mann= 7 ,-1 , 0
  4143.9     .09       0  4158.7     .06       0  4947.8     .09       0
  4981.9     .05       0  5017.4     .09       0  5052.8     .06       0
  5483.6     .09       0
#XS Ineff= 2 , 0
       0  4936.5   912.5  5063.5       0   912.5
Permanent Ineff=
       F       F
Bank Sta=4981.9,5017.4
Exp/Cntr=0.5,0.3

Type RM Length L Ch R = 3 ,28468   ,,,
BEGIN DESCRIPTION:
Cane_Creek_XS-41
Structure ID: Ed Thompson Rd
Approximate Survey Structure
END DESCRIPTION:
Bridge Culvert--1,0,-1,-1, 0
Deck Dist Width WeirC Skew NumUp NumDn MinLoCord MaxHiCord MaxSubmerge Is_Ogee
21,22,3,0, 60, 60, , , , 0, 1,1,,
  4165.5  4192.3  4345.6  4402.1  4472.2  4479.2  4513.5    4519  4533.8  4583.2
  4605.8  4649.8  4657.6  4682.3  4692.6    4702  4708.9  4753.6    4866    4954
    4954  5042.5  5042.5  5096.2  5102.6  5158.5  5269.4  5300.2  5308.4  5374.5
  5387.6    5433  5496.3  5525.6  5538.8    5673  5682.8  5685.9  5691.5    5703
  5704.4  5712.1  5717.4  5730.8  5743.9  5748.3    5757  5762.6  5775.9    5783
    5788  5806.7  5814.8  5819.1  5822.7  5828.8  5834.6    5857  5884.1  5889.9
  921.35  924.05     917  915.44  913.82   914.3   912.9  913.49  912.43  912.07
     911   910.5  911.26  910.25  910.72  910.05  910.45     910     910   911.5
   911.5   912.5   912.5   913.7  913.24  914.79  922.73  925.84  926.18  933.53
  935.57  940.11  947.84   950.3  952.24  961.55  961.28  961.96  961.53  962.07
  962.79   962.9  962.14  961.72  962.58  962.14  963.62  961.36  961.27   960.3
   960.2  962.03  959.01  959.04  962.34  960.58   958.1  956.29  956.36  954.97
     878     878     878     878     878     878     878     878     878     878
     878     878     878     878     878     878     878     878     878     878
   909.5   910.5     878     878     878     878     878     878     878     878
     878     878     878     878     878     878     878     878     878     878
     878     878     878     878     878     878     878     878     878     878
     878     878     878     878     878     878     878     878     878     878
  4165.5  4192.3  4345.6  4402.1  4472.2  4479.2  4513.5    4519  4533.8  4583.2
  4605.8  4649.8  4657.6  4682.3  4692.6    4702  4708.9  4753.6    4866    4954
    4954  5042.5  5042.5  5096.2  5102.6  5158.5  5269.4  5300.2  5308.4  5374.5
  5387.6    5433  5496.3  5525.6  5538.8    5673  5682.8  5685.9  5691.5    5703
  5704.4  5712.1  5717.4  5730.8  5743.9  5748.3    5757  5762.6  5775.9    5783
    5788  5806.7  5814.8  5819.1  5822.7  5828.8  5834.6    5857  5884.1  5889.9
  921.35  924.05     917  915.44  913.82   914.3   912.9  913.49  912.43  912.07
     911   910.5  911.26  910.25  910.72  910.05  910.45     910     910   911.5
   911.5   912.5   912.5   913.7  913.24  914.79  922.73  925.84  926.18  933.53
  935.57  940.11  947.84   950.3  952.24  961.55  961.28  961.96  961.53  962.07
  962.79   962.9  962.14  961.72  962.58  962.14  963.62  961.36  961.27   960.3
   960.2  962.03  959.01  959.04  962.34  960.58   958.1  956.29  956.36  954.97
     878     878     878     878     878     878     878     878     878     878
     878     878     878     878     878     878     878     878     878     878
   909.5   910.5     878     878     878     878     878     878     878     878
     878     878     878     878     878     878     878     878     878     878
     878     878     878     878     878     878     878     878     878     878
     878     878     878     878     878     878     878     878     878     878
Pier Skew, UpSta & Num, DnSta & Num=  ,4978.8, 2 ,4978.8, 2 , 0 , 0 , 0 ,0,0
       2       2
  901.91     910
       2       2
  903.88     910
Pier Skew, UpSta & Num, DnSta & Num=  ,5021.3, 2 ,5021.3, 2 , 0 , 0 , 0 ,0,0
       2       2
  901.17   910.5
       2       2
  905.24   910.5
Abutment Skew #Up #Dn= , 2 , 2
  4957.5    4959
     908  906.36
  4957.5    4959
     908  907.55
Abutment Skew #Up #Dn= , 2 , 2
    5041  5042.5
  907.96     908
    5041  5042.5
  909.12     908
BR Coef= 1 , 1 , 0 ,1.25, 0 ,,,0.8,0,2,0,
WSPro=,,,, 1 ,,,, 0 ,,,, 0 ,,,,-1 ,-1 ,-1 , 0 , 0 , 0 , 0 , 0
BC Design=,, 0 ,, 0 ,,,,,,
BC HTab HWMax=975.52

Type RM Length L Ch R = 1 ,28409   ,538,538,538
BEGIN DESCRIPTION:
Cane_Creek_XS-40
END DESCRIPTION:
XS GIS Cut Line= 6
      1150887.92       643303.85       1150067.6       643702.29
      1149950.42       643749.16       1149692.6       643803.85
      1149387.92       643815.57      1149290.26       643839.01
#Sta/Elev= 30
  4137.8     938  4190.9  930.73  4214.1  923.95  4230.1  921.54  4261.5  917.93
  4276.1  918.37  4332.2  914.22    4348  915.18  4606.4  907.13  4845.8  904.73
  4934.5  907.11  4959.8  907.58  4983.7  901.91    4987   897.5    5013   897.5
  5017.2  902.29  5023.6   906.9  5029.6  908.44  5047.5  909.18  5183.6  913.16
  5203.9  919.38  5235.2  918.38  5270.4  921.89  5369.6  932.85  5507.6  951.22
  5640.7   961.1  5706.2  963.49  5799.6   967.3  5822.5  965.56  5846.3  960.37
#Mann= 7 ,-1 , 0
  4137.8     .09       0  4230.1     .06       0  4934.5     .09       0
  4983.7     .05       0  5017.2     .09       0  5047.5     .06       0
  5706.2     .09       0
#XS Ineff= 2 , 0
       0  4909.5   908.9    5060       0   908.9
Permanent Ineff=
       F       F
Bank Sta=4983.7,5017.2
Exp/Cntr=0.5,0.3

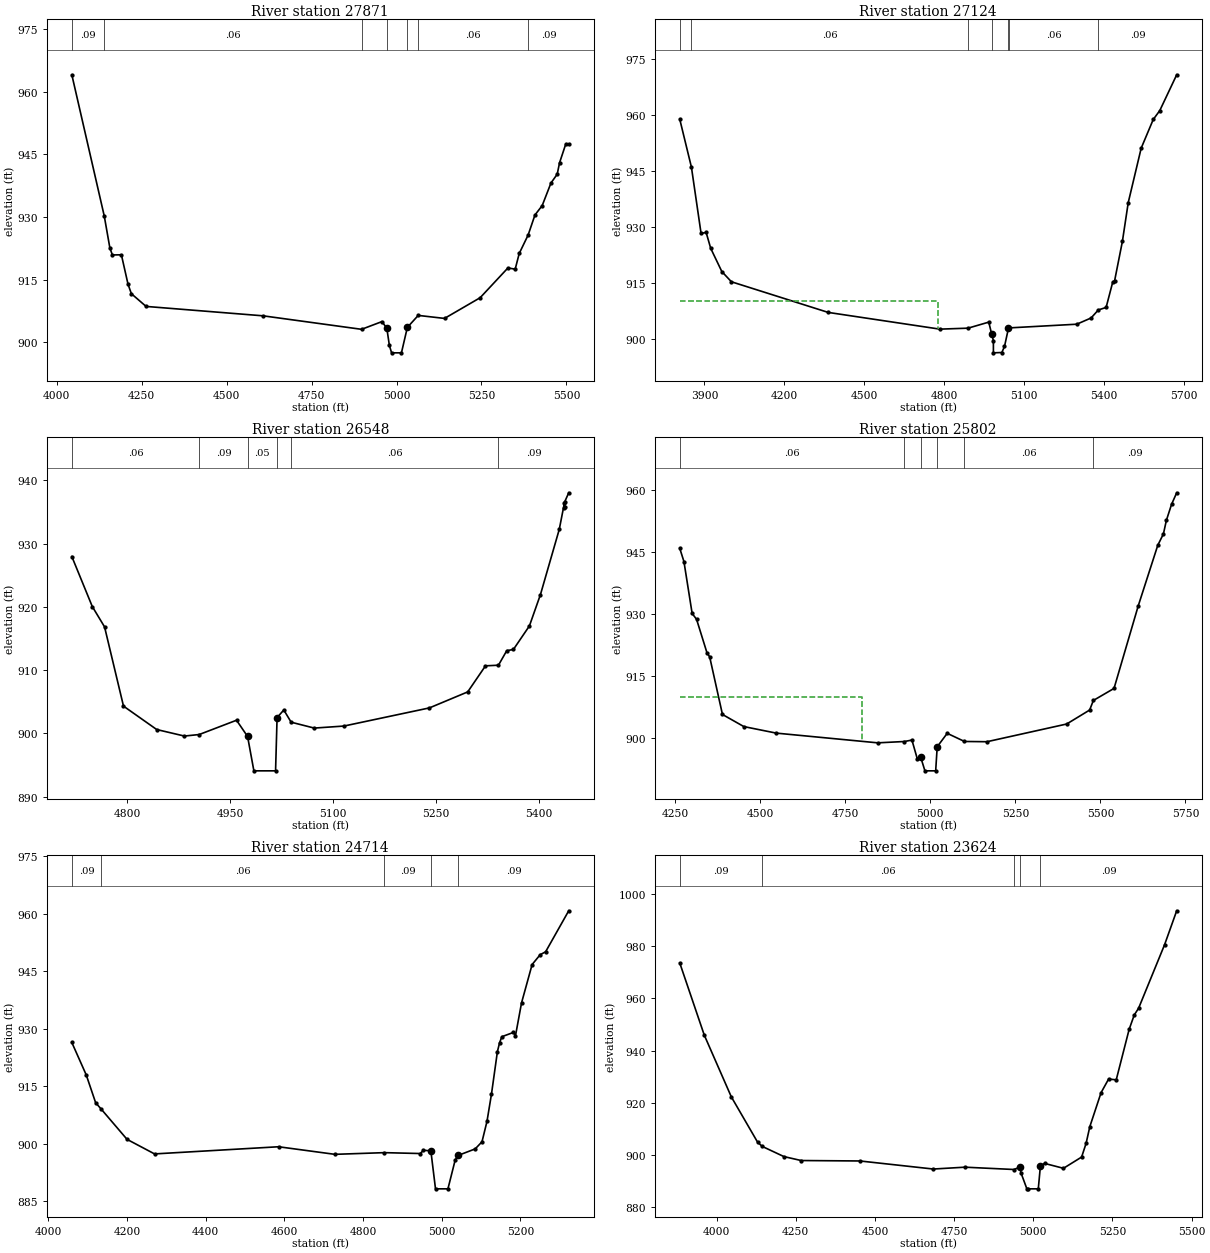
Type RM Length L Ch R = 1 ,27871   ,747,747,747
BEGIN DESCRIPTION:
Cane_Creek_XS-39
END DESCRIPTION:
XS GIS Cut Line= 5
       1150598.9       642812.49      1150392.39       642920.99
      1149818.37       643232.51      1149748.36       643351.51
      1149433.35       643656.03
#Sta/Elev= 30
  4044.3  964.07  4139.8  930.25  4156.3  922.61  4163.7  920.94  4190.2  920.98
  4209.8  913.91  4219.6  911.66  4262.9  908.62  4607.3  906.37  4897.1  903.14
  4957.2  904.99  4971.5  903.39    4979  899.28  4985.5  897.51  5014.5  897.51
  5031.9   903.6  5063.9  906.47  5141.3  905.75  5246.1   910.7  5327.9  917.83
  5349.3  917.54  5361.2   921.3  5387.4  925.71  5407.5  930.51  5428.8  932.76
  5454.6  938.16    5473  940.27  5479.9  943.01  5498.3  947.52  5506.9   947.5
#Mann= 7 ,-1 , 0
  4044.3     .09       0  4139.8     .06       0  4897.1     .09       0
  4971.5     .05       0  5031.9     .09       0  5063.9     .06       0
  5387.4     .09       0
Bank Sta=4971.5,5031.9
Exp/Cntr=0.3,0.1

Type RM Length L Ch R = 1 ,27124   ,576,576,576
BEGIN DESCRIPTION:
Cane_Creek_XS-38
END DESCRIPTION:
XS GIS Cut Line= 4
      1150551.98       642714.01      1149516.82       642760.88
      1149290.26       642799.94      1148747.29       643053.85
#Sta/Elev= 30
  3807.5  958.71  3851.2   945.9  3887.4  928.15  3906.4  928.42  3923.6  924.16
  3965.3  917.94  4001.3   915.2  4364.7  906.99  4783.8  902.51  4889.5  902.77
 4967.48  904.39  4978.6  901.12  4984.8  899.43  4984.9  896.16  5016.5  896.25
  5026.5  897.86  5041.5  902.78  5043.2  902.84  5297.8  903.83  5351.6   905.5
  5378.9  907.66    5408  908.32  5433.1  915.19  5439.7   915.4  5469.1     926
  5491.1  936.42  5539.7     951  5584.9  958.68  5609.5  961.07    5673  970.66
#Mann= 7 ,-1 , 0
  3807.5     .09       0  3851.2     .06       0  4889.5     .09       0
  4978.6     .05       0  5041.5     .09       0  5043.2     .06       0
  5378.9     .09       0
#XS Ineff= 2 , 0
       0    4775     910               0
Permanent Ineff=
       F       F
Bank Sta=4978.6,5041.5
Exp/Cntr=0.3,0.1

Type RM Length L Ch R = 1 ,26548   ,746,746,746
BEGIN DESCRIPTION:
Cane_Creek_XS-37
END DESCRIPTION:
XS GIS Cut Line= 2
      1149430.23       642210.58      1148757.61       642478.53
#Sta/Elev= 30
  4718.9  927.95  4748.7  920.05  4766.6  916.83  4794.2   904.3  4842.6   900.6
  4882.9  899.57  4904.5  899.81  4958.9  902.07    4975  899.51  4984.2  894.07
  5015.8  894.07    5018  902.49  5027.8  903.69  5038.5  901.76  5072.2  900.83
  5115.4  901.15    5240  904.02  5295.8  906.55  5321.7  910.67  5340.6  910.77
  5352.7  913.07  5362.4  913.26  5385.7  916.98  5401.8  921.94  5429.2  932.24
  5436.6  936.35  5436.7  935.57  5437.1  935.73  5437.3  936.64    5443  938.03
#Mann= 6 ,-1 , 0
  4718.9     .06       0  4904.5     .09       0    4975     .05       0
    5018     .09       0  5038.5     .06       0  5340.6     .09       0
Bank Sta=4975,5018
Exp/Cntr=0.3,0.1

Type RM Length L Ch R = 1 ,25802   ,1088,1088,1088
BEGIN DESCRIPTION:
Cane_Creek_XS-36
END DESCRIPTION:
XS GIS Cut Line= 5
      1149811.37       641622.44       1149251.2       641663.23
       1148942.6        641710.1      1148562.59       641797.32
      1148400.81       641909.45
#Sta/Elev= 30
  4263.7  945.86  4275.9  942.69    4300  930.14    4313  928.73  4343.6  920.63
  4351.5  919.66  4389.1  905.72    4452  902.79  4547.3  901.21  4845.4  898.86
  4923.7  899.18    4946  899.53  4961.6  895.05  4971.2  895.54  4984.2  892.09
  5015.8  892.09  5020.3  897.91  5049.7  901.16  5100.5  899.19  5166.5  899.13
  5400.8  903.41  5468.3  906.79  5479.3  909.11    5540  912.02  5611.4  932.04
  5668.6  946.63  5685.2  949.38  5693.9  952.66  5709.1  956.52  5724.2  959.32
#Mann= 6 ,-1 , 0
  4263.7     .06       0  4923.7     .09       0  4971.2     .05       0
  5020.3     .09       0  5100.5     .06       0  5479.3     .09       0
#XS Ineff= 2 , 0
       0    4800     910               0
Permanent Ineff=
       F       F
Bank Sta=4971.2,5020.3
Exp/Cntr=0.3,0.1

Type RM Length L Ch R = 1 ,24714   ,1090,1090,1090
BEGIN DESCRIPTION:
Cane_Creek_XS-35
END DESCRIPTION:
XS GIS Cut Line= 3
      1149599.76       640701.27       1149001.2       640913.23
      1148423.07       641159.32
#Sta/Elev= 30
  4059.6  926.42  4096.2  917.96  4120.1   910.7  4134.9  908.95    4200  901.12
  4269.9  897.32  4585.2  899.19  4728.3  897.21  4854.3  897.65  4945.4  897.42
  4953.6  898.28  4972.4  898.11  4984.2   888.2  5015.8   888.2  5034.1  895.68
  5041.6  896.92  5085.1  898.63  5102.4  900.49  5115.1  905.83  5126.5  912.95
  5141.6  924.05  5147.2  926.38  5152.9  927.93  5182.4  929.05  5187.5  928.16
  5202.9  936.75  5229.8  946.77  5250.4  949.35  5264.1   950.1  5322.9  960.81
#Mann= 5 ,-1 , 0
  4059.6     .09       0  4134.9     .06       0  4854.3     .09       0
  4972.4     .05       0  5041.6     .09       0
Bank Sta=4972.4,5041.6
Exp/Cntr=0.3,0.1

Type RM Length L Ch R = 1 ,23624   ,1553,1553,1553
BEGIN DESCRIPTION:
Cane_Creek_XS-34
END DESCRIPTION:
XS GIS Cut Line= 4
      1149786.35       640124.16      1148759.01       640061.66
      1148634.01       640100.73      1148286.35       640315.57
#Sta/Elev= 30
  3883.9  973.53  3961.2  945.92  4046.7  922.23  4129.5   904.9  4144.2  903.27
  4212.7  899.37  4267.1  897.86  4452.7  897.69  4684.4   894.6  4784.2  895.31
  4939.4  894.42  4957.3  895.37  4961.7  892.96  4979.6  887.06  4984.2  887.01
  5015.8  887.01  5022.5  895.79  5035.5  896.76  5095.3  894.88  5152.6  899.19
  5166.7  904.43  5178.6  910.88    5214  923.86  5237.8  929.08  5261.9  928.79
  5302.6  948.11  5318.8  953.64  5332.6  956.25  5414.5  980.55  5452.8  993.57
#Mann= 5 ,-1 , 0
  3883.9     .09       0  4144.2     .06       0  4939.4     .09       0
  4957.3     .05       0  5022.5     .09       0
Bank Sta=4957.3,5022.5
Exp/Cntr=0.3,0.1

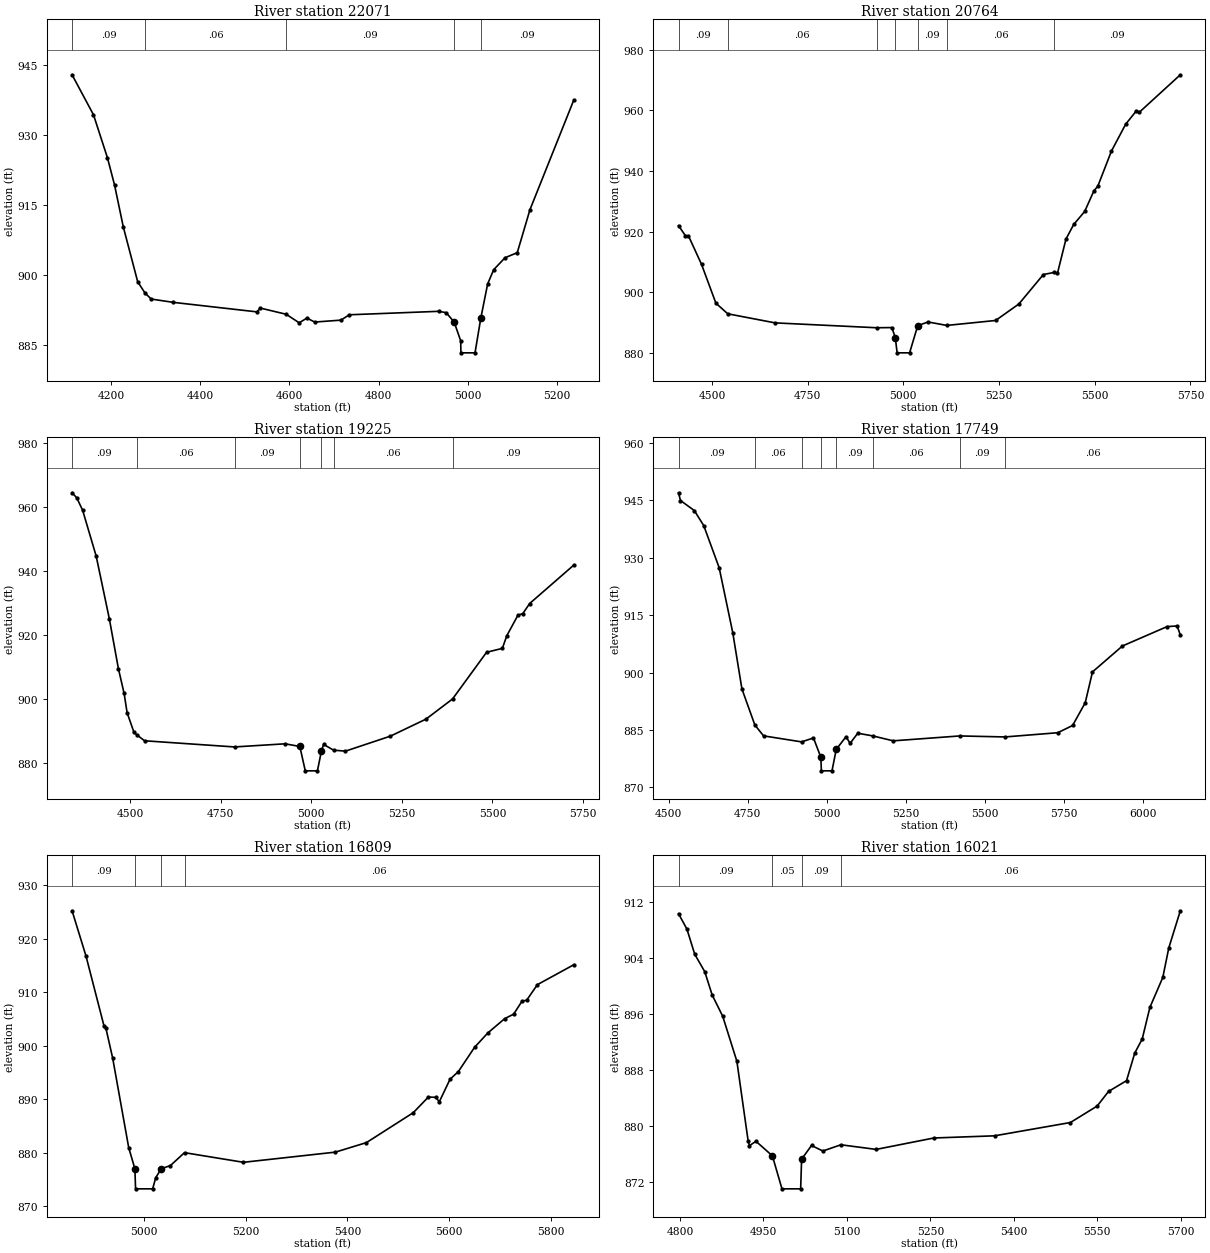
Type RM Length L Ch R = 1 ,22071   ,1307,1307,1307
BEGIN DESCRIPTION:
Cane_Creek_XS-33
END DESCRIPTION:
XS GIS Cut Line= 3
       1148692.6       638889.79      1148032.45       639049.94
      1147669.38        639306.8
#Sta/Elev= 30
  4113.2  942.96  4161.2  934.38  4192.3  925.21  4208.3  919.35    4228  910.33
  4260.2  898.59  4276.8  896.14  4290.6  894.88  4340.1  894.17  4527.5  892.13
  4534.8  892.95  4592.8  891.62  4621.9  889.79  4639.3   890.8  4656.6  889.95
  4715.4  890.36  4734.3  891.51  4934.5  892.25  4951.3  891.96  4969.1  889.94
  4983.7  885.93  4984.2  883.35  5015.8  883.35  5028.8  890.81  5044.1  898.13
  5057.6  901.17    5083  903.74  5110.4  904.82  5138.9  914.05  5237.2  937.58
#Mann= 5 ,-1 , 0
  4113.2     .09       0  4276.8     .06       0  4592.8     .09       0
  4969.1     .05       0  5028.8     .09       0
Bank Sta=4969.1,5028.8
Exp/Cntr=0.3,0.1

Type RM Length L Ch R = 1 ,20764   ,1539,1539,1539
BEGIN DESCRIPTION:
Cane_Creek_XS-32
END DESCRIPTION:
XS GIS Cut Line= 5
      1147903.78       637905.28      1147833.78       637989.28
      1147551.98       638100.73       1147251.2        638210.1
       1146728.8       638459.19
#Sta/Elev= 30
  4412.5  921.95  4430.2  918.67  4438.5  918.56  4472.7  909.12  4510.1  896.33
  4541.1  892.82  4664.8  889.82  4929.8  888.21    4970  888.27  4978.9  884.93
  4983.7  879.92  5016.3  879.92  5037.5   888.9  5064.4  890.12  5113.5  888.98
    5241  890.61  5301.8  896.06  5365.8  905.79    5394  906.49  5402.6  906.17
  5424.9  917.52  5445.2  922.35  5473.8  926.63  5498.2  933.53  5507.8  934.89
  5543.8  946.61  5580.9  955.46  5609.1  959.92  5616.7  959.42  5723.7  971.79
#Mann= 7 ,-1 , 0
  4412.5     .09       0  4541.1     .06       0  4929.8     .09       0
  4978.9     .05       0  5037.5     .09       0  5113.5     .06       0
    5394     .09       0
Bank Sta=4978.9,5037.5
Exp/Cntr=0.3,0.1

Type RM Length L Ch R = 1 ,19225   ,1476,1476,1476
BEGIN DESCRIPTION:
Cane_Creek_XS-31
END DESCRIPTION:
XS GIS Cut Line= 4
       1147692.6       636850.73      1147165.26       636921.04
      1146954.32       636964.01      1146384.28       637250.65
#Sta/Elev= 30
  4339.4  964.44  4352.3  962.88  4368.6  958.96    4406  944.63  4442.3  925.03
  4467.3  909.46  4483.1  901.69  4491.4  895.66  4509.9  889.68  4517.4  888.83
  4539.5  886.91  4787.9  884.98  4927.5  885.96  4968.2  885.13  4983.2  877.51
  5016.8  877.51  5027.7  883.68  5033.8  885.77  5061.4  883.97  5094.1  883.67
  5218.3  888.36  5316.5  893.68  5389.8  899.98  5483.7  914.57  5527.3   915.8
  5539.7  919.78  5570.3  926.16  5583.8  926.67  5602.7  929.82  5724.7  941.85
#Mann= 7 ,-1 , 0
  4339.4     .09       0  4517.4     .06       0  4787.9     .09       0
  4968.2     .05       0  5027.7     .09       0  5061.4     .06       0
  5389.8     .09       0
Bank Sta=4968.2,5027.7
Exp/Cntr=0.3,0.1

Type RM Length L Ch R = 1 ,17749   ,940,940,940
BEGIN DESCRIPTION:
Cane_Creek_XS-30
END DESCRIPTION:
XS GIS Cut Line= 4
       1147352.2       635517.14      1146696.51       635694.48
      1146284.79       635908.84      1145919.46       636162.42
#Sta/Elev= 30
  4531.1  946.97  4537.2  944.95    4581  942.33  4610.9  938.39  4659.7  927.38
  4702.8  910.38  4731.7  895.71  4772.6  886.29  4800.2  883.44  4920.4  881.87
  4958.2  882.89  4981.5  877.86  4983.2   874.3  5016.8   874.3  5030.3  879.91
  5061.3  883.24    5074  881.47  5098.4  884.13  5146.6  883.42  5210.4  882.14
  5420.9  883.42  5564.4  883.16  5731.4  884.26  5778.3  886.15  5818.3  892.09
  5841.3  900.16  5936.1  906.93  6077.5     912    6109  912.16  6119.3  909.82
#Mann= 8 ,-1 , 0
  4531.1     .09       0  4772.6     .06       0  4920.4     .09       0
  4981.5     .05       0  5030.3     .09       0  5146.6     .06       0
  5420.9     .09       0  5564.4     .06       0
Bank Sta=4981.5,5030.3
Exp/Cntr=0.3,0.1

Type RM Length L Ch R = 1 ,16809   ,788,788,788
BEGIN DESCRIPTION:
Cane_Creek_XS-29
END DESCRIPTION:
XS GIS Cut Line= 2
      1146570.86       634788.88      1145810.44       635419.08
#Sta/Elev= 30
  4858.2  925.24  4885.5  916.82  4921.1   903.7  4924.7  903.33  4938.1  897.71
  4969.7  880.96  4981.8  877.03  4983.2  873.27  5016.8  873.27  5022.9  875.36
  5033.8  877.05  5051.5   877.6  5079.5  880.03  5195.5  878.23  5376.4  880.13
  5437.5  881.91  5529.7   887.5  5559.5  890.43  5574.2  890.37  5580.9  889.53
  5602.1  893.75  5618.5  895.19  5650.3  899.71  5676.4   902.4  5709.8  905.09
  5727.2  905.91  5743.9  908.36  5752.8  908.51    5774  911.43  5845.8  915.16
#Mann= 4 ,-1 , 0
  4858.2     .09       0  4981.8     .05       0  5033.8     .09       0
  5079.5     .06       0
Bank Sta=4981.8,5033.8
Exp/Cntr=0.3,0.1

Type RM Length L Ch R = 1 ,16021   ,743,743,743
BEGIN DESCRIPTION:
Cane_Creek_XS-28
END DESCRIPTION:
XS GIS Cut Line= 2
      1145990.55       634330.47      1145383.55       634997.63
#Sta/Elev= 30
  4797.3  910.27  4812.4  908.07  4826.4  904.49  4844.4     902  4857.7  898.68
  4876.7  895.63  4902.2  889.19  4922.4  877.83  4924.8  877.16  4936.5  877.78
    4966   875.7  4983.2  870.99  5016.8  870.99  5018.5  875.22  5036.3  877.18
  5056.7  876.39  5089.1  877.28  5152.5  876.62  5256.2  878.25  5365.3  878.56
  5501.7  880.46  5549.7  882.81  5570.2   884.9  5602.5  886.43  5617.3  890.38
  5630.7  892.38  5644.5   896.9  5667.7  901.17  5678.5   905.4  5699.2  910.69
#Mann= 4 ,-1 , 0
  4797.3     .09       0    4966     .05       0  5018.5     .09       0
  5089.1     .06       0
Bank Sta=4966,5018.5
Exp/Cntr=0.3,0.1

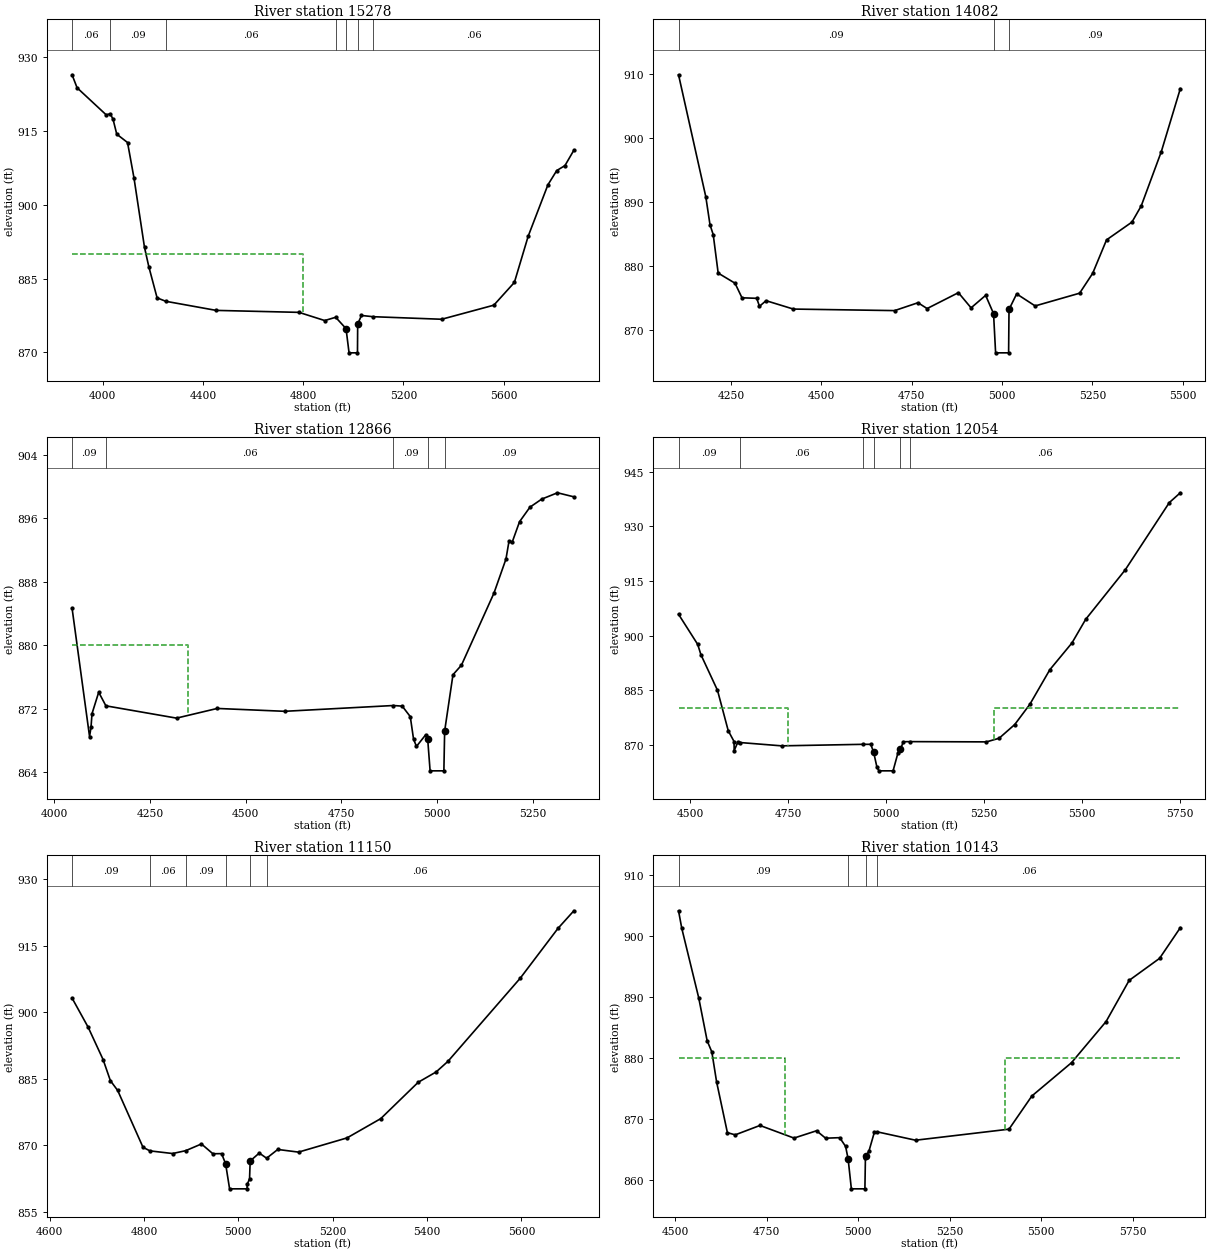
Type RM Length L Ch R = 1 ,15278   ,1196,1196,1196
BEGIN DESCRIPTION:
Cane_Creek_XS-27
END DESCRIPTION:
XS GIS Cut Line= 4
      1146372.94       633502.42      1145607.32       633778.46
      1145305.02       634031.01      1144992.73       634762.83
#Sta/Elev= 30
  3877.3  926.38  3897.3  923.74  4013.8  918.23  4029.7  918.47  4040.9  917.34
  4055.7  914.32  4098.8  912.62  4124.5  905.43  4166.5  891.32  4183.7  887.41
  4216.8  881.07  4251.4  880.38  4452.6  878.53  4783.3  878.13  4885.9  876.47
  4929.7  877.13  4971.1  874.83  4983.2  869.91  5016.8  869.91  5017.6  875.76
  5032.8   877.5  5078.8  877.25  5352.9  876.73  5561.2  879.59  5643.2  884.21
  5698.3  893.59  5777.2  904.04  5812.4  906.93  5845.2  907.94  5880.7  911.06
#Mann= 7 ,-1 , 0
  3877.3     .06       0  4029.7     .09       0  4251.4     .06       0
  4929.7     .09       0  4971.1     .05       0  5017.6     .09       0
  5078.8     .06       0
#XS Ineff= 2 , 0
       0    4800     890               0
Permanent Ineff=
       F       F
Bank Sta=4971.1,5017.6
Exp/Cntr=0.3,0.1

Type RM Length L Ch R = 1 ,14082   ,1216,1216,1216
BEGIN DESCRIPTION:
Cane_Creek_XS-26
END DESCRIPTION:
XS GIS Cut Line= 4
      1145203.09       632482.12      1145000.31       632770.74
      1144493.29       633343.89      1144388.36       633593.51
#Sta/Elev= 30
  4104.5  909.86    4180  890.79  4191.6  886.42  4200.5  884.88  4214.2  878.87
  4260.8  877.29  4280.1  875.01  4320.9  874.93  4328.5  873.68  4346.7  874.56
  4422.3  873.25  4702.5  873.01  4767.2  874.24  4792.4  873.33    4879  875.81
  4914.1  873.44  4954.4  875.39  4976.3  872.54    4982  866.41    5018  866.41
  5019.1  873.19  5040.2  875.62  5091.4  873.74  5214.5  875.73  5250.6  878.83
    5289  884.06  5359.3  886.84    5385  889.37  5440.7  897.87  5493.2   907.7
#Mann= 3 ,-1 , 0
  4104.5     .09       0  4976.3     .05       0  5019.1     .09       0
Bank Sta=4976.3,5019.1
Exp/Cntr=0.3,0.1

Type RM Length L Ch R = 1 ,12866   ,812,812,812
BEGIN DESCRIPTION:
Cane_Creek_XS-25
END DESCRIPTION:
XS GIS Cut Line= 4
      1144528.98       632283.61      1143677.42       632544.03
      1143487.32       632645.59      1143328.46        632775.8
#Sta/Elev= 30
  4046.3  884.67    4092   868.5  4095.8  869.66  4098.4  871.38  4115.9  874.08
  4134.7  872.37  4319.3  870.82  4425.6  872.04  4601.9  871.68  4886.3  872.41
  4909.2  872.33  4930.2  871.01  4938.8  868.15  4946.4  867.26  4970.8  868.74
  4975.6  868.24    4982  864.18    5018  864.18    5020  869.19  5041.8  876.29
  5063.9  877.49  5148.9  886.57  5180.3  890.87  5188.2  893.12  5196.9  893.04
  5215.8  895.57    5243   897.4  5273.6  898.41  5314.9  899.21  5357.7   898.7
#Mann= 5 ,-1 , 0
  4046.3     .09       0  4134.7     .06       0  4886.3     .09       0
  4975.6     .05       0    5020     .09       0
#XS Ineff= 2 , 0
       0    4350     880               0
Permanent Ineff=
       F       F
Bank Sta=4975.6,5020
Exp/Cntr=0.3,0.1

Type RM Length L Ch R = 1 ,12054   ,904,904,904
BEGIN DESCRIPTION:
Cane_Creek_XS-24
END DESCRIPTION:
XS GIS Cut Line= 4
      1144203.46       631872.15      1143747.73       631864.34
      1143630.54       631859.13      1142930.02       631955.49
#Sta/Elev= 30
  4470.6  905.83  4519.5  897.56  4527.7  894.74    4570  884.96  4597.4  873.87
  4612.3  870.89  4612.5   868.4  4621.6  870.64  4627.6  870.62  4733.6  869.71
  4941.2  870.13    4961  870.13  4968.3  868.01  4976.9  863.81    4982  862.85
    5018  862.85  5030.4  867.75  5036.8  868.81  5044.4  870.84  5061.3  870.87
  5256.3   870.8  5288.5  871.79  5328.4  875.56  5366.9   881.1  5417.9   890.6
  5474.5  897.97  5509.3  904.42  5610.4  918.03  5722.8  936.49  5750.9  939.18
#Mann= 6 ,-1 , 0
  4470.6     .09       0  4627.6     .06       0  4941.2     .09       0
  4968.3     .05       0  5036.8     .09       0  5061.3     .06       0
#XS Ineff= 2 , 0
       0    4750     880    5275       0     880
Permanent Ineff=
       F       F
Bank Sta=4968.3,5036.8
Exp/Cntr=0.3,0.1

Type RM Length L Ch R = 1 ,11150   ,1007,1007,1007
BEGIN DESCRIPTION:
Cane_Creek_XS-23
END DESCRIPTION:
XS GIS Cut Line= 4
      1143687.84       630924.24      1143427.42       631010.17
      1143268.57       631114.34      1142864.92       631557.05
#Sta/Elev= 30
  4647.7  903.18  4681.7  896.62  4713.4  889.31  4728.9  884.54  4744.4  882.32
    4798   869.5  4812.7  868.69  4860.8  868.09  4888.6  868.74  4921.8  870.25
  4946.1  868.04  4964.6  868.07  4973.1  865.75  4981.5  860.12  5018.5  860.12
  5018.8  861.11  5023.8  862.39  5025.1  866.41  5044.4   868.2  5059.9  867.03
  5083.6  869.01  5127.6  868.41  5230.4  871.62  5301.8  875.97  5381.1  884.17
  5419.2  886.51  5444.1  888.89  5597.3  907.66  5677.3  918.91    5711  922.89
#Mann= 6 ,-1 , 0
  4647.7     .09       0  4812.7     .06       0  4888.6     .09       0
  4973.1     .05       0  5025.1     .09       0  5059.9     .06       0
Bank Sta=4973.1,5025.1
Exp/Cntr=0.3,0.1

Type RM Length L Ch R = 1 ,10143   ,385,385,385
BEGIN DESCRIPTION:
Cane_Creek_XS-22
END DESCRIPTION:
XS GIS Cut Line= 5
      1143091.48       630156.01       1142726.9       630333.09
      1142617.52       630450.28      1142482.11       630705.49
      1142422.21       631218.51
#Sta/Elev= 30
  4509.3  904.12  4518.2  901.23  4564.4  889.86  4587.5  882.81  4600.3  880.98
  4613.3  876.07  4642.8  867.75  4664.2  867.39  4731.8  868.93  4824.8  866.86
  4886.4  868.06  4911.1  866.84  4949.6  866.93  4965.8  865.49  4972.7  863.42
  4981.5  858.54  5018.5  858.54  5019.9  863.59  5022.5  863.99  5029.9   864.8
  5044.4  867.83  5052.3  867.88  5156.9  866.51  5412.2  868.32  5474.7  873.76
    5583  879.22  5677.5  885.97  5740.5  892.71  5823.6  896.32  5880.3  901.35
#Mann= 4 ,-1 , 0
  4509.3     .09       0  4972.7     .05       0  5022.5     .09       0
  5052.3     .06       0
#XS Ineff= 2 , 0
       0    4800     880    5400       0     880
Permanent Ineff=
       F       F
Bank Sta=4972.7,5022.5
Exp/Cntr=0.5,0.3

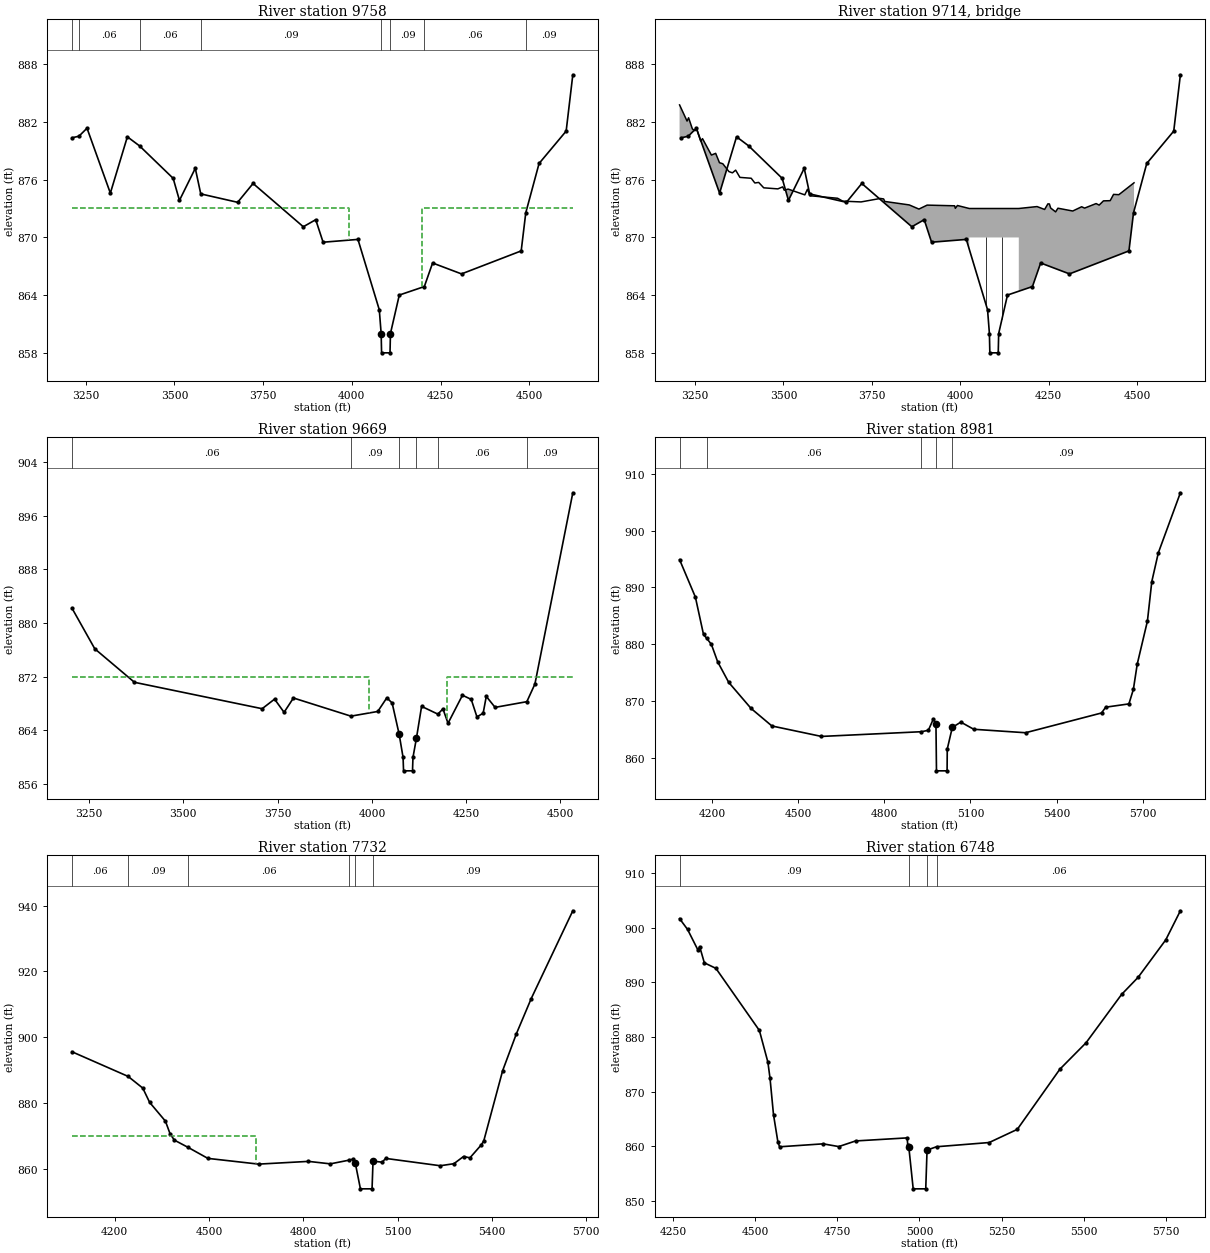
Type RM Length L Ch R = 1 ,9758    ,89,89,89
BEGIN DESCRIPTION:
Cane_Creek_XS-21
END DESCRIPTION:
XS GIS Cut Line= 6
      1142822.14       629145.91      1142755.16       629279.88
      1142466.92       630024.84      1142225.36        630477.5
      1142208.96        630536.3      1142091.48       630697.67
#Sta/Elev= 30
3211.486  880.323230.899  880.483253.754  881.313319.532  874.593367.452  880.42
3401.774  879.483496.551  876.123514.244  873.843558.888  877.163574.288  874.51
3678.238  873.643721.735  875.593863.285  871.113898.263  871.843919.069  869.51
4017.286   869.84077.411  862.524082.654  860.064083.883  858.064107.638  858.06
4108.867  860.06 4133.78  864.04 4204.38  864.924227.644  867.364309.149  866.23
4477.321  868.614490.264  872.564527.699  877.664604.044  881.014622.803  886.84
#Mann= 8 ,-1 , 0
3211.486     .09       03230.899     .06       03401.774     .06       0
3574.288     .09       04082.654     .05       04108.867     .09       0
 4204.38     .06       04490.264     .09       0
#XS Ineff= 2 , 0
       0    3992     873    4198       0     873
Permanent Ineff=
       F       F
Bank Sta=4082.654,4108.867
Skew Angle= 35
Exp/Cntr=0.5,0.3

Type RM Length L Ch R = 3 ,9714    ,,,
BEGIN DESCRIPTION:
Cane_Creek_XS-20
Structure ID: Pearidge Rd
Approximate Survey Structure
END DESCRIPTION:
Bridge Culvert--1,0,-1,-1, 0
Deck Dist Width WeirC Skew NumUp NumDn MinLoCord MaxHiCord MaxSubmerge Is_Ogee
34,30,3,35, 60, 60, , , , 0, 1,1,,
3206.3253227.4593231.8013242.6143250.0683254.2453265.9593271.202 3296.353308.391
3319.1223328.6243345.909 3355.823364.9133376.9543408.9013419.2233430.035 3444.37
3484.2633498.0253502.3673513.2613560.5263567.9813575.1893653.1733667.6713719.605
3774.1613783.4993786.6123855.9133883.2723906.5363984.274 3986.243992.2194025.723
4025.7234165.7984165.7984217.4044238.7844248.123  4252.34255.9044269.9124276.465
4318.3244343.5544351.9094384.429 4393.034405.236 4424.244433.8254448.7334491.738
  883.72  882.05  882.39  881.23  881.05  881.27  879.98  880.23  878.53  878.71
  877.74  877.63  876.82  876.69  876.97  876.22  876.13  875.64   875.7  875.14
  875.03  875.24  874.89  875.01  874.41  874.99  874.32  874.06  873.76  873.68
  874.04  873.99  873.73  873.37  872.94  873.35  873.28  873.02  873.31     873
     873     873     873   873.2   872.9  873.48  873.47  873.05  872.65  873.03
  872.74  873.18  873.04  873.51  873.35  873.79  873.81  874.46  874.43  875.66
  838.02  838.02  838.02  838.02  838.02  838.02  838.02  838.02  838.02  838.02
  838.02  838.02  838.02  838.02  838.02  838.02  838.02  838.02  838.02  838.02
  838.02  838.02  838.02  838.02  838.02  838.02  838.02  838.02  838.02  838.02
  838.02  838.02  838.02  838.02  838.02  838.02  838.02  838.02  838.02  838.02
     870     870  838.02  838.02  838.02  838.02  838.02  838.02  838.02  838.02
  838.02  838.02  838.02  838.02  838.02  838.02  838.02  838.02  838.02  838.02
3206.3253227.4593231.8013242.6143250.0683254.2453265.9593271.202 3296.353308.391
3319.1223328.6243345.909 3355.823364.9133376.9543408.9013419.2233430.035 3444.37
3484.2633498.0253502.3673513.2613560.5263567.9813575.1893653.1733667.6713719.605
3774.1613783.4993786.6123855.9133883.2723906.5363984.274 3986.243992.2194025.723
4025.7234165.7984165.7984217.4044238.7844248.123  4252.34255.9044269.9124276.465
4318.3244343.5544351.9094384.429 4393.034405.236 4424.244433.8254448.7334491.738
  883.72  882.05  882.39  881.23  881.05  881.27  879.98  880.23  878.53  878.71
  877.74  877.63  876.82  876.69  876.97  876.22  876.13  875.64   875.7  875.14
  875.03  875.24  874.89  875.01  874.41  874.99  874.32  874.06  873.76  873.68
  874.04  873.99  873.73  873.37  872.94  873.35  873.28  873.02  873.31     873
     873     873     873   873.2   872.9  873.48  873.47  873.05  872.65  873.03
  872.74  873.18  873.04  873.51  873.35  873.79  873.81  874.46  874.43  875.66
  838.02  838.02  838.02  838.02  838.02  838.02  838.02  838.02  838.02  838.02
  838.02  838.02  838.02  838.02  838.02  838.02  838.02  838.02  838.02  838.02
  838.02  838.02  838.02  838.02  838.02  838.02  838.02  838.02  838.02  838.02
  838.02  838.02  838.02  838.02  838.02  838.02  838.02  838.02  838.02  838.02
     870     870  838.02  838.02  838.02  838.02  838.02  838.02  838.02  838.02
  838.02  838.02  838.02  838.02  838.02  838.02  838.02  838.02  838.02  838.02
Pier Skew= 35
Pier Skew, UpSta & Num, DnSta & Num=  ,4073.26, 2 ,4073.26, 2 , 0 , 0 , 0 ,0,0
       2       2
  865.61     870
       2       2
  869.13     870
Pier Skew, UpSta & Num, DnSta & Num=  ,4118.26, 2 ,4118.26, 2 , 0 , 0 , 0 ,0,0
       2       2
     848     870
       2       2
  847.75     870
Abutment Skew #Up #Dn= , 2 , 2
4025.7234034.324
     870     865
4025.7234034.324
     870   868.6
Abutment Skew #Up #Dn= , 2 , 2
4153.1014165.798
     860     870
4164.5694165.798
  865.69     862
BR Coef= 1 , 1 , 0 ,1.25, 0 ,,,0.8,0,2,0,
WSPro=,,,, 1 ,,,, 0 ,,,, 0 ,,,,-1 ,-1 ,-1 , 0 , 0 , 0 , 0 , 0
BC Design=,, 0 ,, 0 ,,,,,,
BC HTab HWMax=886.84

Type RM Length L Ch R = 1 ,9669    ,688,688,688
BEGIN DESCRIPTION:
Cane_Creek_XS-19
END DESCRIPTION:
XS GIS Cut Line= 6
      1142762.06       629067.47      1142668.31       629294.03
      1142462.58       629846.11      1142384.45       630017.99
      1142152.68       630442.47      1142069.35       630520.59
#Sta/Elev= 30
 3204.85  882.213265.222  876.163370.401  871.163708.957  867.22 3741.89  868.65
3767.116  866.683791.937  868.823944.381  866.114015.565  866.814039.566  868.85
4053.656  868.07 4072.25  863.414082.654  859.954083.883  857.954107.638  857.95
4108.867  859.954118.123  862.844131.721  867.574174.973  866.414188.325   867.2
 4201.84  865.054240.095  869.234263.359  868.614278.513     8664294.978  866.55
4303.251  869.064326.597  867.424410.806  868.274432.186   870.94532.696  899.44
#Mann= 6 ,-1 , 0
 3204.85     .06       03944.381     .09       0 4072.25     .05       0
4118.123     .09       04174.973     .06       04410.806     .09       0
#XS Ineff= 2 , 0
       0    3992     872    4198       0     872
Permanent Ineff=
       F       F
Bank Sta=4072.25,4118.123
Skew Angle= 35
Exp/Cntr=0.5,0.3

Type RM Length L Ch R = 1 ,8981    ,1249,1249,1249
BEGIN DESCRIPTION:
Cane_Creek_XS-18
END DESCRIPTION:
XS GIS Cut Line= 6
      1142767.26       628856.53      1142588.81       629025.86
      1142208.57       629411.45      1142021.13       629523.92
      1141683.74       629759.55      1141410.61       629941.64
#Sta/Elev= 30
  4085.9   894.9    4141  888.31  4169.3  881.73  4180.8  881.02  4196.8  879.98
  4218.7  876.91  4257.2  873.29  4335.1   868.7  4407.8  865.61  4580.5  863.77
  4928.9   864.6  4953.2  864.85    4971  866.88  4979.7  865.91  4981.5  857.71
  5018.5  857.71  5019.1  861.55  5036.7  865.36  5066.4  866.29  5111.5  865.03
  5292.1  864.42  5556.9   867.9  5571.4  868.92  5652.4   869.5  5667.9  872.05
  5681.5  876.53  5716.9  884.08  5732.2  891.05  5754.9   896.1  5831.8  906.68
#Mann= 5 ,-1 , 0
  4085.9     .09       0  4180.8     .06       0  4928.9     .09       0
  4979.7     .05       0  5036.7     .09       0
Bank Sta=4979.7,5036.7
Exp/Cntr=0.3,0.1

Type RM Length L Ch R = 1 ,7732    ,984,984,984
BEGIN DESCRIPTION:
Cane_Creek_XS-17
END DESCRIPTION:
XS GIS Cut Line= 5
      1142613.62       628499.76      1142329.76        628398.2
      1141834.97       628343.51      1141558.93       628437.26
      1141118.83       628679.45
#Sta/Elev= 30
    4064  895.62  4242.5  888.15  4289.1   884.6    4311  880.26  4361.2  874.57
  4376.1   870.7  4389.6  868.82  4433.6   866.6  4496.2  863.28  4657.6  861.54
  4816.2  862.37  4885.8  861.62  4946.2  862.76  4956.4  863.01  4965.2  861.84
  4981.5  854.04  5018.5  854.04  5021.6  862.44  5050.6  862.13  5061.9  863.27
  5235.4  861.05  5278.8  861.66  5309.5  863.85  5329.9  863.45  5366.3  867.41
    5374  868.62    5434   889.9  5477.8  901.12  5524.9  911.77  5657.2   938.4
#Mann= 6 ,-1 , 0
    4064     .06       0  4242.5     .09       0  4433.6     .06       0
  4946.2     .09       0  4965.2     .05       0  5021.6     .09       0
#XS Ineff= 2 , 0
       0    4650     870               0
Permanent Ineff=
       F       F
Bank Sta=4965.2,5021.6
Exp/Cntr=0.3,0.1

Type RM Length L Ch R = 1 ,6748    ,1025,1025,1025
BEGIN DESCRIPTION:
Cane_Creek_XS-16
END DESCRIPTION:
XS GIS Cut Line= 6
      1142043.31       627575.28      1141441.74        627523.2
      1141139.66        627588.3      1140900.08       627640.38
      1140741.22       627786.22      1140642.26        627900.8
#Sta/Elev= 30
  4269.5  901.65  4293.8  899.68  4325.5   895.9  4330.7  896.53  4344.9  893.57
  4380.1  892.56  4512.5   881.2  4538.4  875.41  4544.9  872.46  4555.5   865.8
  4568.8  860.83    4574  859.92  4706.5  860.46  4754.2  859.96  4805.5  860.99
  4962.5  861.55  4964.4  860.21  4967.4  859.96  4980.9  852.23  5019.1  852.23
  5023.1  859.32    5052  859.93  5212.3   860.7  5297.9  863.11  5427.5  874.11
  5507.3  878.95  5615.4  887.78    5666  890.93    5750  897.77  5794.5  903.09
#Mann= 4 ,-1 , 0
  4269.5     .09       0  4967.4     .05       0  5023.1     .09       0
    5052     .06       0
Bank Sta=4967.4,5023.1
Exp/Cntr=0.3,0.1