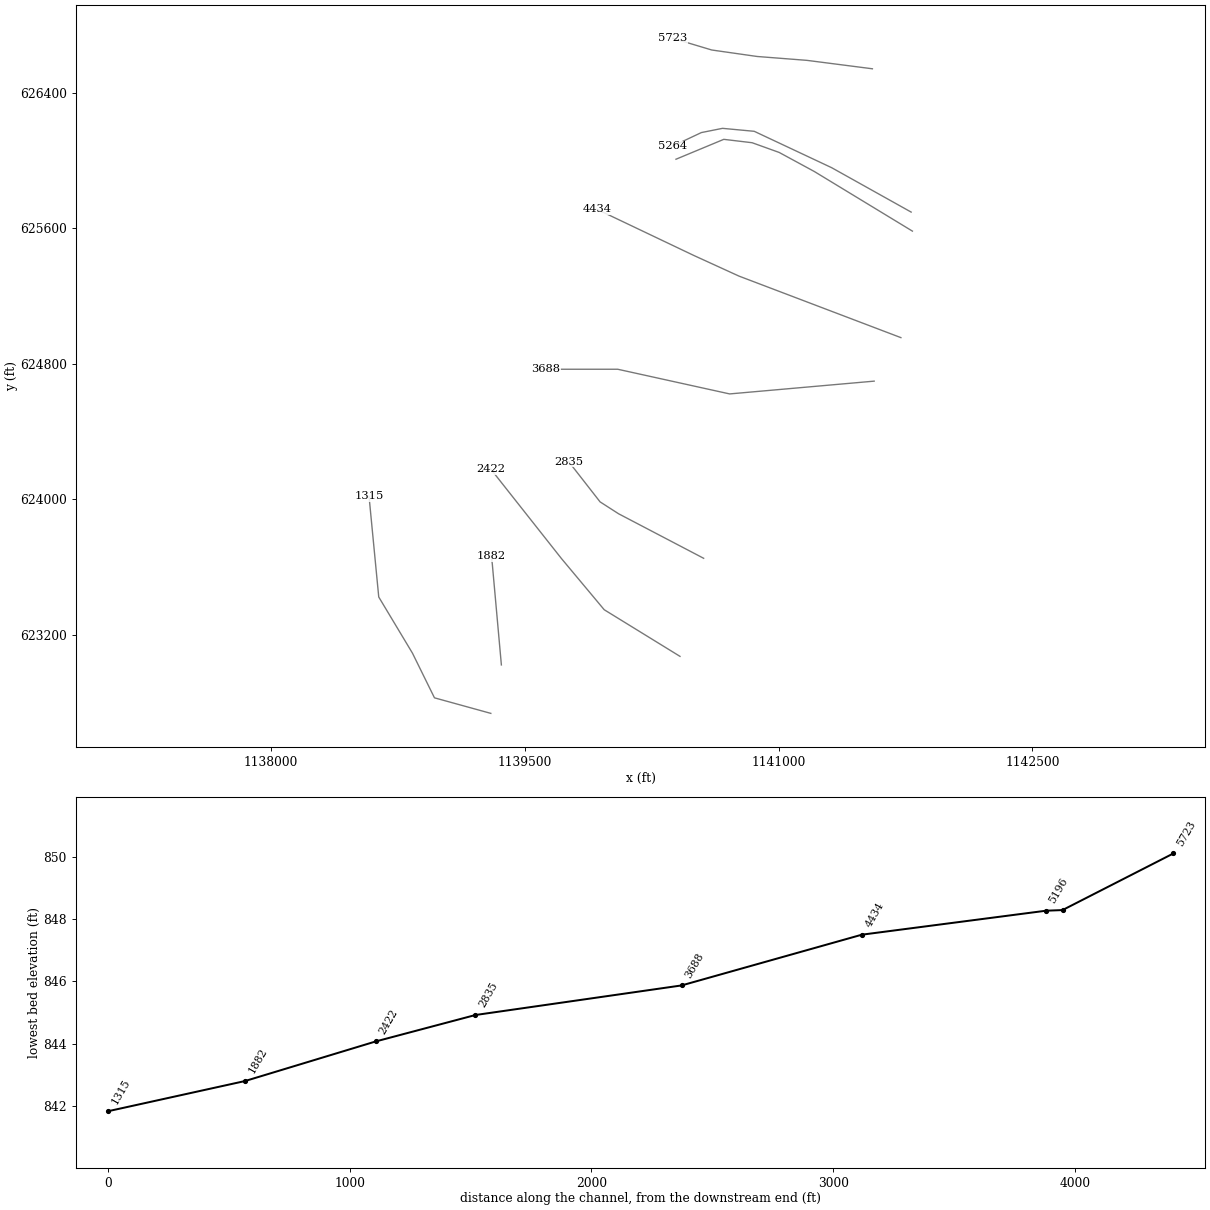
HEC-RAS study lds_cane_crk.prj: Cane Creek Limited Detail Study

--- lds_cane_crk.g01 (geometry) --- (continued)

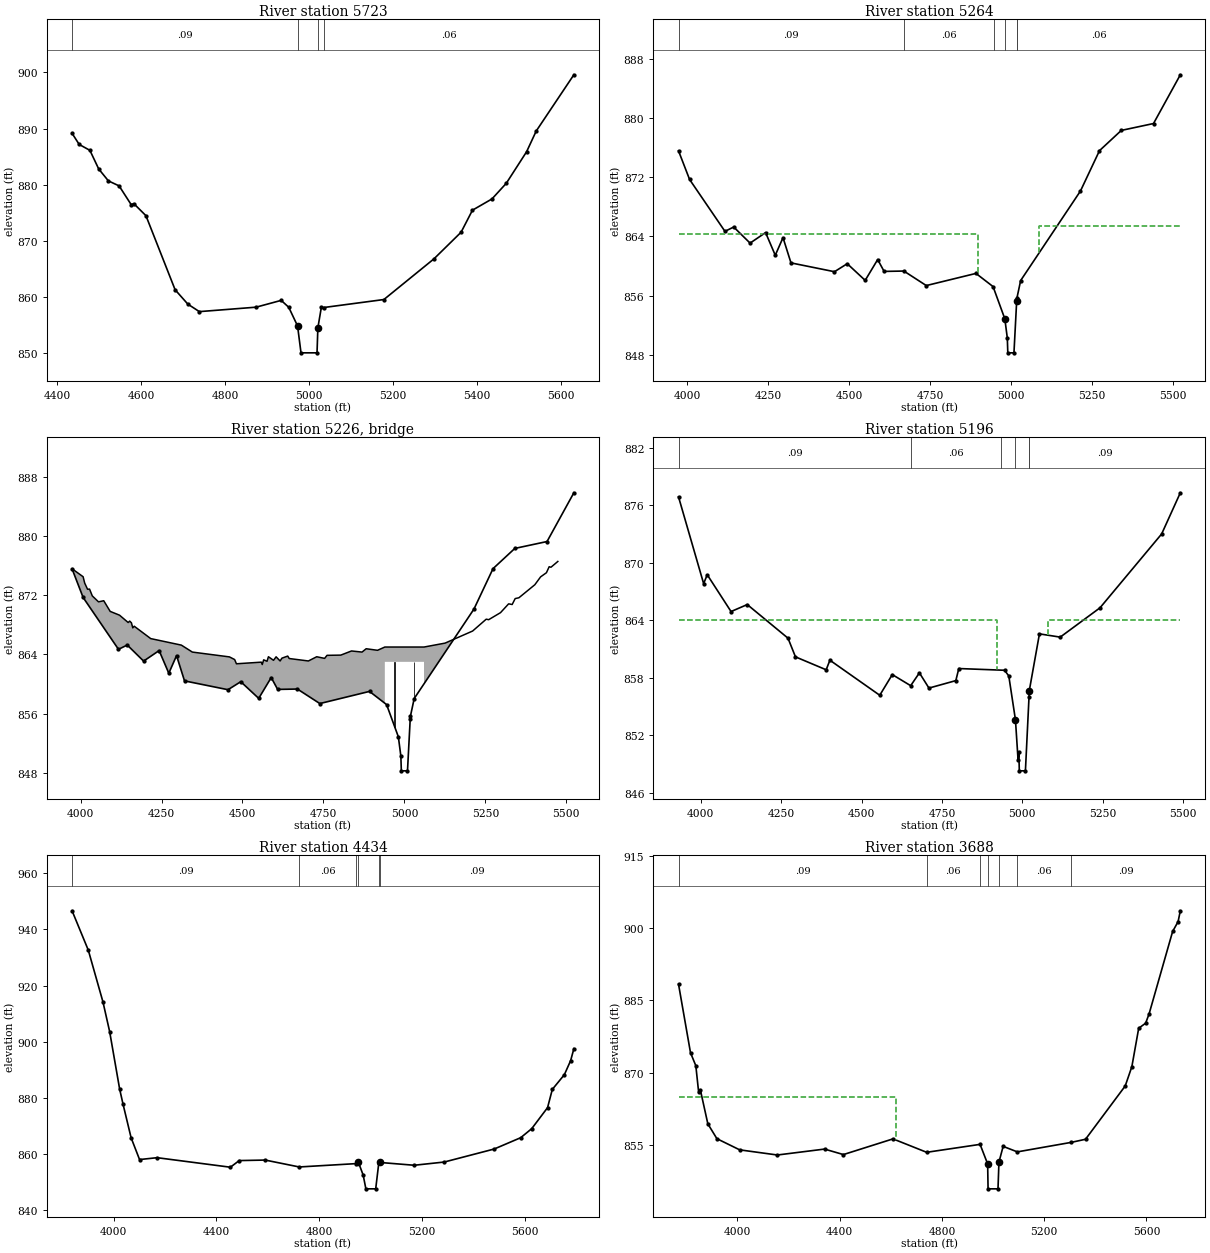
Type RM Length L Ch R = 1 ,5723    ,459,459,459
BEGIN DESCRIPTION:
Cane_Creek_XS-14
END DESCRIPTION:
XS GIS Cut Line= 5
      1141554.42       626543.31      1141167.74       626593.08
      1140872.94       626616.05      1140604.94       626654.33
      1140375.23       626723.25
#Sta/Elev= 30
  4435.2  889.15  4452.2  887.17  4477.7  886.12  4498.7  882.81  4521.8  880.69
  4547.3   879.8  4575.9  876.49  4582.6  876.63  4611.3   874.5  4680.8  861.33
  4711.2  858.77  4738.6  857.44  4873.8  858.23  4933.7  859.44  4951.7  858.21
  4972.7  854.89  4980.9  850.11  5019.1  850.11  5021.1  854.55  5029.4  858.21
  5035.2  858.17  5178.5  859.59  5297.9  866.83  5362.5  871.56  5389.6  875.48
  5436.1  877.48  5470.2  880.26  5518.7  885.88  5541.6  889.56  5631.3  899.56
#Mann= 4 ,-1 , 0
  4435.2     .09       0  4972.7     .05       0  5021.1     .09       0
  5035.2     .06       0
Bank Sta=4972.7,5021.1
Exp/Cntr=0.5,0.3

Type RM Length L Ch R = 1 ,5264    ,68,68,68
BEGIN DESCRIPTION:
Cane_Creek_XS-13
END DESCRIPTION:
XS GIS Cut Line= 6
      1141783.44       625696.39      1141313.51       625958.85
      1140856.09       626173.81      1140668.62       626191.31
      1140543.64       626166.32      1140373.67       626086.33
#Sta/Elev= 30
  3973.8  875.55  4007.9  871.69  4117.1  864.69  4144.2  865.27  4194.7   863.1
  4242.6  864.52  4272.5  861.46  4296.4  863.84    4321  860.43  4455.3  859.24
  4494.7  860.32  4550.1  858.07  4588.7  860.88  4608.6  859.28 4669.55  859.33
  4738.8  857.37  4892.2  859.01    4945  857.23  4981.3  852.88    4989  850.29
  4990.5  848.29  5009.5  848.29  5017.9  855.29  5018.6  855.67  5030.2  858.05
  5214.8  870.13  5273.6  875.58  5340.9  878.31  5440.4  879.24  5523.2  885.82
#Mann= 6 ,-1 , 0
  3973.8     .09       0 4669.55     .06       0  4947.3     .09       0
  4981.3     .05       0  5017.9     .09       0  5018.6     .06       0
#XS Ineff= 2 , 0
       0    4900  864.36    5087       0   865.4
Permanent Ineff=
       F       F
Bank Sta=4981.3,5017.9
Exp/Cntr=0.5,0.3

Type RM Length L Ch R = 3 ,5226    ,,,
BEGIN DESCRIPTION:
Cane_Creek_XS-12
Structure ID: Mackey Freeman Rd
Approximate Survey Structure
END DESCRIPTION:
Bridge Culvert--1,0,-1,-1, 0
Deck Dist Width WeirC Skew NumUp NumDn MinLoCord MaxHiCord MaxSubmerge Is_Ogee
26.5,23,3,0, 60, 60, , , , 0, 1,1,,
    3977  4007.9  4012.8  4021.6  4027.8  4036.3  4055.4  4071.6  4091.5  4120.4
    4147  4151.8  4157.1  4161.2  4165.7  4216.6  4311.2  4345.2  4459.7  4475.8
  4481.3  4558.1    4561  4565.4  4575.8  4580.1  4595.8  4603.8  4616.2  4621.8
  4639.7  4644.3  4703.5  4729.2  4753.6    4761  4803.5  4836.6  4869.1  4881.9
    4917  4939.5  4939.5  5060.5  5060.5  5125.6  5210.6  5252.6  5260.1  5296.7
  5321.8  5332.7    5342  5353.5  5402.7  5420.5  5438.5    5447  5452.5  5473.7
  875.46  874.49  873.63   872.8  872.82   871.9   871.1  871.25  869.81   869.3
  868.31   868.5  868.27  867.59  867.81  866.14  865.26  864.32  863.67  863.31
  862.74  862.96  862.64  863.27  863.08  863.69  863.21  863.68  863.12   863.5
  863.78  863.45  863.12  863.69  863.47  863.88  863.91  864.47  864.32  864.77
  864.56     865     865     865     865  865.53  867.16  868.76  868.69  869.64
  870.83  870.74  871.54  871.65  873.41  874.47  875.03  875.84  875.77  876.55
  828.28  828.28  828.28  828.28  828.28  828.28  828.28  828.28  828.28  828.28
  828.28  828.28  828.28  828.28  828.28  828.28  828.28  828.28  828.28  828.28
  828.28  828.28  828.28  828.28  828.28  828.28  828.28  828.28  828.28  828.28
  828.28  828.28  828.28  828.28  828.28  828.28  828.28  828.28  828.28  828.28
  828.28  828.28     863     863  828.28  828.28  828.28  828.28  828.28  828.28
  828.28  828.28  828.28  828.28  828.28  828.28  828.28  828.28  828.28  828.28
    3977  4007.9  4012.8  4021.6  4027.8  4036.3  4055.4  4071.6  4091.5  4120.4
    4147  4151.8  4157.1  4161.2  4165.7  4216.6  4311.2  4345.2  4459.7  4475.8
  4481.3  4558.1    4561  4565.4  4575.8  4580.1  4595.8  4603.8  4616.2  4621.8
  4639.7  4644.3  4703.5  4729.2  4753.6    4761  4803.5  4836.6  4869.1  4881.9
    4917  4939.5  4939.5  5060.5  5060.5  5125.6  5210.6  5252.6  5260.1  5296.7
  5321.8  5332.7    5342  5353.5  5402.7  5420.5  5438.5    5447  5452.5  5473.7
  875.46  874.49  873.63   872.8  872.82   871.9   871.1  871.25  869.81   869.3
  868.31   868.5  868.27  867.59  867.81  866.14  865.26  864.32  863.67  863.31
  862.74  862.96  862.64  863.27  863.08  863.69  863.21  863.68  863.12   863.5
  863.78  863.45  863.12  863.69  863.47  863.88  863.91  864.47  864.32  864.77
  864.56     865     865     865     865  865.53  867.16  868.76  868.69  869.64
  870.83  870.74  871.54  871.65  873.41  874.47  875.03  875.84  875.77  876.55
  828.28  828.28  828.28  828.28  828.28  828.28  828.28  828.28  828.28  828.28
  828.28  828.28  828.28  828.28  828.28  828.28  828.28  828.28  828.28  828.28
  828.28  828.28  828.28  828.28  828.28  828.28  828.28  828.28  828.28  828.28
  828.28  828.28  828.28  828.28  828.28  828.28  828.28  828.28  828.28  828.28
  828.28  828.28     863     863  828.28  828.28  828.28  828.28  828.28  828.28
  828.28  828.28  828.28  828.28  828.28  828.28  828.28  828.28  828.28  828.28
Pier Skew, UpSta & Num, DnSta & Num=  ,4969.8, 2 ,4969.8, 2 , 0 , 0 , 0 ,0,0
       1       1
  855.64     863
       1       1
  855.32     863
Pier Skew, UpSta & Num, DnSta & Num=  ,5030.3, 2 ,5030.3, 2 , 0 , 0 , 0 ,0,0
       1       1
  859.81     863
       1       1
  855.85     863
BR Coef= 1 , 1 , 0 ,1.25, 0 ,,,0.8,0,2,0,
WSPro=,,,, 1 ,,,, 0 ,,,, 0 ,,,,-1 ,-1 ,-1 , 0 , 0 , 0 , 0 , 0
BC Design=,, 0 ,, 0 ,,,,,,
BC HTab HWMax=885.82

Type RM Length L Ch R = 1 ,5196    ,762,762,762
BEGIN DESCRIPTION:
Cane_Creek_XS-11
END DESCRIPTION:
XS GIS Cut Line= 6
      1141790.93       625583.91      1141211.03       625936.35
      1141003.56       626048.84      1140843.59       626106.33
      1140676.12       626126.32      1140393.66       626008.84
#Sta/Elev= 30
  3930.8  876.87  4008.8  867.82  4020.1  868.74  4094.1   864.9  4144.5  865.63
  4271.2  862.12  4294.4  860.17  4389.9  858.82  4401.5  859.82  4556.5  856.16
  4595.5  858.32  4652.7  857.16  4679.8   858.5  4709.5  856.91  4793.1  857.69
  4802.3  858.95 4944.62  858.77 4957.79  858.18  4978.5  853.59  4986.6  849.43
    4989  850.27  4990.5  848.27  5009.5  848.27  5020.7  855.99  5021.6  856.65
  5053.1  862.57  5117.7  862.23  5241.4  865.29  5433.1     873  5491.2   877.3
#Mann= 6 ,-1 , 0
  3930.8     .09       0  4652.7     .06       0 4932.63     .09       0
  4978.5     .05       0  5020.7     .06       0  5021.6     .09       0
#XS Ineff= 2 , 0
       0    4921     864    5079       0     864
Permanent Ineff=
       F       F
Bank Sta=4978.5,5021.6
Exp/Cntr=0.5,0.3

Type RM Length L Ch R = 1 ,4434    ,746,746,746
BEGIN DESCRIPTION:
Cane_Creek_XS-9
END DESCRIPTION:
XS GIS Cut Line= 4
      1141722.87       624954.46      1140765.74       625318.18
      1140497.74       625440.69      1139927.29       625712.51
#Sta/Elev= 30
  3838.9  946.66    3902  932.61  3958.9  914.18  3984.9   903.6  4023.9  883.04
  4037.1  877.66  4068.4   865.7  4101.2  857.94  4169.4  858.61  4454.3  855.21
  4488.6  857.58 4589.65  857.76    4722   855.3  4940.9  856.48  4951.8  856.98
  4970.5  852.37  4980.9   847.5  5019.1   847.5    5031  856.67    5035  856.91
  5168.7  855.91  5285.6  857.06  5479.6   861.7  5582.7  865.74  5625.5  868.96
  5687.1  876.46  5705.6  882.97  5752.4  888.21  5776.8  893.23  5789.3  897.48
#Mann= 6 ,-1 , 0
  3838.9     .09       0    4722     .06       0  4940.9     .09       0
  4951.8     .05       0    5031     .06       0    5035     .09       0
Bank Sta=4951.8,5035
Exp/Cntr=0.3,0.1

Type RM Length L Ch R = 1 ,3688    ,853,853,853
BEGIN DESCRIPTION:
Cane_Creek_XS-8
END DESCRIPTION:
XS GIS Cut Line= 4
       1141564.9       624697.36      1140710.73       624621.83
      1140049.27       624767.67      1139622.19       624767.67
#Sta/Elev= 30
  3770.3  888.37  3817.1  874.15  3837.9  871.45    3849  865.91  3855.6  866.44
  3884.9  859.37  3920.3  856.29  4009.4  853.97  4156.6   852.9  4341.1  854.13
    4415  852.99  4608.9  856.25  4740.5  853.46  4949.3  855.11  4978.9  851.05
  4980.6  845.87  5019.4  845.87  5023.1  851.42  5039.5  854.69    5095  853.55
  5306.4  855.53  5361.6  856.17  5516.8  867.24  5542.8  871.26  5569.5  879.23
  5596.7  880.29  5610.3  882.24  5702.2  899.34  5723.6  901.39  5732.3  903.64
#Mann= 7 ,-1 , 0
  3770.3     .09       0  4740.5     .06       0  4949.3     .09       0
  4978.9     .05       0  5023.1     .09       0    5095     .06       0
  5306.4     .09       0
#XS Ineff= 2 , 0
       0    4620     865               0
Permanent Ineff=
       F       F
Bank Sta=4978.9,5023.1
Exp/Cntr=0.3,0.1

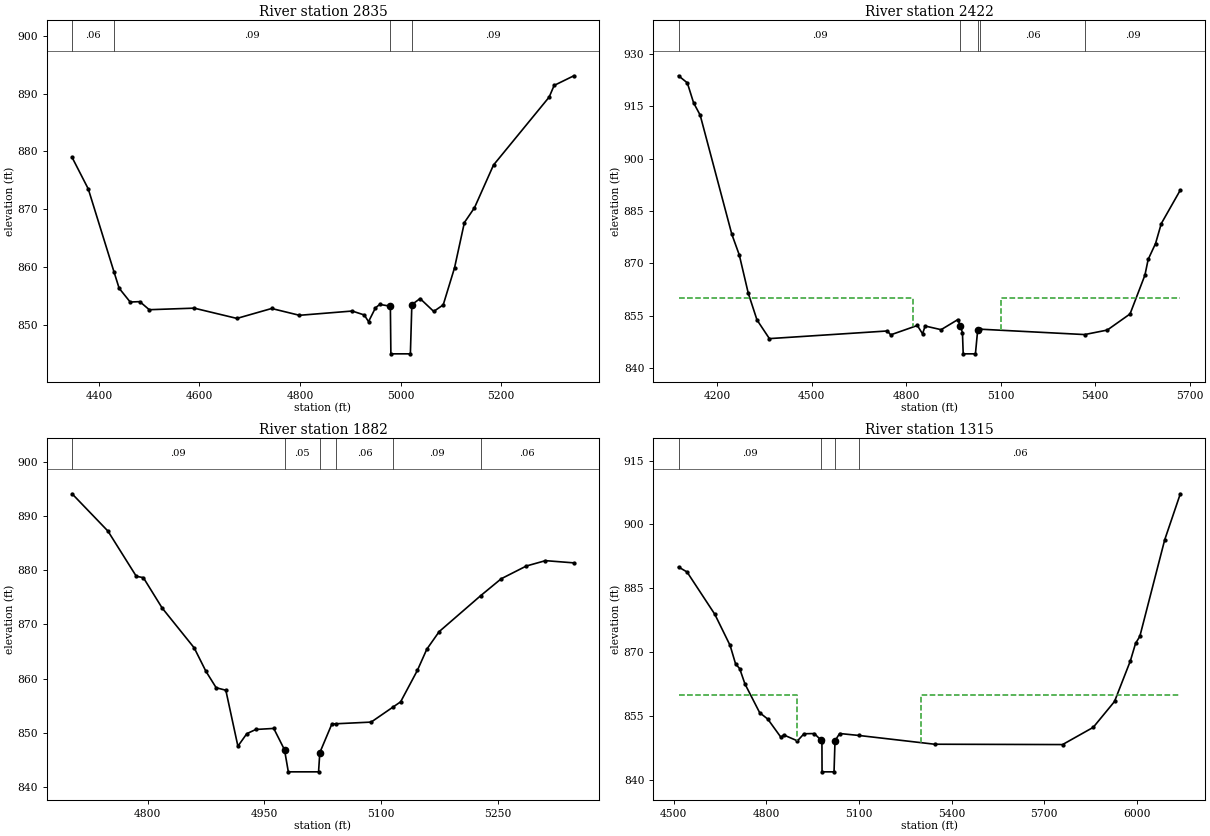
Type RM Length L Ch R = 1 ,2835    ,413,413,413
BEGIN DESCRIPTION:
Cane_Creek_XS-7
END DESCRIPTION:
XS GIS Cut Line= 4
      1140557.08       623650.48      1140054.48        623913.5
       1139945.1       623983.81      1139760.21       624220.79
#Sta/Elev= 30
  4346.6  878.98  4378.8  873.51  4429.9  859.15  4440.2  856.29  4462.2   853.9
  4481.3  853.97  4500.1  852.57  4589.4  852.84  4674.4  851.06  4743.5  852.78
  4798.8   851.6  4903.7  852.34  4927.6  851.66  4936.2   850.5    4950   852.9
  4958.5  853.49  4979.6  853.17  4980.6  844.92  5019.4  844.92  5022.3  853.45
  5038.7   854.5  5065.8  852.27  5084.7  853.41  5107.2  859.83  5126.8  867.68
  5146.9  870.25  5184.7  877.65  5295.4  889.43  5305.3  891.45  5344.5  893.12
#Mann= 4 ,-1 , 0
  4346.6     .06       0  4429.9     .09       0  4979.6     .05       0
  5022.3     .09       0
Bank Sta=4979.6,5022.3
Exp/Cntr=0.3,0.1

Type RM Length L Ch R = 1 ,2422    ,540,540,540
BEGIN DESCRIPTION:
Cane_Creek_XS-6
END DESCRIPTION:
XS GIS Cut Line= 4
      1140417.34       623070.82      1139969.41       623346.48
      1139716.72       623648.93      1139299.41       624177.27
#Sta/Elev= 30
  4076.7  923.71  4104.6  921.68  4124.5  915.97  4145.4  912.44  4245.8  878.35
  4269.6  872.39  4298.1  861.44  4325.8  853.78  4365.2  848.43  4739.6  850.62
  4750.4  849.51    4835  852.19  4851.5   849.8  4859.7  852.04  4910.4  850.99
  4963.8  853.89  4971.5  852.03  4978.2  850.14  4980.6  844.07  5019.4  844.07
  5026.6  850.94  5034.7  851.13  5366.1  849.59    5438  850.88  5510.3  855.49
  5557.6  866.61  5567.9  871.12  5591.3  875.66  5609.5  881.37    5670  890.98
#Mann= 5 ,-1 , 0
  4076.7     .09       0  4971.5     .05       0  5026.6     .09       0
  5034.7     .06       0  5366.1     .09       0
#XS Ineff= 2 , 0
       0    4820     860    5100       0     860
Permanent Ineff=
       F       F
Bank Sta=4971.5,5026.6
Exp/Cntr=0.3,0.1

Type RM Length L Ch R = 1 ,1882    ,567,567,567
BEGIN DESCRIPTION:
Cane_Creek_XS-5
END DESCRIPTION:
XS GIS Cut Line= 3
      1139361.77       623020.27      1139308.05       623617.69
      1139302.58       623661.44
#Sta/Elev= 30
  4703.1  894.11  4749.1  887.23  4785.5  878.89  4794.6  878.63  4818.7  873.03
  4859.8  865.68  4874.8  861.37    4888  858.32  4900.4  857.86  4915.9  847.53
  4927.3  849.84  4938.9  850.62  4961.9  850.81  4975.7  846.87  4980.6   842.8
  5019.4   842.8    5021  846.34  5036.4   851.6  5041.8  851.67  5086.9  851.98
  5114.9  854.75  5124.7  855.72  5146.2  861.52  5158.3  865.43  5174.2  868.68
  5227.6  875.33  5253.8  878.43    5286  880.78  5310.6  881.77    5347  881.36
#Mann= 6 ,-1 , 0
  4703.1     .09       0  4975.7     .05       0    5021     .09       0
  5041.8     .06       0  5114.9     .09       0  5227.6     .06       0
Bank Sta=4975.7,5021
Exp/Cntr=0.3,0.1

Type RM Length L Ch R = 1 ,1315    ,0,0,0
BEGIN DESCRIPTION:
Cane_Creek_XS-3
END DESCRIPTION:
XS GIS Cut Line= 5
      1139299.41       622733.91      1138966.33        622825.8
      1138836.16       623089.97      1138637.04       623421.62
      1138579.65       624016.47
#Sta/Elev= 30
    4516  889.98  4543.5  888.81  4633.4  878.87    4683  871.53  4700.7  867.19
  4713.9   866.1    4731  862.49  4778.7  855.73  4804.9  854.23  4847.7  849.93
  4856.3  850.51    4901  849.11  4922.1  850.78 4955.62  850.83  4978.4   849.2
  4980.2  848.84  4980.6  841.83  5019.4  841.83  5022.5  849.13  5037.5  850.84
  5098.6  850.39  5344.9  848.32  5759.2  848.24  5858.5  852.29  5927.4  858.37
  5978.8  867.94  5995.5  872.03  6009.3  873.67  6089.9  896.39  6140.4  907.19
#Mann= 4 ,-1 , 0
    4516     .09       0  4978.4     .05       0  5022.5     .09       0
  5098.6     .06       0
#XS Ineff= 2 , 0
       0    4900     860    5300       0     860
Permanent Ineff=
       F       F
Bank Sta=4978.4,5022.5
Exp/Cntr=0.3,0.1
Stream Node=Cane Creek      ,Reach-1         , 0 , 0 ,Upstream end
Stream Node=Cane Creek      ,Reach-1         , 0 , 1 ,Downstream end

Chan Stop Cuts=-1
Use User Specified Reach Order=0
User Specified Reach Order=Cane Creek      ,Reach-1